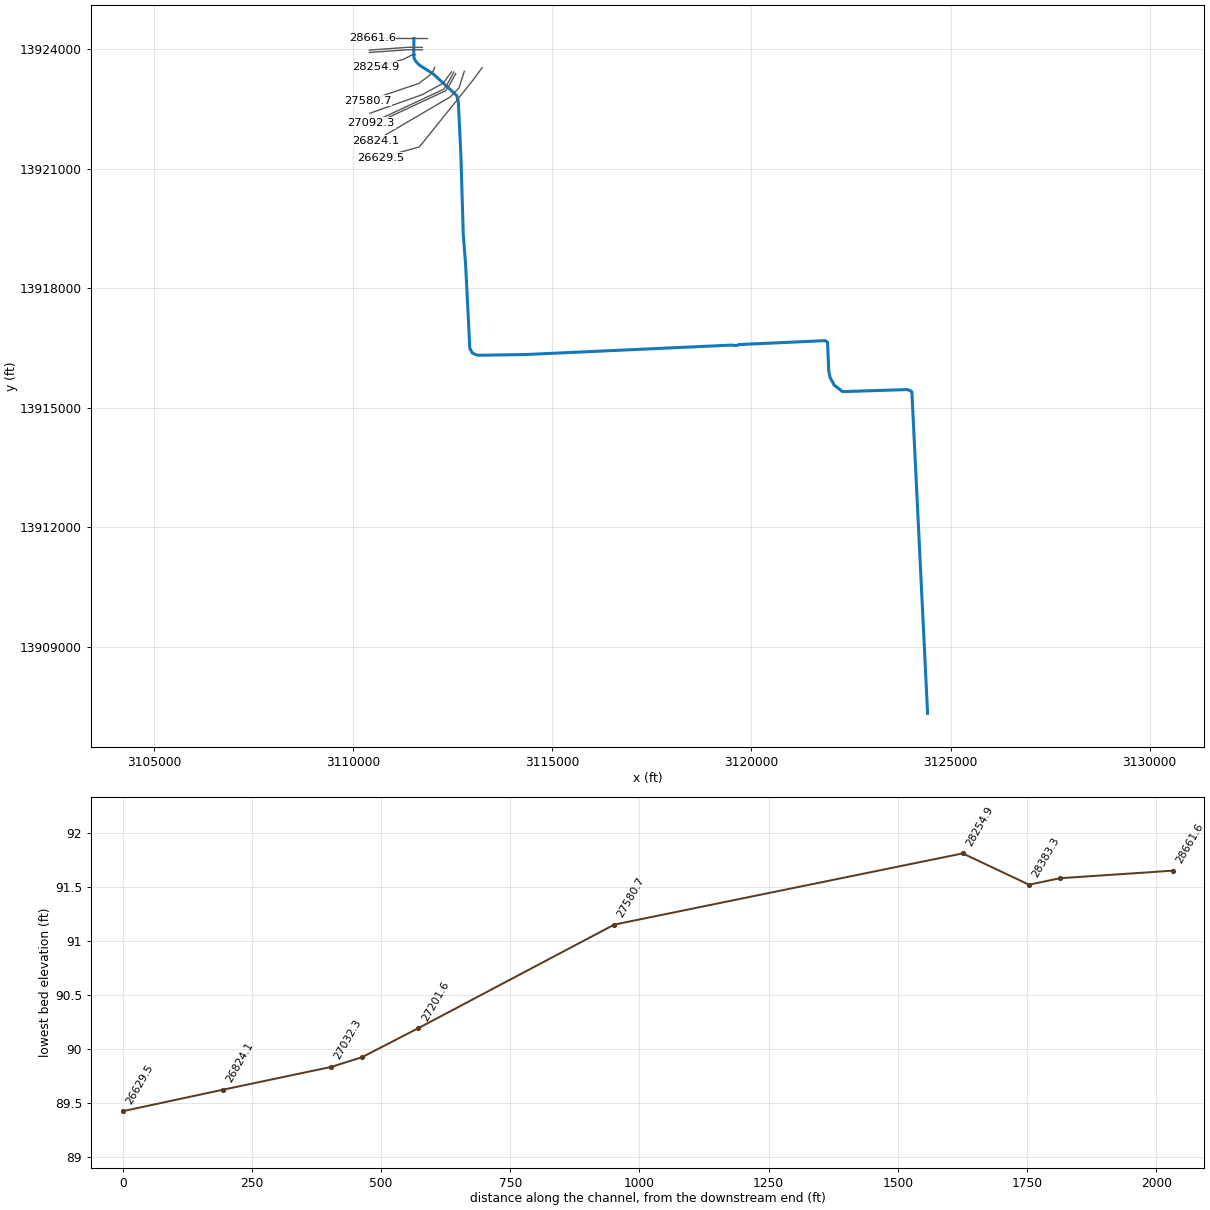
--- P140-00-00.prj (project) ---

Proj Title=P140-00-00 (Hoods Bayou)
Current Plan=p01
Default Exp/Contr=.3,.1
English Units
Geom File=g01
Flow File=f01
Flow File=f02
Plan File=p01
Plan File=p02
Y Axis Title=Elevation
X Axis Title(PF)=Main Channel Distance
X Axis Title(XS)=Station
BEGIN DESCRIPTION:
HCFCD MODEL SUMMARY METADATA
The purpose of this summary is to document the high points of hydrologic and hydraulic models filed within the HCFCD Model and Map Management (M3) system.  The document includes references to the project that prompted the creation or update of the model.
DESCRIPTION OF PROJECT:
The following model was the hydraulic model which represented the effective condition of Harris County's watersheds.
PURPOSE OF PROJECT:
Development of effective models to support the National Flood Insurance Program.
HCFCD Watershed Unit ID: P
M3 Study Identifier: 2007_Effective_P
Engineer: HCFCD
Project Name: EffectiveFEMA Study for watershed Greens Bayou (P)
Study Completion Date: 6/18/2007
FEMA Case Number: [No Data]
FEMA Approval Date: [No Date in Database]
Vertical Datum: NAVD 1988
Datum Note: 2001 ADJ
HYDRAULICS
HCFCD Unit No.:  P140-00-00
Hydraulic Program Name: HEC-RAS
Hydraulic Program Version: 3.0.1
Steady Hydraulic Model: Yes
Unsteady Hydraulic Model: No
Update 1:
The effective FEMA hydraulic model for unit number P140-00-00 has been updated by FEMA LOMR 17-06-3082P with an effective date of 4/2/2018.
END DESCRIPTION:
DSS Export Rating Curves= 0
DSS Export Rating Curve Sorted= 0
DSS Export Volume Flow Curves= 0
DXF Filename=..\..\..\..\..\CLOMR\Civil\Eng Design\Data\Models\RAS 3.0.1\P140_00_00_EDL.
DXF OffsetX= 0
DXF OffsetY= 0
DXF ScaleX= 1
DXF ScaleY= 10

--- P140-00-00.p01 (plan) ---

Plan Title=Effective Multi-Profile 2018
Version=Version 3.0.1  May 2012
Short Identifier=PostProj FP
Geom File=g01
Flow File=f01
Subcritical Flow
K Sum by GR= 0
Std Step Tol= 0.01
Critical Tol= 0.01
Num of Std Step Trials= 20
Max Error Tol= 0.3
Flow Tol Ratio= 0.001
Split Flow NTrial= 30
Split Flow Tol= 0.02
Split Flow Ratio= 0.02
Log Output Level= 0
Friction Slope Method= 1
Unsteady Friction Slope Method= 2
Parabolic Critical Depth
Global Vel Dist= 0 , 0 , 0
Global Log Level= 0
CheckData=True
Encroach Param=-1 ,0,0, 0
BEGIN DESCRIPTION:
FEMA Effective Multi-Profile June 2007 + LOMR 17-06-3082P
END DESCRIPTION:
Computation Interval=1HOUR
Output Interval=1HOUR
Run HTab= 0
Run UNet= 0
Run PostProcess= 0
UNET Theta= 1
UNET ZTol= 0.02
UNET ZSATol= 0.05
UNET MxIter= 20
UNET MaxInSteps= 0
UNET DtIC= 0
UNET DtMin= 0
UNET MaxCRTS= 20
UNET WFStab= 2
UNET SFStab= 1
UNET WFX= 1
UNET SFX= 1
UNET Convert EG Bridges= 0
UNET Use Existing IB Tables=-1
Instantaneous Interval=1HOUR
DSS File=dss
Write IC File= 0
IC Time=0
Write Velocity= 0
Write Detailed= 0

--- P140-00-00.p02 (plan) ---

Plan Title=Effective Floodway 2018
Version=Version 3.0.1  May 2012
Short Identifier=Post Project
Geom File=g01
Flow File=f02
Subcritical Flow
K Sum by GR= 0
Std Step Tol= 0.01
Critical Tol= 0.01
Num of Std Step Trials= 20
Max Error Tol= 0.3
Flow Tol Ratio= 0.001
Split Flow NTrial= 30
Split Flow Tol= 0.02
Split Flow Ratio= 0.02
Log Output Level= 0
Friction Slope Method= 1
Unsteady Friction Slope Method= 2
Parabolic Critical Depth
Global Vel Dist= 0 , 0 , 0
Global Log Level= 0
CheckData=True
Encroach Param= 0 ,0,0, 2
Encroach River=P140-00-00
Encroach Reach=P140-00-00_0012
Encroach Node=28661.6
       1    4970    5147
Encroach Node=28443.3
       1    4990    5177
Encroach Node=28383.3
       1    4990    5177
Encroach Node=28254.9
       1  4987.7    5165
Encroach Node=27580.7
       1    4910    5250
Encroach Node=27201.6
       1    4850    5300
Encroach Node=27092.3
       1    4850    5191
Encroach Node=27032.3
       1    4850    5191
Encroach Node=26824.1
       1    4825    5185
Encroach Node=26629.5
       1    4840    5152
Encroach Node=26561.5
       1    4840    5152
Encroach Node=25914.5
       1    4920    5030
Encroach Node=25427.8
       1    4915    5027
Encroach Node=24433.8
       1    4945    5045
Encroach Node=23413.6
       1  4948.7  5018.4
Encroach Node=22744.9
       1  4948.7  5018.4
Encroach Node=22492.3
       1 4974.54 5026.36
Encroach Node=22317.3
       1 4974.54 5026.36
Encroach Node=22253.6
       1  4960.2  5085.1
Encroach Node=22201.6
       1  4989.2  5015.1
Encroach Node=21685
       1 4918.09 5055.94
Encroach Node=21069.0
       1 4906.66 5077.91
Encroach Node=20703.5
       1 4897.29 5086.73
Encroach Node=20186.7
       1 4776.86 5041.27
Encroach Node=20004.6
       1 4928.09 5074.93
Encroach Node=19957.2
       1 4936.02 5066.49
Encroach Node=19869.3
       1 4927.12 5057.49
Encroach Node=19818.9
       1 4927.09 5057.27
Encroach Node=19445.7
       1 4959.39 5086.46
Encroach Node=19380.2
       1 4967.21 5094.61
Encroach Node=19284.2
       1 4927.19 5051.01
Encroach Node=19145.6
       1 4935.37 5105.62
Encroach Node=18878.2
       1 4952.02 5056.17
Encroach Node=18730.9
       1  4970.7  5013.3
Encroach Node=18510.9
       1  4980.7    5013
Encroach Node=18451.3
       1    4930    5110
Encroach Node=18398.3
       1    4930    5110
Encroach Node=18062.2
       1    4875    5060
Encroach Node=17281.3
       1    4956    5060
Encroach Node=17175.8
       1    4955    5060
Encroach Node=17115.8
       1    4955    5060
Encroach Node=16411.8
       1    4966    5060
Encroach Node=15932.8
       1    4970    5060
Encroach Node=15862.8
       1    4970    5060
Encroach Node=15777.0
       1    4960    5050
Encroach Node=15630.7
       1    4940    5040
Encroach Node=15566.1
       1    4940    5040
Encroach Node=15039.5
       1    4965    5035
Encroach Node=14424.9
       1    4945    5030
Encroach Node=14356.7
       1    4973    5030
Encroach Node=14283.7
       1    4973    5030
Encroach Node=13960.9
       1  4979.7  5029.5
Encroach Node=13671.1
       1  4979.7  5029.5
Encroach Node=13549.3
       1  4979.7  5029.5
Encroach Node=13451.3
       1  4979.7  5029.5
Encroach Node=13182.7
       1  4981.2  5019.7
Encroach Node=12048.6
       1  4984.6  5026.1
Encroach Node=11211.8
       1  4958.1 5061.21
Encroach Node=11195.6
       1  4958.1  5061.2
Encroach Node=11139.6
       1  4958.1  5061.2
Encroach Node=10668.7
       1  4942.7    5054
Encroach Node=10218.3
       1  4942.7    5054
Encroach Node=9242.9
       1  4942.5  5044.7
Encroach Node=8106.4
       1  4944.3  5064.2
Encroach Node=7536.4
       1  4938.7  5070.3
Encroach Node=6761.4
       1  4938.7  5054.6
Encroach Node=6308.0
       1  4941.6  5069.9
Encroach Node=6064.0
       1 4948.47 5070.67
Encroach Node=5940.8
       1 4948.47 5070.67
Encroach Node=5387.9
       1  4939.7  5052.2
Encroach Node=4850.2
       1  4939.7  5052.2
Encroach Node=4364.2
       1 4942.49 5047.69
Encroach Node=4176.8
       1 4942.49 5047.69
Encroach Node=4154.8
       1  4942.5  5047.7
Encroach Node=4100.8
       1  4942.5  5047.7
Encroach Node=3591.4
       1  4942.6  5045.2
Encroach Node=2895.0
       1  4945.3  5045.2
Encroach Node=1955.7
       1 4941.11 5045.21
Encroach Node=1933.7
       1 4941.11 5045.21
Encroach Node=1232.0
       1  4938.9  5043.6
BEGIN DESCRIPTION:
FEMA Effective Floodway June 2007 + LOMR 17-06-3082P
END DESCRIPTION:
Computation Interval=1HOUR
Output Interval=1HOUR
Run HTab= 0
Run UNet= 0
Run PostProcess= 0
UNET Theta= 1
UNET ZTol= 0.02
UNET ZSATol= 0.1
UNET MxIter= 20
UNET MaxInSteps= 20
UNET DtIC= 0
UNET DtMin= 0
UNET MaxCRTS= 20
UNET WFStab= 2
UNET SFStab= 1
UNET WFX= 1
UNET SFX= 1
UNET Convert EG Bridges=-1
UNET Use Existing IB Tables=-1
Instantaneous Interval=1HOUR
DSS File=dss
Write IC File= 0
IC Time=0
Write Velocity= 0
Write Detailed= 0

--- P140-00-00.f01 (steady flow) ---

Flow Title=Effective Multi-Profile 2018
Program Version=4.10
Number of Profiles= 4
Profile Names=10PCT_10yr, 2PCT_50yr, 1PCT_100yr, 0.2PCT_500yr
River Rch & RM=P140-00-00,P140-00-00_0012 ,28661.6
     276     407     466     649
River Rch & RM=P140-00-00,P140-00-00_0012 ,28443.3
     291     425     493     686
River Rch & RM=P140-00-00,P140-00-00_0012 ,28254.9
     355     518     600     836
River Rch & RM=P140-00-00,P140-00-00_0012 ,27580.7
     410     597     693     965
River Rch & RM=P140-00-00,P140-00-00_0012 ,27092.3
     443     646     750    1044
River Rch & RM=P140-00-00,P140-00-00_0012 ,26824.1
     467     682     791    1100
River Rch & RM=P140-00-00,P140-00-00_0012 ,26629.5
     489     711     823    1144
River Rch & RM=P140-00-00,P140-00-00_0012 ,25914.5
     503     728     842    1169
River Rch & RM=P140-00-00,P140-00-00_0012 ,25427.8
     530     765     882    1222
River Rch & RM=P140-00-00,P140-00-00_0012 ,24433.8
     561     804     924    1279
River Rch & RM=P140-00-00,P140-00-00_0012 ,23413.6
     595     849     972    1342
River Rch & RM=P140-00-00,P140-00-00_0012 ,22492.3
     616     875    1001    1380
River Rch & RM=P140-00-00,P140-00-00_0012 ,21685
     650     919    1048    1442
River Rch & RM=P140-00-00,P140-00-00_0012 ,20703.5
     668     942    1073    1475
River Rch & RM=P140-00-00,P140-00-00_0012 ,19445.7
     647     880     987    1304
River Rch & RM=P140-00-00,P140-00-00_0012 ,18730.9
     615     791     866    1075
River Rch & RM=P140-00-00,P140-00-00_0012 ,18451.3
     603     761     826    1002
River Rch & RM=P140-00-00,P140-00-00_0012 ,18062.2
     592     732     787     933
River Rch & RM=P140-00-00,P140-00-00_0012 ,17175.8
     562     655     688     764
River Rch & RM=P140-00-00,P140-00-00_0012 ,16411.8
     540     603     622     658
River Rch & RM=P140-00-00,P140-00-00_0012 ,15932.8
     168     197     204     216
River Rch & RM=P140-00-00,P140-00-00_0012 ,15630.7
     199     240     252     276
River Rch & RM=P140-00-00,P140-00-00_0012 ,15039.5
     243     301     321     365
River Rch & RM=P140-00-00,P140-00-00_0012 ,14356.7
     272     344     370     429
River Rch & RM=P140-00-00,P140-00-00_0012 ,13960.9
     307     394     428     508
River Rch & RM=P140-00-00,P140-00-00_0012 ,13549.3
     341     446     488     591
River Rch & RM=P140-00-00,P140-00-00_0012 ,13182.7
     474     651     730     942
River Rch & RM=P140-00-00,P140-00-00_0012 ,12048.6
     604     861     983    1328
River Rch & RM=P140-00-00,P140-00-00_0012 ,11211.8
     802    1160    1332    1822
River Rch & RM=P140-00-00,P140-00-00_0012 ,10218.3
     812    1174    1348    1846
River Rch & RM=P140-00-00,P140-00-00_0012 ,9242.9
     823    1190    1368    1874
River Rch & RM=P140-00-00,P140-00-00_0012 ,8106.4
     828    1199    1378    1888
River Rch & RM=P140-00-00,P140-00-00_0012 ,7536.4
     937    1365    1572    2166
River Rch & RM=P140-00-00,P140-00-00_0012 ,6761.4
     969    1411    1626    2240
River Rch & RM=P140-00-00,P140-00-00_0012 ,6064
    1028    1496    1724    2376
River Rch & RM=P140-00-00,P140-00-00_0012 ,4850.2
    1062    1555    1796    2489
River Rch & RM=P140-00-00,P140-00-00_0012 ,4176.8
    1410    2092    2429    3411
River Rch & RM=P140-00-00,P140-00-00_0012 ,4154.8
    1490    2211    2567    3604
River Rch & RM=P140-00-00,P140-00-00_0012 ,2895
    1552    2303    2675    3756
River Rch & RM=P140-00-00,P140-00-00_0012 ,1955.7
    1642    2454    2858    4041
Boundary for River Rch & Prof#=P140-00-00,P140-00-00_0012 , 1
Up Type= 0
Dn Type= 3
Dn Slope=0.0028
Boundary for River Rch & Prof#=P140-00-00,P140-00-00_0012 , 2
Up Type= 0
Dn Type= 3
Dn Slope=0.0028
Boundary for River Rch & Prof#=P140-00-00,P140-00-00_0012 , 3
Up Type= 0
Dn Type= 3
Dn Slope=0.0028
Boundary for River Rch & Prof#=P140-00-00,P140-00-00_0012 , 4
Up Type= 0
Dn Type= 3
Dn Slope=0.0028
DSS Import GetInterval= 0
DSS Import GetPeak= 0
DSS Import FillOption= 0

--- P140-00-00.f02 (steady flow) ---

Flow Title=Effective Floodway 2018
Program Version=4.10
Number of Profiles= 2
Profile Names=1PCT_100yr, 1PCTFloodway_100yrFW
River Rch & RM=P140-00-00,P140-00-00_0012 ,28661.6
     466     466
River Rch & RM=P140-00-00,P140-00-00_0012 ,28443.3
     493     493
River Rch & RM=P140-00-00,P140-00-00_0012 ,28254.9
     600     600
River Rch & RM=P140-00-00,P140-00-00_0012 ,27580.7
     693     693
River Rch & RM=P140-00-00,P140-00-00_0012 ,27092.3
     750     750
River Rch & RM=P140-00-00,P140-00-00_0012 ,26824.1
     791     791
River Rch & RM=P140-00-00,P140-00-00_0012 ,26629.5
     823     823
River Rch & RM=P140-00-00,P140-00-00_0012 ,25914.5
     842     842
River Rch & RM=P140-00-00,P140-00-00_0012 ,25427.8
     882     882
River Rch & RM=P140-00-00,P140-00-00_0012 ,24433.8
     924     924
River Rch & RM=P140-00-00,P140-00-00_0012 ,23413.6
     972     972
River Rch & RM=P140-00-00,P140-00-00_0012 ,22492.3
    1001    1001
River Rch & RM=P140-00-00,P140-00-00_0012 ,21685
    1048    1048
River Rch & RM=P140-00-00,P140-00-00_0012 ,20703.5
    1073    1073
River Rch & RM=P140-00-00,P140-00-00_0012 ,19445.7
     987     987
River Rch & RM=P140-00-00,P140-00-00_0012 ,18730.9
     866     866
River Rch & RM=P140-00-00,P140-00-00_0012 ,18451.3
     826     826
River Rch & RM=P140-00-00,P140-00-00_0012 ,18062.2
     787     787
River Rch & RM=P140-00-00,P140-00-00_0012 ,17175.8
     688     688
River Rch & RM=P140-00-00,P140-00-00_0012 ,16411.8
     622     622
River Rch & RM=P140-00-00,P140-00-00_0012 ,15932.8
     204     204
River Rch & RM=P140-00-00,P140-00-00_0012 ,15630.7
     252     252
River Rch & RM=P140-00-00,P140-00-00_0012 ,15039.5
     321     321
River Rch & RM=P140-00-00,P140-00-00_0012 ,14356.7
     370     370
River Rch & RM=P140-00-00,P140-00-00_0012 ,13960.9
     428     428
River Rch & RM=P140-00-00,P140-00-00_0012 ,13549.3
     488     488
River Rch & RM=P140-00-00,P140-00-00_0012 ,13182.7
     730     730
River Rch & RM=P140-00-00,P140-00-00_0012 ,12048.6
     983     983
River Rch & RM=P140-00-00,P140-00-00_0012 ,11211.8
    1332    1332
River Rch & RM=P140-00-00,P140-00-00_0012 ,10218.3
    1348    1348
River Rch & RM=P140-00-00,P140-00-00_0012 ,9242.9
    1368    1368
River Rch & RM=P140-00-00,P140-00-00_0012 ,8106.4
    1378    1378
River Rch & RM=P140-00-00,P140-00-00_0012 ,7536.4
    1572    1572
River Rch & RM=P140-00-00,P140-00-00_0012 ,6761.4
    1626    1626
River Rch & RM=P140-00-00,P140-00-00_0012 ,6064
    1724    1724
River Rch & RM=P140-00-00,P140-00-00_0012 ,4850.2
    1796    1796
River Rch & RM=P140-00-00,P140-00-00_0012 ,4176.8
    2429    2429
River Rch & RM=P140-00-00,P140-00-00_0012 ,4154.8
    2567    2567
River Rch & RM=P140-00-00,P140-00-00_0012 ,2895
    2675    2675
River Rch & RM=P140-00-00,P140-00-00_0012 ,1955.7
    2858    2858
Boundary for River Rch & Prof#=P140-00-00,P140-00-00_0012 , 1
Up Type= 0
Dn Type= 3
Dn Slope=0.0028
Boundary for River Rch & Prof#=P140-00-00,P140-00-00_0012 , 2
Up Type= 0
Dn Type= 1
Dn Known WS=65.59
DSS Import GetInterval= 0
DSS Import GetPeak= 0
DSS Import FillOption= 0

--- P140-00-00.g01 (geometry) ---

Geom Title=P140-00-00 2018
Program Version=4.10

River Reach=P140-00-00      ,P140-00-00_0012
Reach XY= 30
 3111529.107830913924263.1522994 3111524.199704213923841.0094429
 3111530.432303313923775.0249948  3111581.46271313923682.0018869
 3111667.427436113923595.9741718 3112016.922800113923372.0116932
 3112558.9482909 13922875.023842  3112609.436707 13922821.996389
 3112643.424171813922668.9796347 3112707.172403913921361.0140748
 3112768.470837713919331.9840121 3112825.1961179 13918623.969352
 3112932.455417913916491.9516344 3112993.039286213916379.2008757
 3113088.108649913916329.6520903 3113162.761387713916318.3673359
  3114331.89028313916336.5598848       3119494.5       13916573.
       3119627.5       13916563.      3119698.25       13916587.
      3121853.75       13916685.        3121912.       13916645.
      3121943.75       13915917.       3121974.5       13915770.
      3122077.25       13915573.      3122287.06     13915406.27
       3123912.5       13915458.        3124012.       13915422.
       3124030.5       13915389.       3124424.5       13907336.

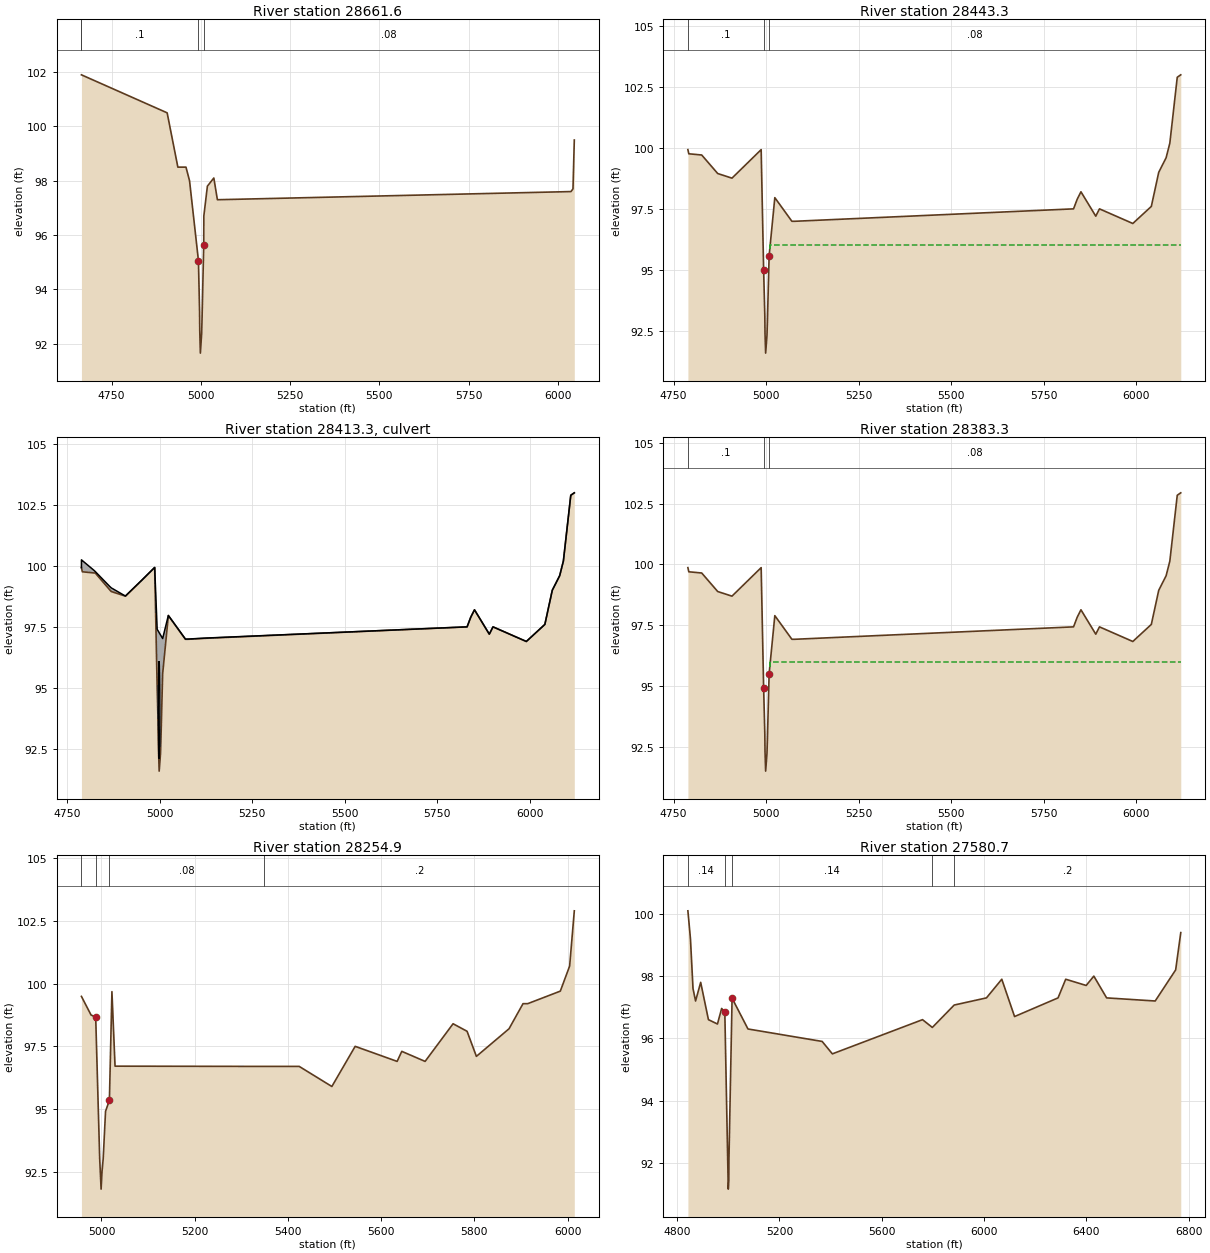
Type RM Length L Ch R = 1 ,28661.6 ,215.9,218.3,242.6
BEGIN DESCRIPTION:
Cross Section 28692.6-Interpolated
END DESCRIPTION:
XS GIS Cut Line= 4
       3111863.5     13924262.87      3111580.82     13924262.87
      3111492.78     13924262.87      3110483.48     13924267.52
#Sta/Elev= 19
  4665.7   101.9  4905.7   100.5  4935.7    98.5  4958.4    98.5  4968.4      98
  4993.3   95.06  4996.5   93.18    4997   92.48  4998.7   91.65  5002.3   92.37
  5003.5   92.96  5008.1   95.64  5008.4    96.7  5018.4    97.8  5036.4    98.1
  5046.4    97.3  6036.4    97.6    6042    97.7  6045.7    99.5
#Mann= 4 , 1 , 0
  4665.7      .2       0  4665.7      .1       0  4993.3     .04       0
  5008.1     .08       0
Bank Sta=4993.3,5008.1
XS Rating Curve= 0 ,0
Exp/Cntr=0.5,0.3

Type RM Length L Ch R = 1 ,28443.3 ,60,60,60
BEGIN DESCRIPTION:
Upstream Section of Bridge/Culvert/Weir
END DESCRIPTION:
XS GIS Cut Line= 5
      3111741.43     13924040.99      3111641.25     13924040.15
      3111463.12     13924042.59      3111372.15     13924041.68
      3110413.13      13923972.8
#Sta/Elev= 28
  4788.8   99.93  4791.2   99.76  4826.1   99.71  4869.3   98.95  4907.8   98.76
  4986.6   99.93  4993.3   94.99  4996.5   93.11    4997   92.41  4998.7   91.58
  5002.3    92.3  5003.5   92.89  5008.1   95.57  5023.5   97.96  5069.6   96.99
  5076.6   96.99  5830.1    97.5  5840.1    97.9  5850.1    98.2  5890.1    97.2
  5900.1    97.5  5990.1    96.9  6040.1    97.6  6060.1      99  6080.1    99.6
  6090.1   100.2  6110.1   102.9  6119.6     103
#Mann= 3 , 1 , 0
  4788.8      .1       0  4993.3     .04       0  5008.1     .08       0
#XS Ineff= 2 , 0
       0    4986    97.3    5010       0      96
Permanent Ineff=
       F       F
Bank Sta=4993.3,5008.1
XS Rating Curve= 0 ,0
Exp/Cntr=0.5,0.3

Type RM Length L Ch R = 2 ,28413.3 ,,,
BEGIN DESCRIPTION:
Access Road 7
Structure ID: P40-16
END DESCRIPTION:
Bridge Culvert--1,0,-1,-1, 0
Deck Dist Width WeirC Skew NumUp NumDn MinLoCord MaxHiCord MaxSubmerge Is_Ogee
10,40,3,0, 36, 36, , , 0.95, 0, 1,1,,
  4788.8  4788.9  4791.2  4823.4  4826.1  4865.1  4869.3  4905.7  4907.8  4951.9
  4985.1  4986.6  4993.3  4996.5    4997  4998.7  5002.3  5003.5  5008.1  5023.5
  5029.7  5069.6  5076.6  5123.6  5830.1  5840.1  5850.1  5890.1  5900.1  5990.1
  6040.1  6060.1  6080.1  6090.1  6110.1  6119.6
   99.93  100.25  100.22   99.81   99.77   99.16    99.1   98.78   98.77   99.42
   99.92   99.94    97.4   97.32   97.31   97.26   97.17   97.14   97.02   97.97
   97.84      97      97   97.04    97.5    97.9    98.2    97.2    97.5    96.9
    97.6      99    99.6   100.2   102.9     103
   99.93   99.92   99.76   99.71   99.71   99.02   98.95   98.77   98.76   99.41
   99.91   99.93   94.99   93.11   92.41   91.58    92.3   92.89   95.57   97.96
   97.83   96.99   96.99   97.03    97.5    97.9    98.2    97.2    97.5    96.9
    97.6      99    99.6   100.2   102.9     103
  4788.8  4788.9  4791.2  4823.4  4826.1  4865.1  4869.3  4905.7  4907.8  4951.9
  4985.1  4986.6  4993.3  4996.5    4997  4998.7  5002.3  5003.5  5008.1  5023.5
  5029.7  5069.6  5076.6  5123.6  5830.1  5840.1  5850.1  5890.1  5900.1  5990.1
  6040.1  6060.1  6080.1  6090.1  6110.1  6119.6
   99.93  100.25  100.22   99.81   99.77   99.16    99.1   98.78   98.77   99.42
   99.92   99.94    97.4   97.32   97.31   97.26   97.17   97.14   97.02   97.97
   97.84      97      97   97.04    97.5    97.9    98.2    97.2    97.5    96.9
    97.6      99    99.6   100.2   102.9     103
   99.85   99.84   99.68   99.63   99.63   98.94   98.87   98.69   98.68   99.33
   99.83   99.85   94.91   93.03   92.33    91.5   92.22   92.81   95.49   97.88
   97.75   96.91   96.91   96.95   97.42   97.82   98.12   97.12   97.42   96.82
   97.52   98.92   99.52  100.12  102.82  102.92
BR Coef= 1 , 0 , 0 ,1.25, 0 ,,,0.8,-1,2,0,
WSPro=,,,, 1 ,,,, 0 ,,,, 0 ,,,,-1 ,-1 ,-1 , 0 , 0 , 0 , 0 , 0
Culvert=1,4,,40,0.015,0.5,1,1,3,92.09,4998.4,92,4998.4,Culvert #1  , 0 ,10
Culvert Bottom n=0.015
BR U #Sta/Elev= 36
  4788.8   99.93  4788.9   99.92  4791.2   99.76  4823.4   99.71  4826.1   99.71
  4865.1   99.02  4869.3   98.95  4905.7   98.77  4907.8   98.76  4951.9   99.41
  4985.1   99.91  4986.6   99.93  4993.3   94.99  4996.5   93.11    4997   92.41
  4998.7   91.58  5002.3    92.3  5003.5   92.89  5008.1   95.57  5023.5   97.96
  5029.7   97.83  5069.6   96.99  5076.6   96.99  5123.6   97.03  5830.1    97.5
  5840.1    97.9  5850.1    98.2  5890.1    97.2  5900.1    97.5  5990.1    96.9
  6040.1    97.6  6060.1      99  6080.1    99.6  6090.1   100.2  6110.1   102.9
  6119.6     103
BR U #Mann= 3
  4788.8      .1  4993.3     .04  5008.1     .08
BR U Banks=4993.3,5008.1
BR D #Sta/Elev= 36
  4788.8   99.85  4788.9   99.84  4791.2   99.68  4823.4   99.63  4826.1   99.63
  4865.1   98.94  4869.3   98.87  4905.7   98.69  4907.8   98.68  4951.9   99.33
  4985.1   99.83  4986.6   99.85  4993.3   94.91  4996.5   93.03    4997   92.33
  4998.7    91.5  5002.3   92.22  5003.5   92.81  5008.1   95.49  5023.5   97.88
  5029.7   97.75  5069.6   96.91  5076.6   96.91  5123.6   96.95  5830.1   97.42
  5840.1   97.82  5850.1   98.12  5890.1   97.12  5900.1   97.42  5990.1   96.82
  6040.1   97.52  6060.1   98.92  6080.1   99.52  6090.1  100.12  6110.1  102.82
  6119.6  102.92
BR D #Mann= 3
  4788.8      .1  4993.3     .04  5008.1     .08
BR D Banks=4993.3,5008.1
BC Design=,, 0 ,, 0 ,,,,,,
BC HTab HWMax=103
BC Use User HTab Curves=0
BC User HTab FreeFlow(D)= 0

Type RM Length L Ch R = 1 ,28383.3 ,128.4,128.4,128.4
BEGIN DESCRIPTION:
Downstream Section of Bridge/Culvert/Weir
END DESCRIPTION:
XS GIS Cut Line= 5
      3111741.73     13923980.99      3111641.55     13923980.15
      3111463.42     13923982.59      3111372.45     13923981.68
      3110413.42     13923912.81
#Sta/Elev= 28
  4788.8   99.87  4791.2    99.7  4826.1   99.65  4869.3   98.89  4907.8    98.7
  4986.6   99.87  4993.3   94.93  4996.5   93.05    4997   92.35  4998.7   91.52
  5002.3   92.24  5003.5   92.83  5008.1   95.51  5023.5    97.9  5069.6   96.93
  5076.6   96.93  5830.1   97.44  5840.1   97.84  5850.1   98.14  5890.1   97.14
  5900.1   97.44  5990.1   96.84  6040.1   97.54  6060.1   98.94  6080.1   99.54
  6090.1  100.14  6110.1  102.84  6119.6  102.94
#Mann= 3 , 1 , 0
  4788.8      .1       0  4993.3     .04       0  5008.1     .08       0
#XS Ineff= 2 , 0
       0    4986    97.2    5010       0      96
Permanent Ineff=
       F       F
Bank Sta=4993.3,5008.1
XS Rating Curve= 0 ,0
Exp/Cntr=0.5,0.3

Type RM Length L Ch R = 1 ,28254.9 ,638.7,674.2,703.4
BEGIN DESCRIPTION:
Cross Section 28285.9
END DESCRIPTION:
XS GIS Cut Line= 4
       3111567.3     13923860.17      3111481.43     13923852.37
      3111258.68     13923736.97       3110562.6     13923552.87
#Sta/Elev= 27
  4957.1   99.49  4977.7   98.75  4987.7   98.66  4996.3   93.01  4999.3   91.81
  5001.3   92.52  5003.8   93.03  5008.8   94.91  5017.1   95.35  5022.5   99.68
  5029.2   96.71  5349.6    96.7  5424.2    96.7  5494.2    95.9  5544.2    97.5
  5634.2    96.9  5644.2    97.3  5694.2    96.9  5754.2    98.4  5784.2    98.1
  5804.2    97.1  5874.2    98.2  5904.2    99.2  5914.2    99.2  5984.2    99.7
  6004.2   100.7  6014.2   102.9
#Mann= 4 , 1 , 0
  4957.1      .1       0  4987.7     .04       0  5017.1     .08       0
  5349.6      .2       0
#XS Ineff= 2 , 0
       0                  5754.2       0    98.4
Permanent Ineff=
       F       F
Bank Sta=4987.7,5017.1
XS Rating Curve= 0 ,0
Exp/Cntr=0.3,0.1

Type RM Length L Ch R = 1 ,27580.7 ,382.9,379.1,324.8
BEGIN DESCRIPTION:
Cross Section 27611.7
END DESCRIPTION:
XS GIS Cut Line= 5
      3112048.94     13923539.43      3112023.54     13923463.23
      3111926.93     13923342.46      3111652.88     13923136.82
      3110374.19     13922703.88
#Sta/Elev= 30
  4841.9   100.1  4851.9    99.2  4861.9    97.6  4871.9    97.2  4891.9    97.8
  4922.2    96.6  4957.5   96.46  4973.9   96.96  4986.3   96.84  4999.8   91.15
  5001.9   91.42  5002.4   92.09  5014.7   97.29  5076.9    96.3  5366.9    95.9
  5406.9    95.5  5759.5    96.6  5797.9   96.35  5883.4   97.07  6009.5    97.3
  6069.5    97.9  6119.5    96.7  6289.5    97.3  6319.5    97.9  6399.5    97.7
  6429.5      98  6479.5    97.3  6669.5    97.2  6749.5    98.2  6769.5    99.4
#Mann= 5 , 1 , 0
  4841.9     .14       0  4986.3     .05       0  5014.7     .14       0
  5797.9     .07       0  5883.4      .2       0
#XS Ineff= 2 , 0
       0  4891.9    97.8  6069.5       0    97.9
Permanent Ineff=
       F       F
Bank Sta=4986.3,5014.7
XS Rating Curve= 0 ,0
Exp/Cntr=0.3,0.1

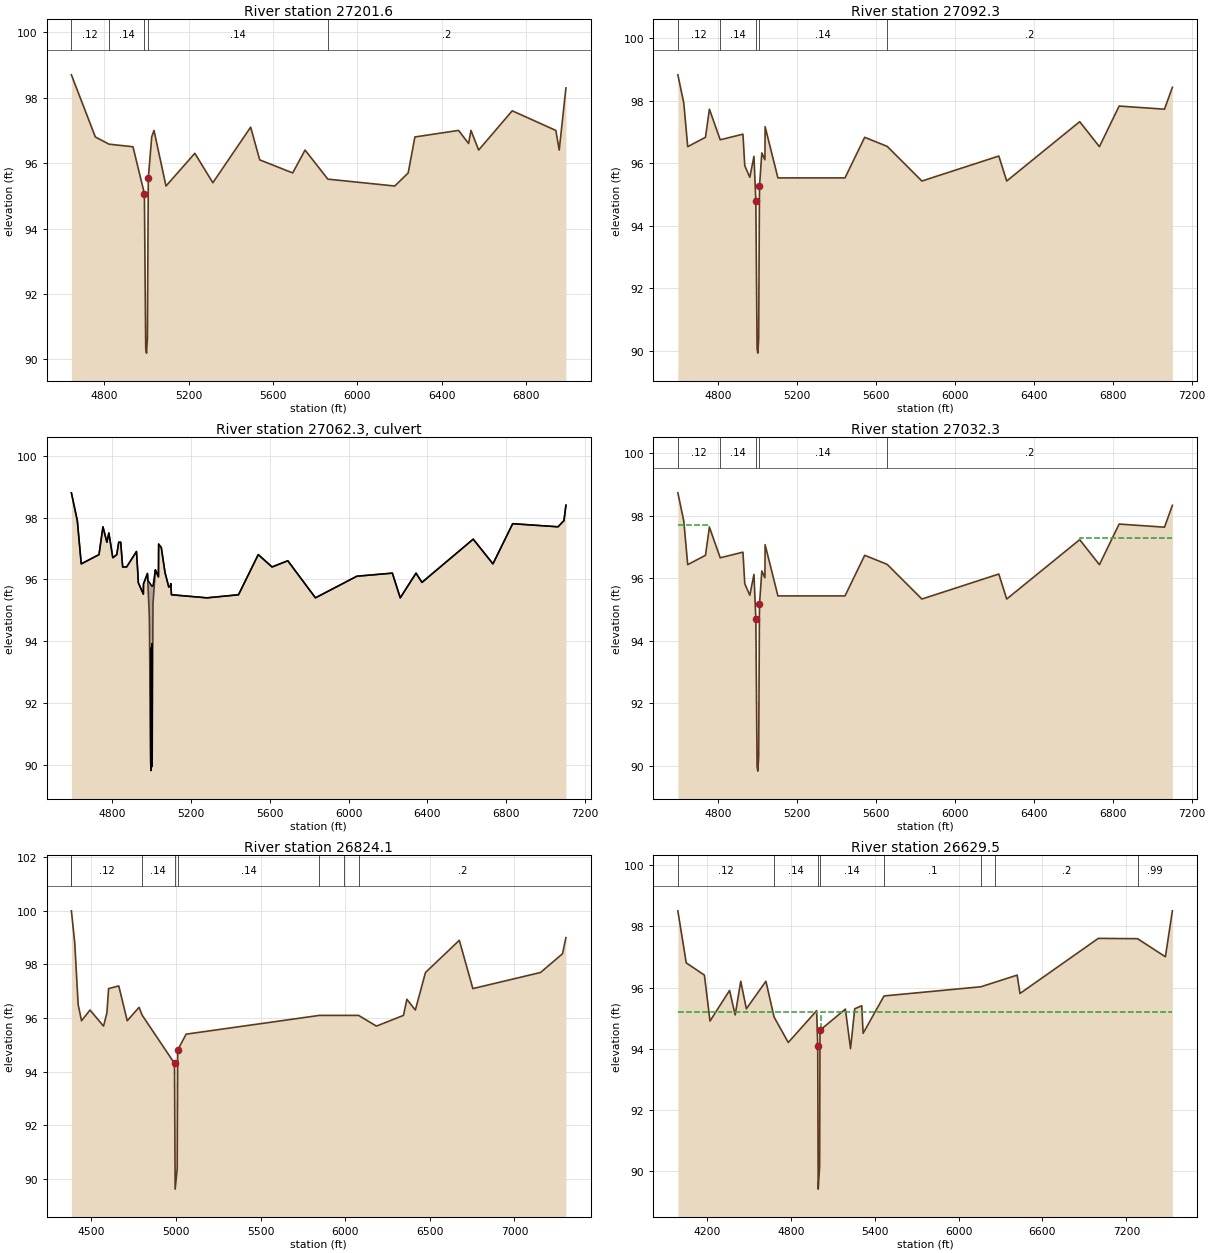
Type RM Length L Ch R = 1 ,27201.6 ,96.1,109.3,138.9
BEGIN DESCRIPTION:
Cross Section 27232.6-Interpolated
END DESCRIPTION:
XS GIS Cut Line= 5
      3112471.31     13923427.54      3112299.11     13923191.57
      3112233.03     13923125.48       3111737.4     13922854.54
      3110422.53     13922387.17
#Sta/Elev= 30
  4643.7    98.7  4757.4    96.8  4821.9   96.58  4935.8    96.5    4990   95.07
  4996.3   90.34  5000.1   90.19  5004.3   90.65  5008.5   95.53  5024.7    96.8
  5035.5      97  5092.5    95.3  5229.3    96.3  5314.8    95.4  5494.1    97.1
    5537    96.1  5693.5    95.7  5752.2    96.4  5860.4   95.51  6177.7    95.3
  6241.4    95.7  6273.2    96.8  6480.4      97  6527.9    96.6  6539.1      97
  6575.7    96.4  6734.9    97.6  6941.8      97  6957.8    96.4  6989.6    98.3
#Mann= 5 , 1 , 0
  4643.7     .12       0  4821.9     .14       0    4990     .05       0
  5008.5     .14       0  5860.4      .2       0
#XS Ineff= 2 , 0
       0                  6734.9       0    97.6
Permanent Ineff=
       F       F
Bank Sta=4990,5008.5
XS Rating Curve= 0 ,0
Exp/Cntr=0.5,0.3

Type RM Length L Ch R = 1 ,27092.3 ,60,60,60
BEGIN DESCRIPTION:
Upstream Section of Bridge/Culvert/Weir
END DESCRIPTION:
XS GIS Cut Line= 5
      3112532.16     13923422.86      3112372.71     13923128.19
       3112331.2     13923065.93      3112271.06     13922987.96
        3110459.     13922143.76
#Sta/Elev= 30
  4594.6   98.83  4624.6   97.93  4644.6   96.53  4734.6   96.83  4754.6   97.73
  4809.4   96.75  4924.6   96.93  4933.9   95.92  4959.5   95.55  4980.4   96.22
    4990    94.8  4996.3   90.07  5000.1   89.92  5004.3   90.38  5008.5   95.26
  5020.4   96.33    5036   96.11    5037   97.17    5102   95.53    5442   95.53
    5542   96.83  5655.9   96.54    5832   95.43    6222   96.23    6262   95.43
    6632   97.33    6732   96.53    6832   97.83    7062   97.73    7102   98.43
#Mann= 5 , 1 , 0
  4594.6     .12       0  4809.4     .14       0    4990     .05       0
  5008.5     .14       0  5655.9      .2       0
#XS Ineff= 2 , 0
       0  4754.6    97.7    6632       0    97.3
Permanent Ineff=
       F       F
Bank Sta=4990,5008.5
XS Rating Curve= 0 ,0
Exp/Cntr=0.5,0.3

Type RM Length L Ch R = 2 ,27062.3 ,,,
BEGIN DESCRIPTION:
Unnamed Trail
Structure ID: P40-15
END DESCRIPTION:
Bridge Culvert--1,0,-1,-1, 0
Deck Dist Width WeirC Skew NumUp NumDn MinLoCord MaxHiCord MaxSubmerge Is_Ogee
10,40,3,0, 57, 57, , , 0.95, 0, 1,1,,
  4594.6  4624.6  4644.6  4734.6  4754.6  4774.6  4784.6  4804.6  4809.4  4824.6
  4834.6  4844.6  4854.6  4874.6  4924.6  4932.2  4933.9  4959.5  4960.1  4980.4
  4982.4    4990    4995  4996.3  5000.1  5002.4  5004.3  5005.1  5008.5  5020.4
  5023.2    5036    5037  5050.4  5069.3  5088.3  5098.2  5098.4    5102    5282
    5442    5542    5612  5655.9    5692    5832    6042    6222    6262    6342
    6372    6632    6732    6832    7062    7092    7102
    98.8    97.9    96.5    96.8    97.7    97.2    97.5    96.7   96.72    96.8
    97.2    97.2    96.4    96.4    96.9   96.13   95.89   95.52   95.85   96.19
   95.97    95.9   95.85   95.84    95.8   95.78   95.78   95.78   95.79   96.31
   96.27   96.08   97.14   97.03   96.22   95.75    95.8   95.86    95.5    95.4
    95.5    96.8    96.4   96.51    96.6    95.4    96.1    96.2    95.4    96.2
    95.9    97.3    96.5    97.8    97.7    97.9    98.4
    98.8    97.9    96.5    96.8    97.7    97.2    97.5    96.7   96.72    96.8
    97.2    97.2    96.4    96.4    96.9   96.13   95.89   95.52   95.85   96.19
   95.89   94.77    91.1   90.04   89.89   90.14   90.35   91.42   95.23    96.3
   96.26   96.08   97.14   97.03   96.22   95.75    95.8   95.86    95.5    95.4
    95.5    96.8    96.4   96.51    96.6    95.4    96.1    96.2    95.4    96.2
    95.9    97.3    96.5    97.8    97.7    97.9    98.4
  4594.6  4624.6  4644.6  4734.6  4754.6  4774.6  4784.6  4804.6  4809.4  4824.6
  4834.6  4844.6  4854.6  4874.6  4924.6  4932.2  4933.9  4959.5  4960.1  4980.4
  4982.4    4990    4995  4996.3  5000.1  5002.4  5004.3  5005.1  5008.5  5020.4
  5023.2    5036    5037  5050.4  5069.3  5088.3  5098.2  5098.4    5102    5282
    5442    5542    5612  5655.9    5692    5832    6042    6222    6262    6342
    6372    6632    6732    6832    7062    7092    7102
    98.8    97.9    96.5    96.8    97.7    97.2    97.5    96.7   96.72    96.8
    97.2    97.2    96.4    96.4    96.9   96.13   95.89   95.52   95.85   96.19
   95.97    95.9   95.85   95.84    95.8   95.78   95.78   95.78   95.79   96.31
   96.27   96.08   97.14   97.03   96.22   95.75    95.8   95.86    95.5    95.4
    95.5    96.8    96.4   96.51    96.6    95.4    96.1    96.2    95.4    96.2
    95.9    97.3    96.5    97.8    97.7    97.9    98.4
   98.75   97.85   96.45   96.75   97.65   97.15   97.45   96.65   96.67   96.75
   97.15   97.15   96.35   96.35   96.85   96.08   95.84   95.47    95.8   96.14
   95.84   94.72   91.05   89.99   89.84   90.09    90.3   91.37   95.18   96.25
   96.21   96.03   97.09   96.98   96.17    95.7   95.75   95.81   95.45   95.35
   95.45   96.75   96.35   96.46   96.55   95.35   96.05   96.15   95.35   96.15
   95.85   97.25   96.45   97.75   97.65   97.85   98.35
BR Coef= 1 , 0 , 0 ,1.25, 0 ,,,0.8,-1,2,0,
WSPro=,,,, 1 ,,,, 0 ,,,, 0 ,,,,-1 ,-1 ,-1 , 0 , 0 , 0 , 0 , 0
Culvert=1,4,,40,0.024,0.5,1,1,3,89.79,4997.6,89.69,4997.6,Culvert #1  , 0 ,10
Culvert Bottom n=0.024
Culvert=1,4,,40,0.024,0.5,1,1,3,89.93,5002.5,89.84,5002.5,Culvert #2  , 0 ,10
Culvert Bottom n=0.024
BR U #Sta/Elev= 57
  4594.6    98.8  4624.6    97.9  4644.6    96.5  4734.6    96.8  4754.6    97.7
  4774.6    97.2  4784.6    97.5  4804.6    96.7  4809.4   96.72  4824.6    96.8
  4834.6    97.2  4844.6    97.2  4854.6    96.4  4874.6    96.4  4924.6    96.9
  4932.2   96.13  4933.9   95.89  4959.5   95.52  4960.1   95.85  4980.4   96.19
  4982.4   95.89    4990   94.77    4995    91.1  4996.3   90.04  5000.1   89.89
  5002.4   90.14  5004.3   90.35  5005.1   91.42  5008.5   95.23  5020.4    96.3
  5023.2   96.26    5036   96.08    5037   97.14  5050.4   97.03  5069.3   96.22
  5088.3   95.75  5098.2    95.8  5098.4   95.86    5102    95.5    5282    95.4
    5442    95.5    5542    96.8    5612    96.4  5655.9   96.51    5692    96.6
    5832    95.4    6042    96.1    6222    96.2    6262    95.4    6342    96.2
    6372    95.9    6632    97.3    6732    96.5    6832    97.8    7062    97.7
    7092    97.9    7102    98.4
BR U #Mann= 5
  4594.6     .12  4809.4     .14    4990     .05  5008.5     .14  5655.9      .2
BR U Banks=4990,5008.5
BR D #Sta/Elev= 57
  4594.6   98.75  4624.6   97.85  4644.6   96.45  4734.6   96.75  4754.6   97.65
  4774.6   97.15  4784.6   97.45  4804.6   96.65  4809.4   96.67  4824.6   96.75
  4834.6   97.15  4844.6   97.15  4854.6   96.35  4874.6   96.35  4924.6   96.85
  4932.2   96.08  4933.9   95.84  4959.5   95.47  4960.1    95.8  4980.4   96.14
  4982.4   95.84    4990   94.72    4995   91.05  4996.3   89.99  5000.1   89.84
  5002.4   90.09  5004.3    90.3  5005.1   91.37  5008.5   95.18  5020.4   96.25
  5023.2   96.21    5036   96.03    5037   97.09  5050.4   96.98  5069.3   96.17
  5088.3    95.7  5098.2   95.75  5098.4   95.81    5102   95.45    5282   95.35
    5442   95.45    5542   96.75    5612   96.35  5655.9   96.46    5692   96.55
    5832   95.35    6042   96.05    6222   96.15    6262   95.35    6342   96.15
    6372   95.85    6632   97.25    6732   96.45    6832   97.75    7062   97.65
    7092   97.85    7102   98.35
BR D #Mann= 5
  4594.6     .12  4809.4     .14    4990     .05  5008.5     .14  5655.9      .2
BR D Banks=4990,5008.5
BC Design=,, 0 ,, 0 ,,,,,,
BC HTab HWMax=98.83
BC Use User HTab Curves=0
BC User HTab FreeFlow(D)= 0

Type RM Length L Ch R = 1 ,27032.3 ,208.2,208.2,208.2
BEGIN DESCRIPTION:
Downstream Section of Bridge/Culvert/Weir
END DESCRIPTION:
XS GIS Cut Line= 5
      3112577.57     13923383.63      3112418.11     13923088.97
       3112376.6     13923026.71      3112316.46     13922948.74
       3110504.4     13922104.54
#Sta/Elev= 30
  4594.6   98.74  4624.6   97.84  4644.6   96.44  4734.6   96.74  4754.6   97.64
  4809.4   96.66  4924.6   96.84  4933.9   95.83  4959.5   95.46  4980.4   96.13
    4990   94.71  4996.3   89.98  5000.1   89.83  5004.3   90.29  5008.5   95.17
  5020.4   96.24    5036   96.02    5037   97.08    5102   95.44    5442   95.44
    5542   96.74  5655.9   96.45    5832   95.34    6222   96.14    6262   95.34
    6632   97.24    6732   96.44    6832   97.74    7062   97.64    7102   98.34
#Mann= 5 , 1 , 0
  4594.6     .12       0  4809.4     .14       0    4990     .05       0
  5008.5     .14       0  5655.9      .2       0
#XS Ineff= 2 , 0
       0  4754.6    97.7    6632       0    97.3
Permanent Ineff=
       F       F
Bank Sta=4990,5008.5
XS Rating Curve= 0 ,0
Exp/Cntr=0.5,0.3

Type RM Length L Ch R = 1 ,26824.1 ,165.2,194.6,377
BEGIN DESCRIPTION:
Cross Section 26855.1-Interpolated
END DESCRIPTION:
XS GIS Cut Line= 4
      3112794.96     13923442.63      3112660.57     13923025.56
      3112442.77     13922798.49       3110570.7     13921701.22
#Sta/Elev= 30
  4381.2     100  4401.2    98.8  4421.2    96.5  4441.2    95.9  4491.2    96.3
  4571.2    95.7  4591.2    96.2  4601.2    97.1  4661.2    97.2  4711.2    95.9
  4781.2    96.4  4799.4   96.11  4990.6   94.31  4994.5   89.62  5006.5   90.37
  5009.5   94.81  5059.4    95.4  5847.1    96.1  5994.4    96.1  6078.7    96.1
    6184    95.7    6344    96.1    6364    96.7    6414    96.3    6474    97.7
    6674    98.9    6754    97.1    7154    97.7    7284    98.4    7304      99
#Mann= 8 , 1 , 0
  4381.2      .2       0  4381.2     .12       0  4799.4     .14       0
  4990.6    .045       0  5009.5     .14       0  5847.1      .1       0
  5994.4     .14       0  6078.7      .2       0
#XS Ineff= 2 , 0
       0  4661.2    97.2    6674       0    98.9
Permanent Ineff=
       F       F
Bank Sta=4990.6,5009.5
XS Rating Curve= 0 ,0
Exp/Cntr=0.5,0.3

Type RM Length L Ch R = 1 ,26629.5 ,68,68,68
BEGIN DESCRIPTION:
Upstream Section of Bridge/Culvert/Weir
END DESCRIPTION:
XS GIS Cut Line= 5
       3113243.1     13923533.47      3113031.01     13923244.36
       3112758.2      13922900.3      3111664.81     13921543.57
      3110703.05     13921277.18
#Sta/Elev= 30
  3991.2   98.51  4051.2   96.81  4181.2   96.41  4221.2   94.91  4361.2   95.91
  4401.2   95.11  4441.2   96.21  4481.2   95.31  4621.2   96.21  4679.7   95.04
  4781.2   94.21 4984.33   95.25 4991.86   94.11 4995.24   89.42 5005.63   90.17
 5008.23   94.61 5189.65    95.3  5226.7   94.01  5256.7   95.31  5306.7   95.41
  5316.7   94.51  5466.5   95.73  6160.3   96.03  6261.9   96.18  6418.8   96.41
  6438.8   95.81  6999.3   97.61  7279.9    97.6  7479.3   97.01  7529.3   98.51
#Mann= 8 , 1 , 0
  3991.2     .12       0  4679.7     .14       0 4991.86     .04       0
 5008.23     .14       0  5466.5      .1       0  6160.3     .14       0
  6261.9      .2       0  7279.9     .99       0
#XS Ineff= 2 , 0
       0    4985    95.2    5016       0    95.2
Permanent Ineff=
       F       F
Bank Sta=4991.86,5008.23
XS Rating Curve= 0 ,0
Exp/Cntr=0.5,0.3