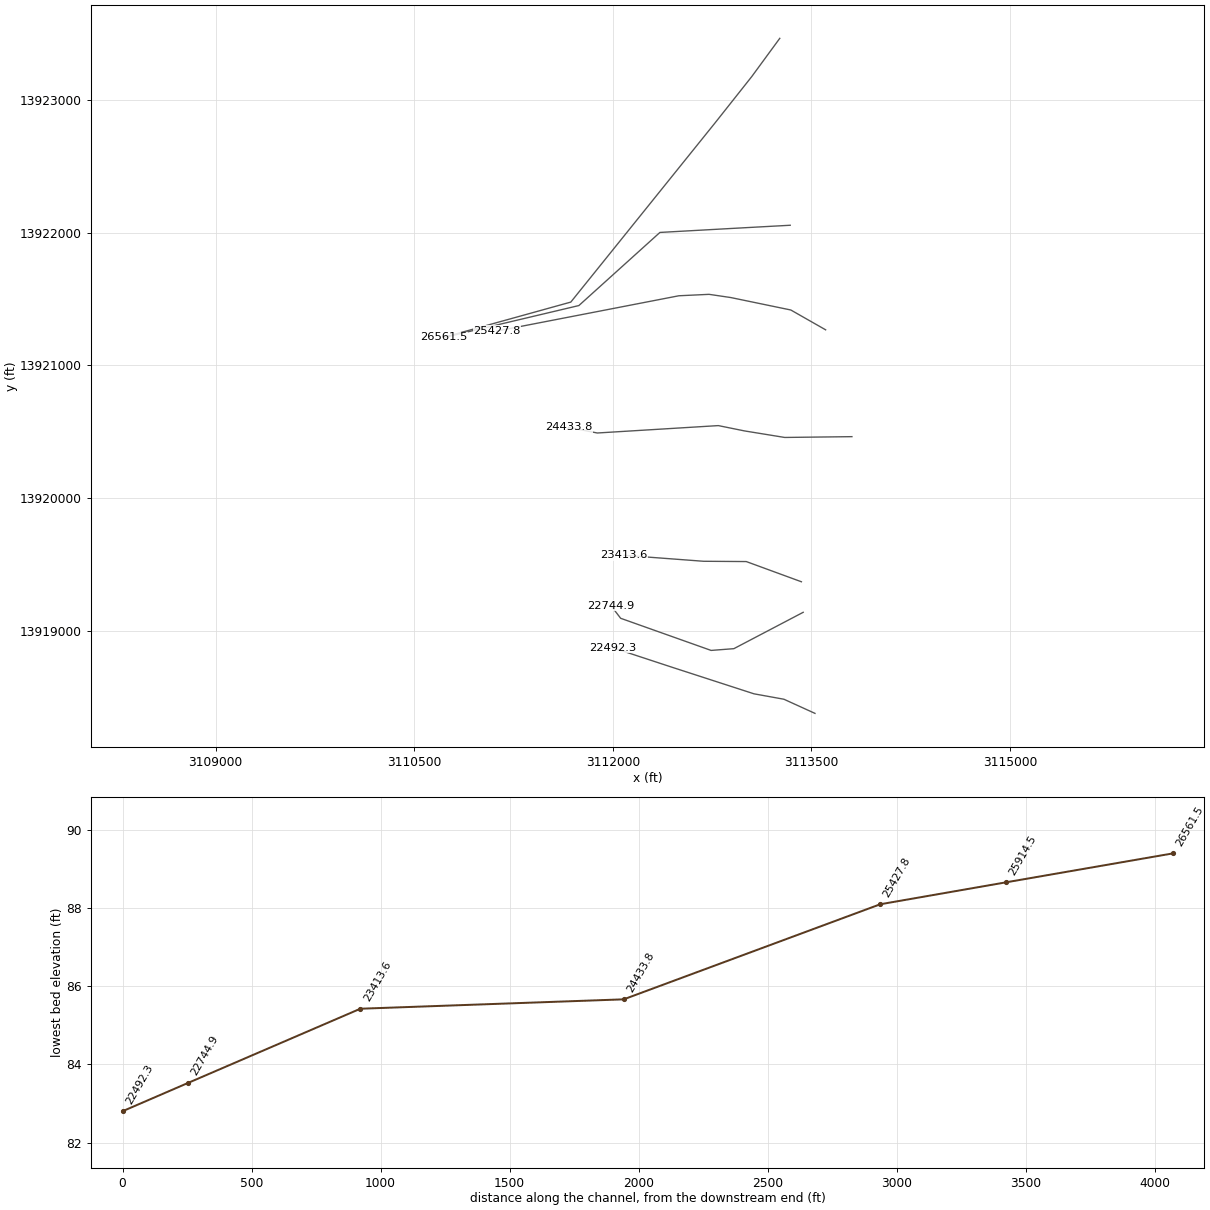
HEC-RAS study P140-00-00.prj: P140-00-00 (Hoods Bayou)

--- P140-00-00.g01 (geometry) --- (continued)

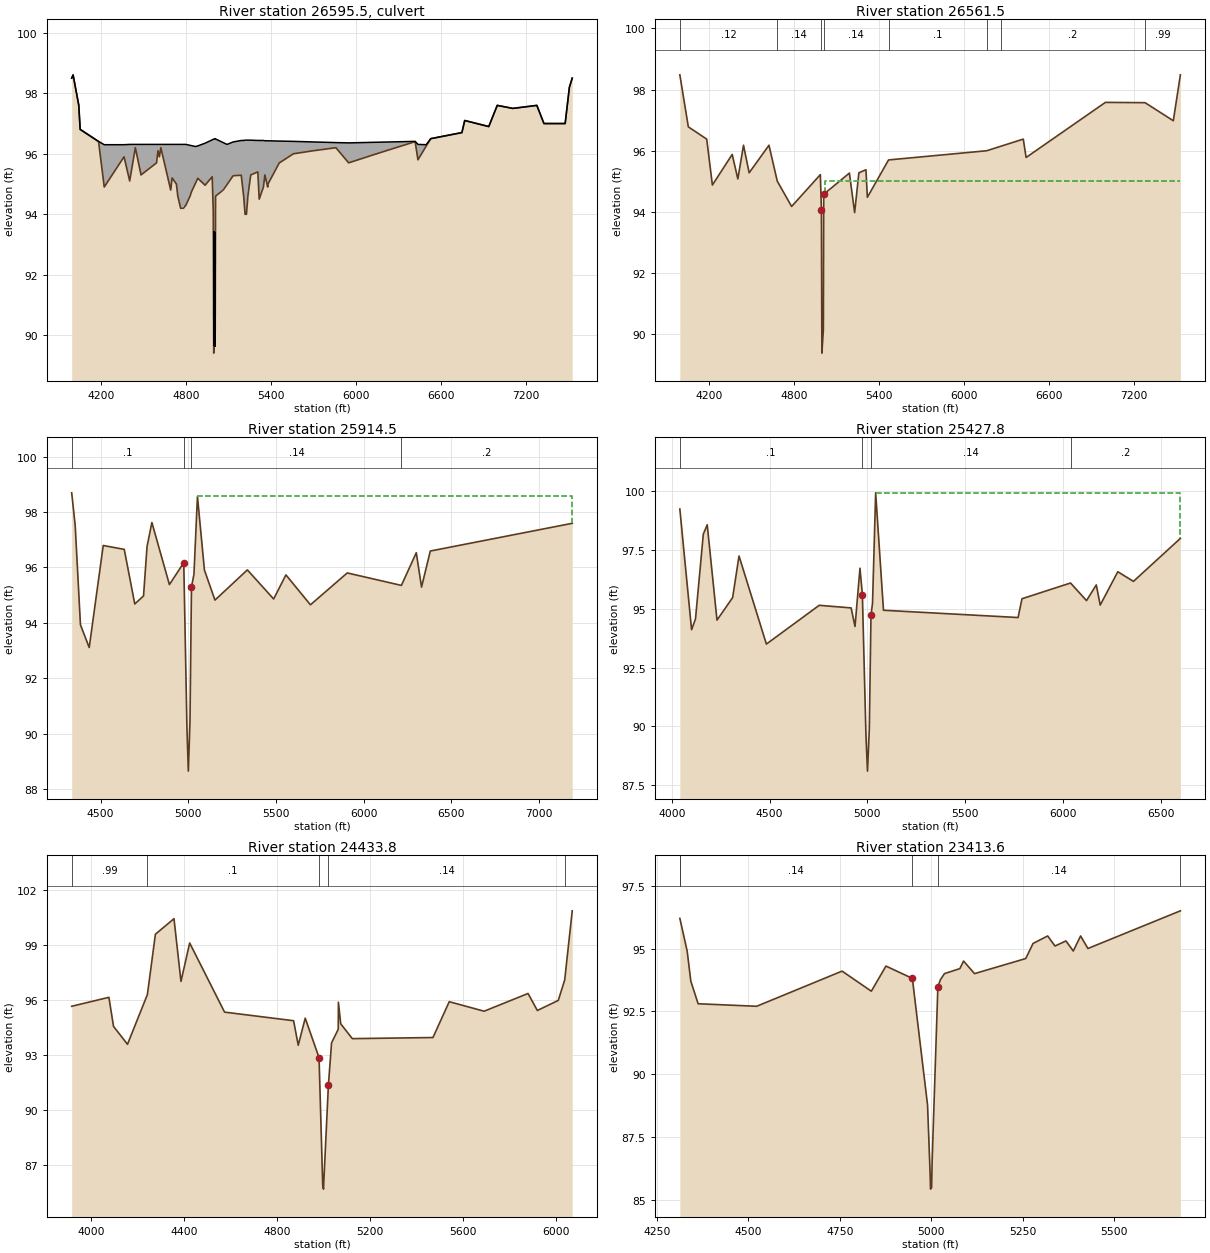
Type RM Length L Ch R = 2 ,26595.5 ,,,
BEGIN DESCRIPTION:
FARRELL ROAD, SKEW ANGLE OF 30 DEGREES
Structure ID: P40-14,,,,
END DESCRIPTION:
Bridge Culvert--1,0,-1,-1, 0
Deck Dist Width WeirC Skew NumUp NumDn MinLoCord MaxHiCord MaxSubmerge Is_Ogee
10,48,3,0, 60, 60, , , 0.95, 0, 1,1,,
  3991.2  4001.2  4041.2  4051.2  4181.2  4221.2  4361.2  4401.2  4441.2  4481.2
  4591.2  4601.2  4611.2  4621.2  4691.2  4701.2  4731.2  4741.2  4761.2  4798.2
  4866.7 4882.31  4934.1 4984.33 4991.86 4995.24 5004.33 5005.63 5008.23    5089
 5131.89 5189.65  5206.7  5216.7  5226.7  5236.7  5256.7  5306.7  5316.7  5346.7
  5356.7  5376.7  5458.8  5558.8  5858.8  5948.8  6418.8  6438.8  6496.6  6529.3
  6749.3  6769.3  6939.3  6999.3  7109.3  7279.3  7329.3  7479.3  7509.3  7529.3
    98.5   98.61   97.61   96.81   96.41    96.3    96.3   96.31   96.31   96.31
   96.31   96.31   96.31   96.31   96.31   96.31   96.31   96.31   96.31   96.31
   96.24   96.26   96.35   96.46   96.48   96.48    96.5   96.49   96.49   96.31
   96.39   96.44   96.44   96.45   96.45   96.45   96.45   96.44   96.44   96.44
   96.43   96.43   96.42   96.41   96.37   96.36   96.41   96.31    96.3    96.5
    96.7    97.1    96.9    97.6    97.5    97.6      97      97    98.2    98.5
    98.5    98.6    97.6    96.8    96.4    94.9    95.9    95.1    96.2    95.3
    95.7    96.1    95.9    96.2    94.8    95.2      95    94.6    94.2    94.3
   95.03   95.19   94.96   95.24    94.1   89.41   89.96   90.16    94.6   94.98
   95.27   95.29    94.6      94      94    94.6    95.3    95.4    94.5    94.9
    95.3    94.9    95.7      96    96.2    95.7    96.4    95.8   96.25    96.5
    96.7    97.1    96.9    97.6    97.5    97.6      97      97    98.2    98.5
  3991.2  4001.2  4041.2  4051.2  4181.2  4221.2  4361.2  4401.2  4441.2  4481.2
  4591.2  4601.2  4611.2  4621.2  4691.2  4701.2  4731.2  4741.2  4761.2  4798.2
  4866.7 4882.31  4934.1 4984.33 4991.86 4995.24 5004.33 5005.63 5008.23    5089
 5131.89 5189.65  5206.7  5216.7  5226.7  5236.7  5256.7  5306.7  5316.7  5346.7
  5356.7  5376.7  5458.8  5558.8  5858.8  5948.8  6418.8  6438.8  6496.6  6529.3
  6749.3  6769.3  6939.3  6999.3  7109.3  7279.3  7329.3  7479.3  7509.3  7529.3
    98.5   98.61   97.61   96.81   96.41    96.3    96.3   96.31   96.31   96.31
   96.31   96.31   96.31   96.31   96.31   96.31   96.31   96.31   96.31   96.31
   96.24   96.26   96.35   96.46   96.48   96.48    96.5   96.49   96.49   96.31
   96.39   96.44   96.44   96.45   96.45   96.45   96.45   96.44   96.44   96.44
   96.43   96.43   96.42   96.41   96.37   96.36   96.41   96.31    96.3    96.5
    96.7    97.1    96.9    97.6    97.5    97.6      97      97    98.2    98.5
   98.49   98.59   97.59   96.79   96.39   94.89   95.89   95.09   96.19   95.29
   95.69   96.09   95.89   96.19   94.79   95.19   94.99   94.59   94.19   94.29
   95.02   95.18   94.95   95.23   94.09    89.4   89.95   90.15   94.59   94.97
   95.26   95.28   94.59   93.99   93.99   94.59   95.29   95.39   94.49   94.89
   95.29   94.89   95.69   95.99   96.19   95.69   96.39   95.79   96.24   96.49
   96.69   97.09   96.89   97.59   97.49   97.59   96.99   96.99   98.19   98.49
BR Coef= 1 , 0 , 0 ,1.25, 0 ,,,0.8,-1,2,0,
WSPro=,,,, 1 ,,,, 0 ,,,, 0 ,,,,-1 ,-1 ,-1 , 0 , 0 , 0 , 0 , 0
Culvert=1,3.8,,48,0.015,0.5,1,1,3,89.65,4997.9,89.5,4997.9,Culvert #1  , 0 ,10
Culvert Bottom n=0.015
Culvert=1,3.8,,48,0.015,0.5,1,1,3,89.62,5003.6,89.46,5003.6,Culvert #2  , 0 ,10
Culvert Bottom n=0.015
BR U #Sta/Elev= 79
  3991.2    98.5  3996.6   98.55  4001.2    98.6  4041.2    97.6  4051.2    96.8
  4181.2    96.4  4221.2    94.9  4361.2    95.9  4401.2    95.1  4441.2    96.2
  4481.2    95.3  4591.2    95.7  4601.2    96.1  4611.2    95.9  4621.2    96.2
  4679.7   95.03  4691.2    94.8  4701.2    95.2  4731.2      95  4741.2    94.6
  4761.2    94.2  4781.2    94.2  4796.5   94.29  4798.2    94.3  4828.2    94.6
 4836.76   94.73  4866.7   95.03 4882.31   95.19  4921.1   95.02  4934.1   94.96
 4984.33   95.24 4991.86    94.1 4994.37   90.56 4995.24   89.41  5002.8   89.87
 5004.33   89.96 5005.63   90.16 5008.23    94.6  5040.3   94.72 5063.39   94.81
    5089   94.98 5131.89   95.27  5148.2   95.28 5189.65   95.29  5206.7    94.6
  5216.7      94    5220      94  5226.7      94  5236.7    94.6  5256.7    95.3
  5306.7    95.4  5316.7    94.5  5346.7    94.9  5356.7    95.3  5376.7    94.9
  5378.8      95  5458.8    95.7  5466.5   95.72  5558.8      96  5698.8    96.1
  5858.8    96.2  5948.8    95.7  6160.3   96.02  6261.9   96.17  6418.8    96.4
  6438.8    95.8  6496.6   96.25  6529.3    96.5  6749.3    96.7  6769.3    97.1
  6939.3    96.9  6999.3    97.6  7109.3    97.5  7279.3    97.6  7279.9   97.59
  7329.3      97  7479.3      97  7509.3    98.2  7529.3    98.5
BR U #Mann= 8
  3991.2     .12  4679.7     .14 4991.86     .04 5008.23     .14  5466.5      .1
  6160.3     .14  6261.9      .2  7279.9     .99
BR U Banks=4991.86,5008.23
BR D #Sta/Elev= 79
  3991.2   98.49  3996.6   98.54  4001.2   98.59  4041.2   97.59  4051.2   96.79
  4181.2   96.39  4221.2   94.89  4361.2   95.89  4401.2   95.09  4441.2   96.19
  4481.2   95.29  4591.2   95.69  4601.2   96.09  4611.2   95.89  4621.2   96.19
  4679.7   95.02  4691.2   94.79  4701.2   95.19  4731.2   94.99  4741.2   94.59
  4761.2   94.19  4781.2   94.19  4796.5   94.28  4798.2   94.29  4828.2   94.59
 4836.76   94.72  4866.7   95.02 4882.31   95.18  4921.1   95.01  4934.1   94.95
 4984.33   95.23 4991.86   94.09 4994.37   90.55 4995.24    89.4  5002.8   89.86
 5004.33   89.95 5005.63   90.15 5008.23   94.59  5040.3   94.71 5063.39    94.8
    5089   94.97 5131.89   95.26  5148.2   95.27 5189.65   95.28  5206.7   94.59
  5216.7   93.99    5220   93.99  5226.7   93.99  5236.7   94.59  5256.7   95.29
  5306.7   95.39  5316.7   94.49  5346.7   94.89  5356.7   95.29  5376.7   94.89
  5378.8   94.99  5458.8   95.69  5466.5   95.71  5558.8   95.99  5698.8   96.09
  5858.8   96.19  5948.8   95.69  6160.3   96.01  6261.9   96.16  6418.8   96.39
  6438.8   95.79  6496.6   96.24  6529.3   96.49  6749.3   96.69  6769.3   97.09
  6939.3   96.89  6999.3   97.59  7109.3   97.49  7279.3   97.59  7279.9   97.58
  7329.3   96.99  7479.3   96.99  7509.3   98.19  7529.3   98.49
BR D #Mann= 8
  3991.2     .12  4679.7     .14 4991.86     .04 5008.23     .14  5466.5      .1
  6160.3     .14  6261.9      .2  7279.9     .99
BR D Banks=4991.86,5008.23
BC Design=,, 0 ,, 0 ,,,,,,
BC HTab HWMax=98.61
BC Use User HTab Curves=0
BC User HTab FreeFlow(D)= 0

Type RM Length L Ch R = 1 ,26561.5 ,647,647,647
BEGIN DESCRIPTION:
Downstream Section of Bridge/Culvert/Weir
END DESCRIPTION:
XS GIS Cut Line= 5
      3113260.58     13923467.75      3113048.49     13923178.64
      3112775.68     13922834.58      3111682.29     13921477.85
      3110720.53     13921211.46
#Sta/Elev= 30
  3991.2   98.48  4051.2   96.78  4181.2   96.38  4221.2   94.88  4361.2   95.88
  4401.2   95.08  4441.2   96.18  4481.2   95.28  4621.2   96.18  4679.7   95.01
  4781.2   94.18 4984.33   95.22 4991.86   94.08 4995.24   89.39 5005.63   90.14
 5008.23   94.58 5189.65   95.27  5226.7   93.98  5256.7   95.28  5306.7   95.38
  5316.7   94.48  5466.5    95.7  6160.3      96  6261.9   96.15  6418.8   96.38
  6438.8   95.78  6999.3   97.58  7279.9   97.57  7479.3   96.98  7529.3   98.48
#Mann= 8 , 1 , 0
  3991.2     .12       0  4679.7     .14       0 4991.86     .04       0
 5008.23     .14       0  5466.5      .1       0  6160.3     .14       0
  6261.9      .2       0  7279.9     .99       0
#XS Ineff= 2 , 0
       0    4985      95    5016       0      95
Permanent Ineff=
       F       F
Bank Sta=4991.86,5008.23
XS Rating Curve= 0 ,0
Exp/Cntr=0.5,0.3

Type RM Length L Ch R = 1 ,25914.5 ,538.9,486.7,428.9
BEGIN DESCRIPTION:
Cross Section 25945.5-Interpolated
END DESCRIPTION:
XS GIS Cut Line= 5
      3113339.48     13922057.53      3112899.44     13922033.58
      3112355.36     13922003.36      3111743.28     13921451.73
      3110724.37     13921210.77
#Sta/Elev= 30
  4334.6   98.69  4354.6   97.51  4384.6   93.93  4434.6   93.11  4514.6   96.79
  4634.6   96.65  4694.6   94.68  4744.6   94.97  4764.6   96.75  4792.3   97.62
  4892.3   95.38  4974.2   96.17  4992.5   90.17  5000.3   88.65  5009.7   90.44
  5018.2   95.29  5032.3   95.75  5052.3   98.56  5092.3    95.9  5152.3   94.82
  5337.2   95.91  5487.2   94.86  5557.2   95.73  5697.2   94.65  5907.2    95.8
  6216.3   95.35  6301.2   96.53  6331.2   95.29  6381.2   96.59  7191.2   97.59
#Mann= 4 , 1 , 0
  4334.6      .1       0  4974.2     .04       0  5018.2     .14       0
  6216.3      .2       0
#XS Ineff= 2 , 0
       0                  5052.3       0   98.56
Permanent Ineff=
       F       F
Bank Sta=4974.2,5018.2
XS Rating Curve= 0 ,0
Exp/Cntr=0.3,0.1

Type RM Length L Ch R = 1 ,25427.8 ,975.6,994,985.1
BEGIN DESCRIPTION:
Cross Section 25458.8
END DESCRIPTION:
XS GIS Cut Line= 6
      3113606.98     13921268.61      3113343.95     13921418.21
      3112890.39     13921512.14      3112726.68      13921536.3
      3112498.57     13921525.56      3111124.12     13921259.44
#Sta/Elev= 30
  4040.8   99.25  4100.8   94.11  4120.8   94.57  4160.8   98.18  4180.8   98.58
  4230.8   94.52  4310.8   95.48  4343.4   97.25  4483.4    93.5  4753.4   95.15
  4916.6   95.04  4936.6   94.25  4961.9   96.73  4974.2   95.61  4992.5   89.61
  5000.3   88.09  5009.7   89.88  5018.2   94.73  5026.1   95.24  5042.1   99.94
  5082.1   94.94  5770.4   94.63  5790.4   95.43  6038.7    96.1  6120.4   95.35
  6170.4   96.02  6190.4   95.16  6280.4   96.58  6360.4   96.17  6600.4      98
#Mann= 4 , 1 , 0
  4040.8      .1       0  4974.2     .04       0  5018.2     .14       0
  6038.7      .2       0
#XS Ineff= 2 , 0
       0                  5042.1       0   99.94
Permanent Ineff=
       F       F
Bank Sta=4974.2,5018.2
XS Rating Curve= 0 ,0
Exp/Cntr=0.3,0.1

Type RM Length L Ch R = 1 ,24433.8 ,1023.7,1020.2,1017.5
BEGIN DESCRIPTION:
Cross Section 24464.8
END DESCRIPTION:
XS GIS Cut Line= 6
      3113805.51     13920462.63      3113298.09      13920456.6
      3112995.06     13920505.74      3112796.46       13920546.
      3111882.48     13920490.25      3111666.45     13920532.25
#Sta/Elev= 30
  3918.3   95.66  4078.3   96.15  4098.3   94.56  4158.3   93.58  4243.9    96.3
  4278.3    99.6  4358.3  100.45  4388.3   97.02  4425.8   99.12  4575.8   95.34
  4872.7   94.87  4892.7   93.53  4922.7   95.01  4982.2   92.85  4997.9    85.9
  5001.2   85.66  5022.3   91.33    5036   93.66  5064.7    94.4  5065.4   95.88
  5075.4    94.7  5125.4   93.89  5472.1   93.95  5542.1   95.91  5692.1   95.39
  5881.1   96.36  5921.1   95.43  6011.1   95.98  6038.7    97.1  6071.1  100.88
#Mann= 5 , 1 , 0
  3918.3     .99       0  4243.9      .1       0  4982.2     .04       0
  5022.3     .14       0  6038.7      .2       0
#XS Ineff= 2 , 0
       0  4922.7   95.01  5065.4       0   95.88
Permanent Ineff=
       F       F
Bank Sta=4982.2,5022.3
XS Rating Curve= 0 ,0
Exp/Cntr=0.3,0.1

Type RM Length L Ch R = 1 ,23413.6 ,573.1,668.7,672.5
BEGIN DESCRIPTION:
Cross Section 23444.6
END DESCRIPTION:
XS GIS Cut Line= 4
      3113423.92     13919367.83       3113007.4     13919520.27
      3112685.36     13919522.41       3112084.2      13919567.5
#Sta/Elev= 29
    4313    96.2    4333    94.9    4343    93.7    4363    92.8    4523    92.7
  4756.5    94.1  4836.5    93.3  4876.5    94.3  4948.7   93.81  4990.2   88.77
  4997.4   85.96  4998.3   85.42  5001.3   85.48  5002.7   86.52  5018.4   93.48
  5025.5   93.76  5036.5      94  5078.6    94.2  5088.6    94.5  5118.6      94
  5258.6    94.6  5278.6    95.2  5318.6    95.5  5338.6    95.1  5368.6    95.3
  5388.6    94.9  5408.6    95.5  5428.6      95  5681.4    96.5
#Mann= 5 , 1 , 0
    4313      .2       0    4313     .14       0  4948.7     .04       0
  5018.4     .14       0  5681.4      .2       0
#XS Ineff= 2 , 0
       0  4876.5    94.3               0
Permanent Ineff=
       F       F
Bank Sta=4948.7,5018.4
XS Rating Curve= 0 ,0
Exp/Cntr=0.3,0.1

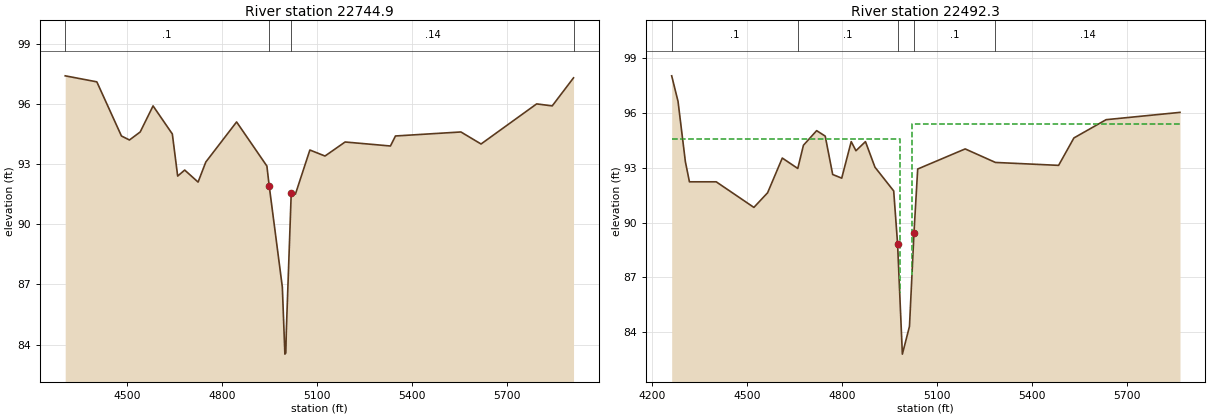
Type RM Length L Ch R = 1 ,22744.9 ,317.2,252.6,249.3
BEGIN DESCRIPTION:
Cross Section 22775.9-Interpolated
END DESCRIPTION:
XS GIS Cut Line= 5
      3113437.53     13919137.45      3112913.69     13918863.06
      3112741.87     13918849.84      3112058.79     13919092.27
      3111986.41     13919186.37
#Sta/Elev= 30
  4303.7    97.4  4403.7    97.1  4481.5    94.4  4506.9    94.2  4540.8    94.6
  4581.5    95.9  4642.4    94.5  4659.3    92.4  4681.5    92.7  4723.8    92.1
  4748.2    93.1  4845.6    95.1  4941.4    92.9  4948.7   91.91  4990.2   86.87
  4998.3   83.52  5001.3   83.58  5002.7   84.62  5018.4   91.58  5031.6    91.5
  5077.3    93.7  5125.1    93.4  5188.7    94.1    5332    93.9  5347.9    94.4
  5554.8    94.6  5618.5      94  5794.3      96  5843.5    95.9  5910.9    97.3
#Mann= 4 , 1 , 0
  4303.7      .1       0  4948.7     .04       0  5018.4     .14       0
  5910.9      .2       0
Bank Sta=4948.7,5018.4
XS Rating Curve= 0 ,0
Exp/Cntr=0.5,0.3

Type RM Length L Ch R = 1 ,22492.3 ,175,175,175
BEGIN DESCRIPTION:
Upstream Section of Bridge/Culvert/Weir
END DESCRIPTION:
XS GIS Cut Line= 5
      3113526.43     13918374.89      3113291.61     13918481.63
      3113065.62     13918522.49      3112446.91     13918722.88
      3112002.61     13918868.81
#Sta/Elev= 30
    4261   98.03  4281.1   96.63  4304.3   93.33  4317.1   92.23  4401.7   92.23
  4520.7   90.83    4564   91.63  4610.4   93.53  4659.3   92.96  4677.2   94.23
  4718.9   95.03    4746   94.73  4769.6   92.63  4798.1   92.43  4828.1   94.43
  4843.1   93.93  4873.1   94.43  4903.1   93.03  4962.3   91.73 4974.54   88.84
 4989.67    82.8 5012.14   84.32 5026.36   89.44  5038.1   92.93  5188.1   94.03
  5283.6   93.29  5483.2   93.13  5531.5   94.63  5633.2   95.63  5866.6   96.03
#Mann= 5 , 1 , 0
    4261      .1       0  4659.3      .1       0 4974.54     .04       0
 5026.36      .1       0  5283.6     .14       0
#XS Ineff= 2 , 0
       0  4981.3    94.6    5020       0    95.4
Permanent Ineff=
       F       F
Bank Sta=4974.54,5026.36
XS Rating Curve= 0 ,0
Exp/Cntr=0.5,0.3