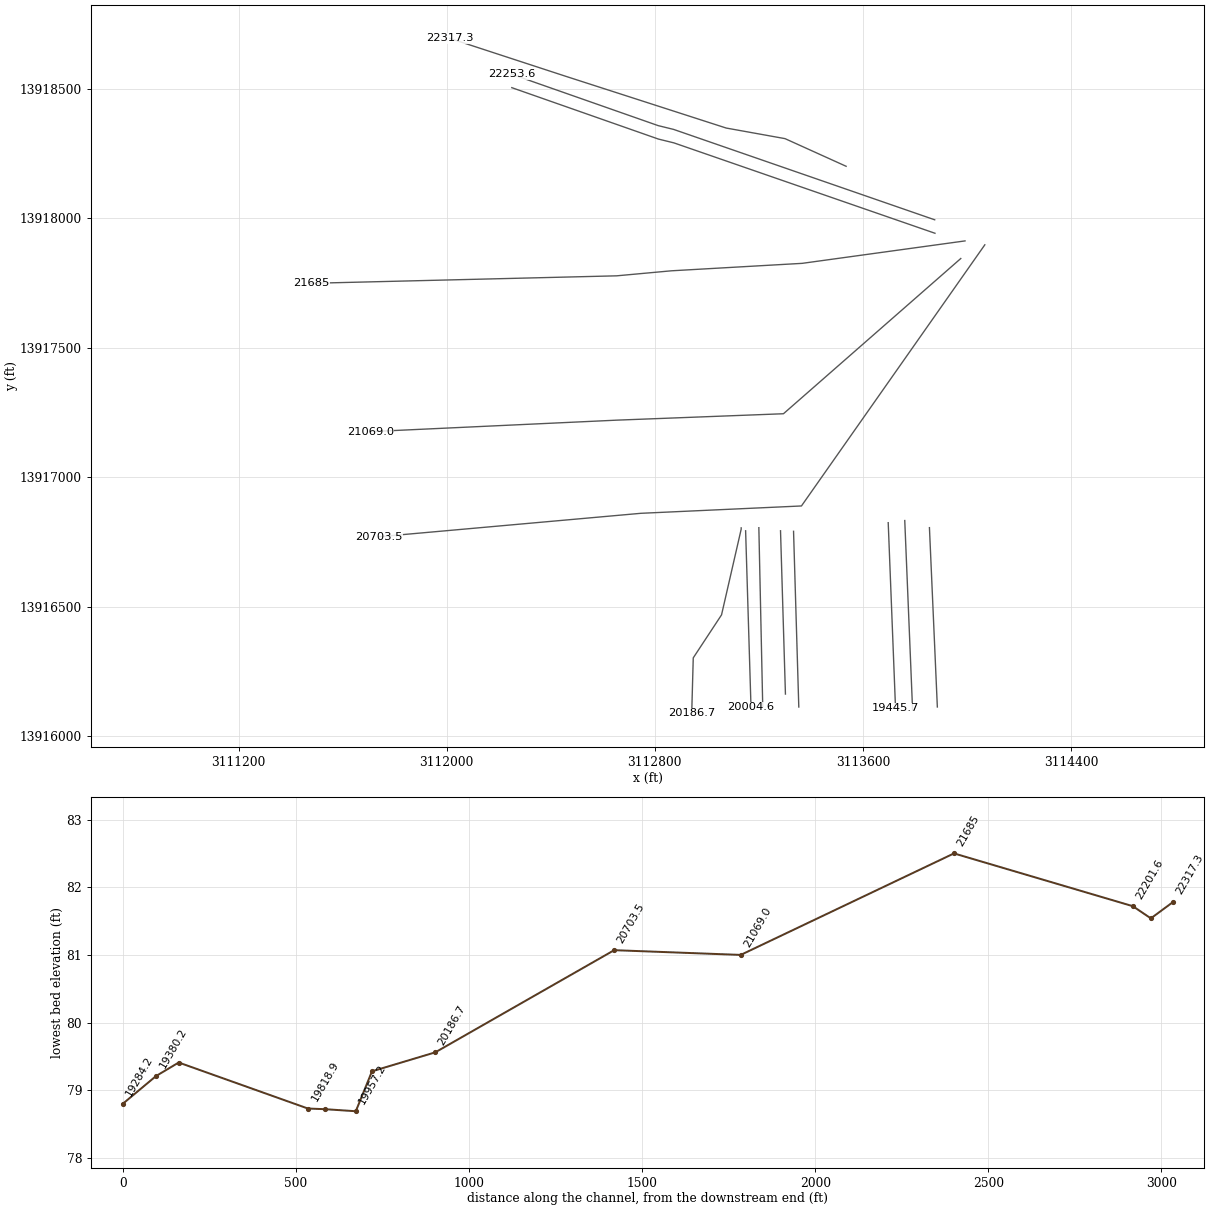
HEC-RAS study P140-00-00.prj: P140-00-00 (Hoods Bayou)

--- P140-00-00.g01 (geometry) --- (continued)

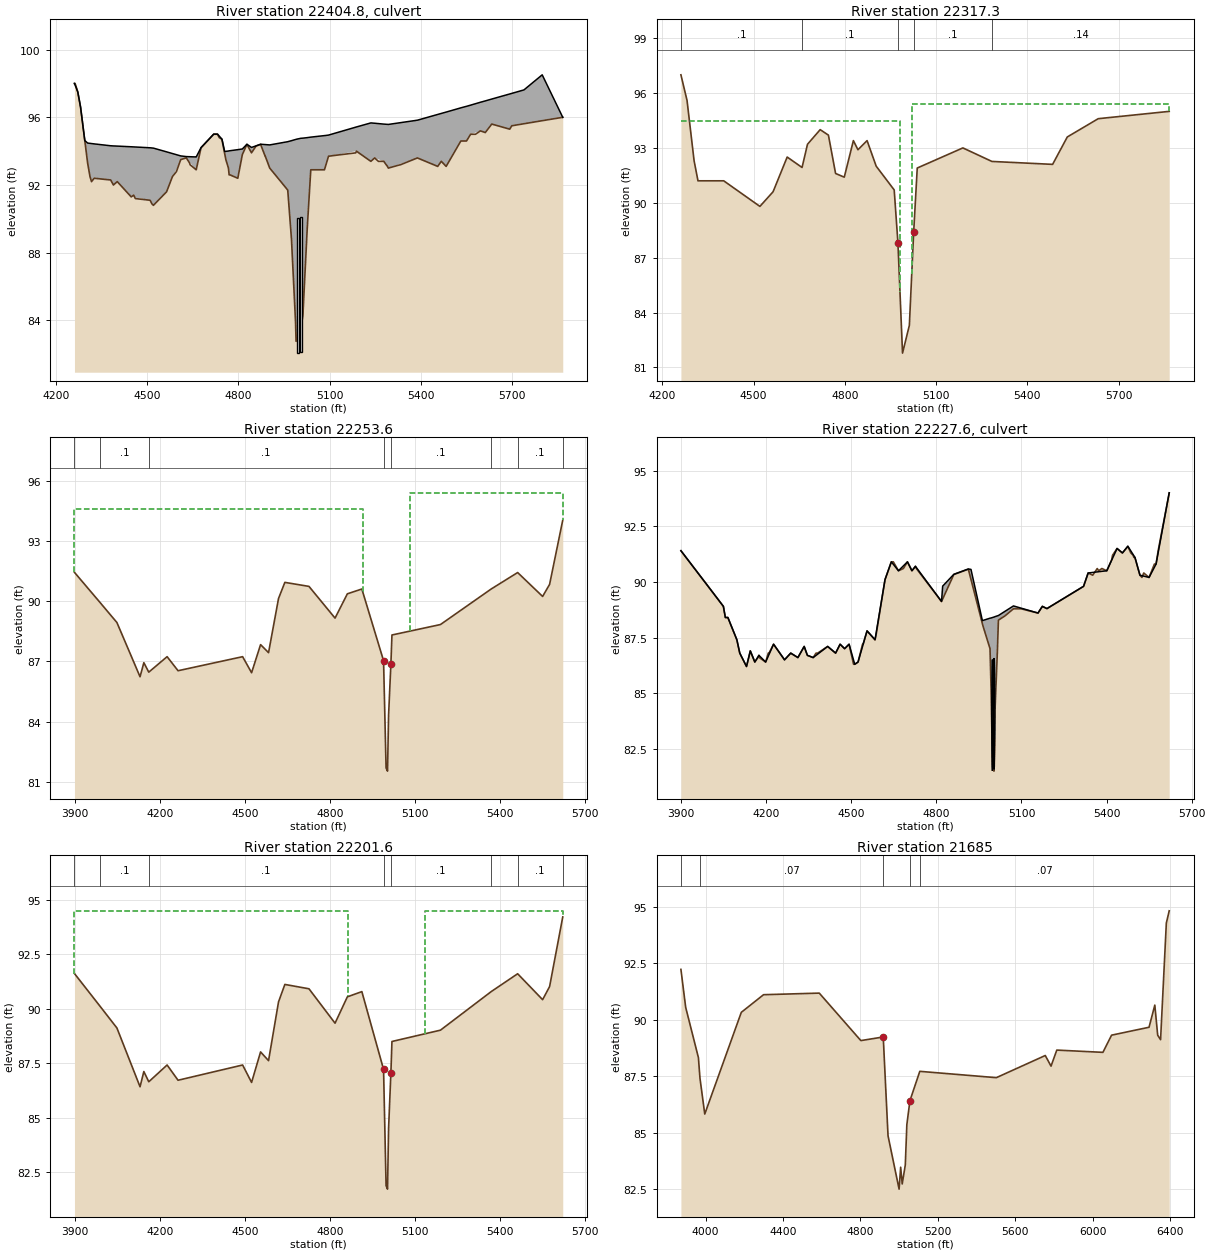
Type RM Length L Ch R = 2 ,22404.8 ,,,
BEGIN DESCRIPTION:
HARDY TOLL ROAD 2, SKEW ANGLE OF 25 DEGREES
Structure ID: P40-13
END DESCRIPTION:
Bridge Culvert--1,0,-1,-1, 0
Deck Dist Width WeirC Skew NumUp NumDn MinLoCord MaxHiCord MaxSubmerge Is_Ogee
10,155,3,0, 60, 60, , , 0.95, 0, 1,1,,
    4261  4271.9  4281.1    4295  4304.3  4317.1    4326  4380.1  4389.1  4401.7
  4447.7  4509.9  4520.7    4564  4610.4  4628.9  4659.3  4661.4  4677.2  4718.9
  4731.3    4746    4755  4767.3  4769.6  4798.1  4813.1  4828.1  4843.1  4873.1
  4903.1  4962.3 4974.54 4987.95 4989.67 5004.71 5012.14 5026.36  5038.1  5083.1
  5096.4  5188.1  5235.7  5248.1  5278.1  5293.1  5388.6  5455.5  5467.2  5483.2
  5531.5  5550.1  5563.7  5595.8  5611.9  5633.2  5692.3    5739    5799  5866.6
      98    97.5    96.6   94.63   94.48   94.45   94.43   94.32   94.31    94.3
   94.26    94.2   94.18   93.96   93.72   93.68   93.66   93.66   94.21   95.01
   95.01   94.71   93.98   94.01   94.02   94.09   94.13   94.41   94.22   94.41
   94.37   94.56   94.62   94.69    94.7   94.76   94.77    94.8   94.83   94.92
   94.95   95.43   95.67   95.65    95.6   95.58   95.83   96.17   96.23   96.31
   96.56   96.65   96.72   96.89   96.97   97.08   97.38   97.62   98.51      96
      98    97.5    96.6   94.62    93.3    92.2    92.4    92.3      92    92.2
    91.3    91.1    90.8    91.6    93.5    93.6   92.93    92.9    94.2      95
      95    94.7   93.85      93    92.6    92.4    93.8    94.4    93.9    94.4
      93    91.7   88.81   83.91   82.77   83.43   84.29   89.41    92.9    92.9
    93.7      94    93.4    93.6    93.4      93    93.6    93.1    93.4    93.1
    94.6    94.6      95    95.2    95.1    95.6    95.3   95.62    95.8      96
    4261  4271.9  4281.1    4295  4304.3  4317.1    4326  4380.1  4389.1  4401.7
  4447.7  4509.9  4520.7    4564  4610.4  4628.9  4659.3  4661.4  4677.2  4718.9
  4731.3    4746    4755  4767.3  4769.6  4798.1  4813.1  4828.1  4843.1  4873.1
  4903.1  4962.3 4974.54 4987.95 4989.67 5004.71 5012.14 5026.36  5038.1  5083.1
  5096.4  5188.1  5235.7  5248.1  5278.1  5293.1  5388.6  5455.5  5467.2  5483.2
  5531.5  5550.1  5563.7  5595.8  5611.9  5633.2  5692.3    5739    5799  5866.6
      98    97.5    96.6   94.63   94.48   94.45   94.43   94.32   94.31    94.3
   94.26    94.2   94.18   93.96   93.72   93.68   93.66   93.66   94.21   95.01
   95.01   94.71   93.98   94.01   94.02   94.09   94.13   94.41   94.22   94.41
   94.37   94.56   94.62   94.69    94.7   94.76   94.77    94.8   94.83   94.92
   94.95   95.43   95.67   95.65    95.6   95.58   95.83   96.17   96.23   96.31
   96.56   96.65   96.72   96.89   96.97   97.08   97.38   97.62   98.51      96
   97.05   96.55   95.65   93.67   92.35   91.25   91.45   91.35   91.05   91.25
   90.35   90.15   89.85   90.65   92.55   92.65   91.98   91.95   93.25   94.05
   94.05   93.75    92.9   92.05   91.65   91.45   92.85   93.45   92.95   93.45
   92.05   90.75   87.86   82.96   81.82   82.48   83.34   88.46   91.95   91.95
   92.75   93.05   92.45   92.65   92.45   92.05   92.65   92.15   92.45   92.15
   93.65   93.65   94.05   94.25   94.15   94.65   94.35   94.67   94.85   95.05
BR Coef= 1 , 0 , 0 ,1.25, 0 ,,,0.8,-1,2,0,
WSPro=,,,, 1 ,,,, 0 ,,,, 0 ,,,,-1 ,-1 ,-1 , 0 , 0 , 0 , 0 , 0
Culvert=2,8,8,155,0.015,0.4,1,8,1,82.07,4995.3,82.12,4995.3,Culvert #1  , 0 ,10
Culvert Bottom n=0.015
Culvert=2,8,8,155,0.015,0.4,1,8,1,82.12,5005.3,82.12,5005.3,Culvert #2  , 0 ,10
Culvert Bottom n=0.015
BR U #Sta/Elev= 103
    4261      98  4263.1      98  4271.9    97.5  4281.1    96.6    4295   94.62
  4304.3    93.3  4312.1    92.5  4317.1    92.2    4326    92.4  4362.8   92.33
  4380.1    92.3  4389.1      92  4401.7    92.2  4447.7    91.3  4455.8    91.4
  4461.2    91.2  4509.9    91.1  4515.2    90.9    4519   90.83  4520.7    90.8
    4564    91.6  4583.3    92.5  4596.5    92.8  4610.4    93.5    4619   93.55
  4628.9    93.6  4639.7    93.3  4641.2    93.2  4659.3   92.93  4661.4    92.9
  4677.2    94.2  4718.9      95  4731.3      95  4737.1    94.8    4746    94.7
    4748    94.5  4748.6   94.44    4755   93.85 4755.09   93.84  4755.2   93.83
 4755.31   93.82  4758.8    93.5  4767.3      93  4769.6    92.6  4772.4    92.6
  4798.1    92.4  4813.1    93.8  4826.6   94.34  4828.1    94.4  4843.1    93.9
    4858    94.3  4873.1    94.4  4885.9    93.8  4888.1    93.7  4888.5    93.7
  4903.1      93  4939.6    92.2  4962.3    91.7 4974.54   88.81 4987.95   83.91
 4989.67   82.77  4997.2    83.1 5004.71   83.43 5012.14   84.29 5026.36   89.41
  5038.1    92.9  5060.3    92.9  5081.5    92.9  5083.1    92.9  5096.4    93.7
  5121.3   93.76  5180.9   93.89  5185.9    93.9  5188.1      94 5232.29   93.44
  5232.4   93.44 5232.51   93.44  5232.6   93.44  5235.7    93.4  5248.1    93.6
  5260.4    93.4  5278.1    93.4  5283.6   93.26  5290.2    93.1  5293.1      93
  5328.6   93.18  5333.4    93.2  5388.6    93.6  5455.5    93.1  5467.2    93.4
  5483.2    93.1  5531.5    94.6  5550.1    94.6  5563.7      95  5579.7      95
  5595.8    95.2  5611.9    95.1  5633.2    95.6  5692.3    95.3    5699    95.5
    5739   95.62    5799    95.8  5866.6      96
BR U #Mann= 5
    4261      .1  4659.3      .1 4974.54     .04 5026.36      .1  5283.6     .14
BR U Banks=4974.54,5026.36
BR D #Sta/Elev= 103
    4261   97.05  4263.1   97.05  4271.9   96.55  4281.1   95.65    4295   93.67
  4304.3   92.35  4312.1   91.55  4317.1   91.25    4326   91.45  4362.8   91.38
  4380.1   91.35  4389.1   91.05  4401.7   91.25  4447.7   90.35  4455.8   90.45
  4461.2   90.25  4509.9   90.15  4515.2   89.95    4519   89.88  4520.7   89.85
    4564   90.65  4583.3   91.55  4596.5   91.85  4610.4   92.55    4619    92.6
  4628.9   92.65  4639.7   92.35  4641.2   92.25  4659.3   91.98  4661.4   91.95
  4677.2   93.25  4718.9   94.05  4731.3   94.05  4737.1   93.85    4746   93.75
    4748   93.55  4748.6   93.49    4755    92.9 4755.09   92.89  4755.2   92.88
 4755.31   92.87  4758.8   92.55  4767.3   92.05  4769.6   91.65  4772.4   91.65
  4798.1   91.45  4813.1   92.85  4826.6   93.39  4828.1   93.45  4843.1   92.95
    4858   93.35  4873.1   93.45  4885.9   92.85  4888.1   92.75  4888.5   92.75
  4903.1   92.05  4939.6   91.25  4962.3   90.75 4974.54   87.86 4987.95   82.96
 4989.67   81.82  4997.2   82.15 5004.71   82.48 5012.14   83.34 5026.36   88.46
  5038.1   91.95  5060.3   91.95  5081.5   91.95  5083.1   91.95  5096.4   92.75
  5121.3   92.81  5180.9   92.94  5185.9   92.95  5188.1   93.05 5232.29   92.49
  5232.4   92.49 5232.51   92.49  5232.6   92.49  5235.7   92.45  5248.1   92.65
  5260.4   92.45  5278.1   92.45  5283.6   92.31  5290.2   92.15  5293.1   92.05
  5328.6   92.23  5333.4   92.25  5388.6   92.65  5455.5   92.15  5467.2   92.45
  5483.2   92.15  5531.5   93.65  5550.1   93.65  5563.7   94.05  5579.7   94.05
  5595.8   94.25  5611.9   94.15  5633.2   94.65  5692.3   94.35    5699   94.55
    5739   94.67    5799   94.85  5866.6   95.05
BR D #Mann= 5
    4261      .1  4659.3      .1 4974.54     .04 5026.36      .1  5283.6     .14
BR D Banks=4974.54,5026.36
BC Design=,, 0 ,, 0 ,,,,,,
BC HTab HWMax=98.03
BC Use User HTab Curves=0
BC User HTab FreeFlow(D)= 0

Type RM Length L Ch R = 1 ,22317.3 ,63.7,63.7,63.7
BEGIN DESCRIPTION:
Downstream Section of Bridge/Culvert/Weir
END DESCRIPTION:
XS GIS Cut Line= 5
      3113535.11     13918200.11      3113300.29     13918306.85
       3113074.3     13918347.71      3112455.59      13918548.1
      3112011.29     13918694.03
#Sta/Elev= 30
    4261   97.01  4281.1   95.61  4304.3   92.31  4317.1   91.21  4401.7   91.21
  4520.7   89.81    4564   90.61  4610.4   92.51  4659.3   91.94  4677.2   93.21
  4718.9   94.01    4746   93.71  4769.6   91.61  4798.1   91.41  4828.1   93.41
  4843.1   92.91  4873.1   93.41  4903.1   92.01  4962.3   90.71 4974.54   87.82
 4989.67   81.78 5012.14    83.3 5026.36   88.42  5038.1   91.91  5188.1   93.01
  5283.6   92.27  5483.2   92.11  5531.5   93.61  5633.2   94.61  5866.6   95.01
#Mann= 5 , 1 , 0
    4261      .1       0  4659.3      .1       0 4974.54     .04       0
 5026.36      .1       0  5283.6     .14       0
#XS Ineff= 2 , 0
       0  4981.3    94.5    5020       0    95.4
Permanent Ineff=
       F       F
Bank Sta=4974.54,5026.36
XS Rating Curve= 0 ,0
Exp/Cntr=0.5,0.3

Type RM Length L Ch R = 1 ,22253.6 ,52,52,52
BEGIN DESCRIPTION:
Upstream Section of Bridge/Culvert/Weir
END DESCRIPTION:
XS GIS Cut Line= 4
      3113875.55     13917993.54      3112872.23     13918342.41
      3112812.51     13918357.16      3112249.04     13918555.62
#Sta/Elev= 30
  3899.6   91.44  3989.7   89.94  4049.3   88.94  4130.8   86.24  4144.2   86.94
  4161.6   86.47  4226.2   87.24  4264.8   86.54  4492.4   87.24    4524   86.44
  4555.7   87.84  4583.8   87.44    4619   90.14  4641.3   90.94  4726.3   90.74
  4818.2   89.16  4861.6   90.37  4912.7   90.61  4989.2   87.04  4998.1    81.7
  5003.2   81.54  5006.9   84.32  5015.1   86.89  5018.8   88.32  5189.8   88.84
  5368.6   90.61  5461.9   91.43  5549.9   90.24  5574.5   90.84  5620.9   94.04
#Mann= 8 , 1 , 0
  3899.6      .2       0  3989.7      .1       0  4161.6      .1       0
  4989.2     .04       0  5015.1      .1       0  5368.6     .12       0
  5461.9      .1       0  5620.9      .2       0
#XS Ineff= 2 , 0
       0    4917    94.6    5084       0    95.4
Permanent Ineff=
       F       F
Bank Sta=4989.2,5015.1
XS Rating Curve= 0 ,0
Exp/Cntr=0.5,0.3

Type RM Length L Ch R = 2 ,22227.6 ,,,
BEGIN DESCRIPTION:
ACCESS ROAD 6
Structure ID: P40-12
END DESCRIPTION:
Bridge Culvert--1,0,-1,-1, 0
Deck Dist Width WeirC Skew NumUp NumDn MinLoCord MaxHiCord MaxSubmerge Is_Ogee
10,32,3,0, 60, 60, , , 0.95, 0, 1,1,,
  3899.6  4049.3  4056.2  4065.1  4096.8    4107  4130.8  4144.2  4160.1  4174.6
  4198.3  4226.2  4264.8  4286.7  4311.9  4334.1  4345.4  4365.8  4416.9  4444.9
  4460.7  4476.6  4492.4  4512.3    4524  4555.7  4583.8    4619  4641.3  4666.5
  4698.1  4713.9  4726.3  4818.2  4822.3  4861.6  4912.7  4922.1  4962.3  4989.2
  4993.1  4998.1  5003.2  5006.9  5018.8  5071.8  5158.3  5173.7  5189.8    5319
  5335.1  5400.9    5437  5455.8  5475.1    5500  5517.7  5549.9  5574.5  5620.9
    91.4    88.9    88.4    88.4    87.4    86.8    86.2    86.9    86.4    86.7
    86.4    87.2    86.5    86.8    86.6    87.1    86.7    86.6    87.1    86.8
    87.2      87    87.2    86.3    86.4    87.8    87.4    90.1    90.9    90.5
    90.9    90.5    90.7   89.12   89.81   90.34   90.58   90.56   88.26   88.37
   88.38    88.4   88.42   88.44   88.49   88.92    88.6    88.9    88.8    89.8
    90.4    90.5    91.5    91.3    91.6    91.1    90.3    90.2    90.8      94
    91.4    88.9    88.4    88.4    87.4    86.8    86.2    86.9    86.4    86.7
    86.4    87.2    86.5    86.8    86.6    87.1    86.7    86.6    87.1    86.8
    87.2      87    87.2    86.3    86.4    87.8    87.4    90.1    90.9    90.5
    90.9    90.5    90.7   89.12   89.23   90.33   90.57   90.11   88.12      87
   85.08   81.66    81.5   84.28   88.28   88.79    88.6    88.9    88.8    89.8
    90.4    90.5    91.5    91.3    91.6    91.1    90.3    90.2    90.8      94
  3899.6  4049.3  4056.2  4065.1  4096.8    4107  4130.8  4144.2  4160.1  4174.6
  4198.3  4226.2  4264.8  4286.7  4311.9  4334.1  4345.4  4365.8  4416.9  4444.9
  4460.7  4476.6  4492.4  4512.3    4524  4555.7  4583.8    4619  4641.3  4666.5
  4698.1  4713.9  4726.3  4818.2  4822.3  4861.6  4912.7  4922.1  4964.6  4989.2
  4993.1  4998.1  5003.2  5006.9  5018.8  5071.8  5158.3  5173.7  5189.8    5319
  5335.1  5400.9    5437  5455.8  5475.1    5500  5517.7  5549.9  5574.5  5620.9
   91.64   89.14   88.64   88.64   87.64   87.04   86.44   87.14   86.64   86.94
   86.64   87.44   86.74   87.04   86.84   87.34   86.94   86.84   87.34   87.04
   87.44   87.24   87.44   86.54   86.64   88.04   87.64   90.34   91.14   90.74
   91.14   90.74   90.94   89.36   89.81   90.57   90.81   90.56   88.27   88.37
   88.38    88.4   88.42   88.44   88.52   89.03   88.84   89.14   89.04   90.04
   90.64   90.74   91.74   91.54   91.84   91.34   90.54   90.44   91.04   94.24
   91.64   89.14   88.64   88.64   87.64   87.04   86.44   87.14   86.64   86.94
   86.64   87.44   86.74   87.04   86.84   87.34   86.94   86.84   87.34   87.04
   87.44   87.24   87.44   86.54   86.64   88.04   87.64   90.34   91.14   90.74
   91.14   90.74   90.94   89.36   89.47   90.57   90.81   90.35   88.25   87.24
   85.32    81.9   81.74   84.52   88.52   89.03   88.84   89.14   89.04   90.04
   90.64   90.74   91.74   91.54   91.84   91.34   90.54   90.44   91.04   94.24
BR Coef= 1 , 0 , 0 ,1.25, 0 ,,,0.8,-1,2,0,
WSPro=,,,, 1 ,,,, 0 ,,,, 0 ,,,,-1 ,-1 ,-1 , 0 , 0 , 0 , 0 , 0
Culvert=1,5,,32,0.015,0.5,1,1,3,81.51,4997.6,81.48,4997.6,Culvert #1  , 0 ,10
Culvert Bottom n=0.015
Culvert=1,5,,32,0.015,0.5,1,1,3,81.58,5003.6,81.59,5003.6,Culvert #2  , 0 ,10
Culvert Bottom n=0.015
BR U #Sta/Elev= 99
  3899.6    91.4  3989.7    89.9  4049.3    88.9  4056.2    88.4  4065.1    88.4
  4096.8    87.4    4107    86.8  4130.8    86.2  4144.2    86.9  4160.1    86.4
  4161.6   86.43  4170.7    86.6  4174.6    86.7  4175.9    86.6  4198.3    86.4
  4207.5    86.8  4210.1    86.8  4226.2    87.2  4264.8    86.5  4286.7    86.8
  4311.9    86.6  4334.1    87.1  4345.4    86.7  4365.8    86.6  4375.9    86.8
  4381.6    86.8  4416.9    87.1  4444.9    86.8  4460.7    87.2  4476.6      87
  4492.4    87.2  4508.2    86.3  4512.3    86.3    4524    86.4  4539.9    87.2
  4541.7    87.2  4555.7    87.8  4583.8    87.4  4587.3    87.6    4619    90.1
  4641.3    90.9  4648.3    90.9  4666.5    90.5  4683.8    90.6  4698.1    90.9
  4713.9    90.5  4726.3    90.7  4729.7    90.6  4818.2   89.12  4822.3   89.23
  4861.6   90.33  4912.7   90.57  4922.1   90.11  4962.3   88.12  4964.6   88.01
  4989.2      87  4993.1   85.08  4998.1   81.66  5003.2    81.5  5006.9   84.28
  5015.1   86.85  5018.8   88.28    5027   88.35  5041.7   88.47  5071.8   88.79
  5072.1   88.79  5085.3   88.79  5099.2   88.79  5158.3    88.6  5173.7    88.9
  5189.8    88.8    5319    89.8  5335.1    90.4  5351.2    90.3  5367.3    90.6
  5368.6   90.57  5372.4    90.5  5383.5    90.6  5400.4    90.5  5400.9    90.5
  5418.2      91  5421.3    91.2    5437    91.5  5455.8    91.3  5461.9   91.39
  5475.1    91.6  5485.6    91.3  5493.5    91.2  5496.3    91.1    5500    91.1
  5517.7    90.3  5524.8    90.2  5531.1    90.4  5549.7    90.2  5549.9    90.2
  5568.7    90.8  5574.5    90.8  5581.9    91.4  5620.9      94
BR U #Mann= 8
  3899.6      .2  3989.7      .1  4161.6      .1  4989.2     .04  5015.1      .1
  5368.6     .12  5461.9      .1  5620.9      .2
BR U Banks=4989.2,5015.1
BR D #Sta/Elev= 99
  3899.6   91.64  3989.7   90.14  4049.3   89.14  4056.2   88.64  4065.1   88.64
  4096.8   87.64    4107   87.04  4130.8   86.44  4144.2   87.14  4160.1   86.64
  4161.6   86.67  4170.7   86.84  4174.6   86.94  4175.9   86.84  4198.3   86.64
  4207.5   87.04  4210.1   87.04  4226.2   87.44  4264.8   86.74  4286.7   87.04
  4311.9   86.84  4334.1   87.34  4345.4   86.94  4365.8   86.84  4375.9   87.04
  4381.6   87.04  4416.9   87.34  4444.9   87.04  4460.7   87.44  4476.6   87.24
  4492.4   87.44  4508.2   86.54  4512.3   86.54    4524   86.64  4539.9   87.44
  4541.7   87.44  4555.7   88.04  4583.8   87.64  4587.3   87.84    4619   90.34
  4641.3   91.14  4648.3   91.14  4666.5   90.74  4683.8   90.84  4698.1   91.14
  4713.9   90.74  4726.3   90.94  4729.7   90.84  4818.2   89.36  4822.3   89.47
  4861.6   90.57  4912.7   90.81  4922.1   90.35  4962.3   88.36  4964.6   88.25
  4989.2   87.24  4993.1   85.32  4998.1    81.9  5003.2   81.74  5006.9   84.52
  5015.1   87.09  5018.8   88.52    5027   88.59  5041.7   88.71  5071.8   89.03
  5072.1   89.03  5085.3   89.03  5099.2   89.03  5158.3   88.84  5173.7   89.14
  5189.8   89.04    5319   90.04  5335.1   90.64  5351.2   90.54  5367.3   90.84
  5368.6   90.81  5372.4   90.74  5383.5   90.84  5400.4   90.74  5400.9   90.74
  5418.2   91.24  5421.3   91.44    5437   91.74  5455.8   91.54  5461.9   91.63
  5475.1   91.84  5485.6   91.54  5493.5   91.44  5496.3   91.34    5500   91.34
  5517.7   90.54  5524.8   90.44  5531.1   90.64  5549.7   90.44  5549.9   90.44
  5568.7   91.04  5574.5   91.04  5581.9   91.64  5620.9   94.24
BR D #Mann= 8
  3899.6      .2  3989.7      .1  4161.6      .1  4989.2     .04  5015.1      .1
  5368.6     .12  5461.9      .1  5620.9      .2
BR D Banks=4989.2,5015.1
BC Design=,, 0 ,, 0 ,,,,,,
BC HTab HWMax=94.04
BC Use User HTab Curves=0
BC User HTab FreeFlow(D)= 0

Type RM Length L Ch R = 1 ,22201.6 ,497.8,516.6,516.6
BEGIN DESCRIPTION:
Downstream Section of Bridge/Culvert/Weir
END DESCRIPTION:
XS GIS Cut Line= 4
      3113876.65     13917941.56      3112873.33     13918290.43
      3112813.61     13918305.18      3112250.14     13918503.63
#Sta/Elev= 30
  3899.6   91.62  3989.7   90.12  4049.3   89.12  4130.8   86.42  4144.2   87.12
  4161.6   86.65  4226.2   87.42  4264.8   86.72  4492.4   87.42    4524   86.62
  4555.7   88.02  4583.8   87.62    4619   90.32  4641.3   91.12  4726.3   90.92
  4818.2   89.34  4861.6   90.55  4912.7   90.79  4989.2   87.22  4998.1   81.88
  5003.2   81.72  5006.9    84.5  5015.1   87.07  5018.8    88.5  5189.8   89.02
  5368.6   90.79  5461.9   91.61  5549.9   90.42  5574.5   91.02  5620.9   94.22
#Mann= 8 ,-1 , 0
  3899.6      .2       0  3989.7      .1       0  4161.6      .1       0
  4989.2     .04       0  5015.1      .1       0  5368.6     .12       0
  5461.9      .1       0  5620.9      .2       0
#XS Ineff= 2 , 0
       0    4865    94.5    5136       0    94.5
Permanent Ineff=
       F       F
Bank Sta=4989.2,5015.1
XS Rating Curve= 0 ,0
Exp/Cntr=0.5,0.3

Type RM Length L Ch R = 1 ,21685   ,620,616,615
XS GIS Cut Line= 5
       3113992.2     13917912.04      3113366.07     13917825.39
      3112863.88     13917796.64      3112653.15     13917777.23
      3111477.87     13917748.31
#Sta/Elev= 30
 3872.98   92.22 3897.61   90.54 3963.28   88.32 3971.49    87.4 3996.12   85.82
 4184.92   90.32 4299.85    91.1 4587.68   91.17 4802.45   89.07 4918.09   89.23
 4942.87   84.86    5000    82.5 5008.09   83.47 5016.11   82.73 5032.04   83.57
 5040.01   85.35 5055.94   86.41  5106.9   87.71  5502.2   87.43 5755.08   88.41
 5784.86   87.94 5814.64   88.65  6052.9   88.55 6097.57   89.31 6291.15   89.66
 6320.93   90.64 6335.82   89.31 6350.71   89.11 6380.49   94.27 6395.39   94.81
#Mann= 5 ,-1 , 0
 3872.98      .2       0 3971.49     .07       0 4918.09     .04       0
 5055.94     .07       0  5106.9     .07       0
#XS Ineff= 2 , 0
       0 4293.43    90.5               0
Permanent Ineff=
       T       F
Bank Sta=4918.09,5055.94
XS Rating Curve= 0 ,0
Exp/Cntr=0.3,0.1

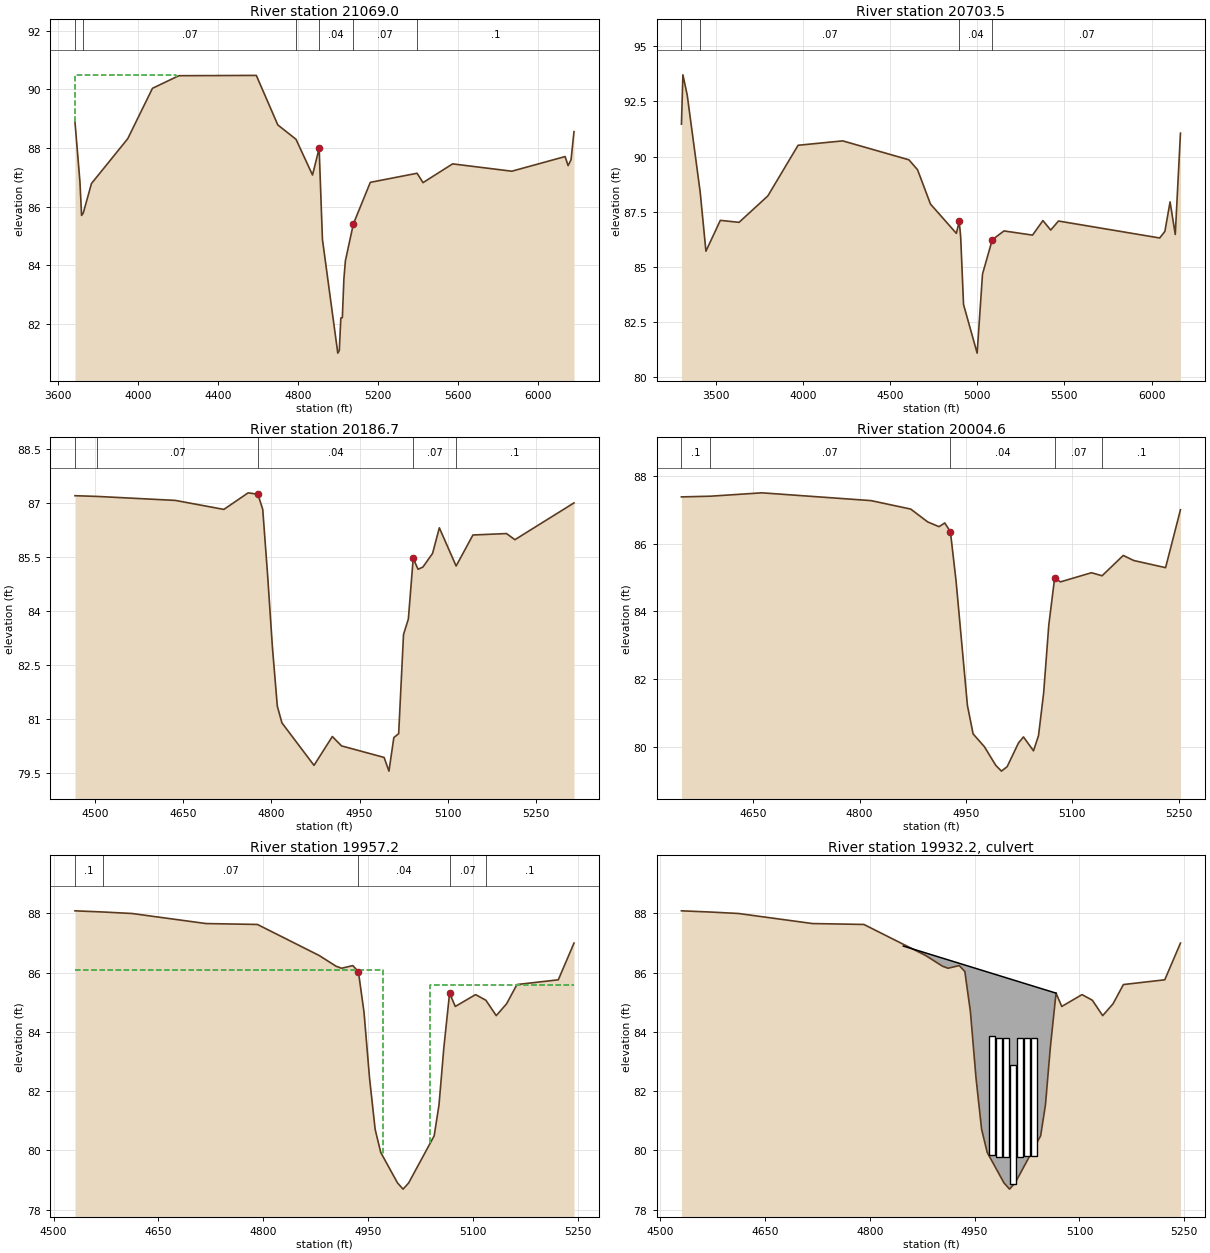
Type RM Length L Ch R = 1 ,21069.0 ,350,365.5,375
XS GIS Cut Line= 5
 3113975.863764113917844.1149406 3113294.284746713917244.8375959
 3112894.545388713917229.3970099 3112653.147577513917220.0725535
 3111705.898487813917175.7120779
#Sta/Elev= 30
 3684.73   88.88 3709.48   86.85 3717.73    85.7 3725.98   85.78 3767.24   86.79
 3948.75   88.32 4072.51   90.04 4204.52   90.47  4592.3   90.48 4699.85   88.79
 4790.85    88.3 4873.57   87.08 4906.66   87.99 4923.21   84.88    5000      81
 5007.61   81.09 5015.22    82.2 5022.84   82.21 5030.45   83.52 5038.06   84.15
 5077.91   85.41 5162.86   86.83  5396.9   87.14 5426.54   86.82 5574.71   87.46
 5871.05   87.21 6137.75   87.71 6152.57    87.4 6167.39    87.6  6182.2   88.56
#Mann= 6 ,-1 , 0
 3684.73      .1       0 3725.98     .07       0 4790.85     .07       0
 4906.66     .04       0 5077.91     .07       0  5396.9      .1       0
#XS Ineff= 2 , 0
       0 4188.02    90.5               0
Permanent Ineff=
       F       F
Bank Sta=4906.66,5077.91
XS Rating Curve= 0 ,0
Exp/Cntr=0.3,0.1

Type RM Length L Ch R = 1 ,20703.5 ,20,516.8,1250
XS GIS Cut Line= 5
 3114068.224143713917896.9501368 3113363.434214713916888.8366674
 3112914.070940213916868.1907113 3112746.320291413916860.4830496
 3111738.570010413916769.9366428
#Sta/Elev= 30
 3304.68   91.47 3312.94   93.71  3337.7   92.79    3412   88.39 3445.02    85.7
 3527.58    87.1 3634.89   87.01    3800   88.21 3973.36   90.51 4229.28   90.71
 4608.89   89.85 4658.33    89.4 4732.49   87.84 4880.81   86.51 4897.29   87.05
 4905.53   86.36 4922.01   83.28    5000   81.07 5030.78   84.66 5086.73   86.22
 5153.93   86.62 5317.61   86.43 5377.13   87.09 5421.77   86.66  5466.4   87.07
 6046.71    86.3 6076.47    86.6 6106.23   87.94 6135.99   86.46 6165.75   91.06
#Mann= 4 ,-1 , 0
 3304.68      .1       0    3412     .07       0 4897.29     .04       0
 5086.73     .07       0
#XS Ineff= 2 , 0
       0 3981.62    90.5               0
Permanent Ineff=
       T       F
Bank Sta=4897.29,5086.73
XS Rating Curve= 0 ,0
Exp/Cntr=0.3,0.1

Type RM Length L Ch R = 1 ,20186.7 ,15,182.7,250
XS GIS Cut Line= 6
 3113131.769323713916804.2981226 3113131.769323713916799.0897997
 3113056.248477413916468.3608024 3112992.960546213916371.7628984
  3112947.56234313916302.4707142 3112941.665045113916088.1522452
#Sta/Elev= 30
 4465.51    87.2 4503.82   87.18  4636.2   87.07 4718.94   86.82 4760.31   87.28
 4776.86   87.24 4785.14   86.82 4793.41      85 4801.69   82.98 4809.96   81.36
 4817.77    80.9 4872.41   79.72 4903.63   80.52 4919.25   80.26 4991.72   79.94
    5000   79.56 5008.28   80.49 5016.53    80.6 5024.78   83.35 5033.02   83.78
 5041.27   85.46 5049.51   85.16 5057.76   85.22 5074.25    85.6 5085.76   86.31
 5114.35   85.25 5142.94   86.11 5200.11   86.15  5214.4   85.98    5315      87
#Mann= 5 ,-1 , 0
 4465.51      .1       0 4503.82     .07       0 4776.86     .04       0
 5041.27     .07       0 5114.35      .1       0
Bank Sta=4776.86,5041.27
XS Rating Curve= 0 ,0
Exp/Cntr=0.3,0.1

Type RM Length L Ch R = 1 ,20004.6 ,50,46.8,45
XS GIS Cut Line= 3
 3113148.811612413916793.0422396 3113164.118340413916290.1098465
 3113169.564851813916111.1499026
#Sta/Elev= 30
 4549.09   87.38 4589.57    87.4 4662.42    87.5 4816.23   87.27 4872.16   87.02
 4896.13   86.64 4912.11    86.5  4920.1   86.61 4928.09   86.35 4936.08   84.89
 4952.06   81.22 4960.05   80.38 4976.03      80 4992.01   79.45    5000   79.28
 5007.99   79.41 5023.97   80.11 5031.04   80.29 5045.18   79.88 5052.25   80.33
 5059.47   81.59  5066.7   83.59 5074.93   84.98 5083.16   84.87 5126.86   85.14
 5141.78   85.05 5171.62   85.65 5186.54    85.5  5231.3   85.29 5252.26      87
#Mann= 5 ,-1 , 0
 4549.09      .1       0 4589.57     .07       0 4928.09     .04       0
 5074.93     .07       0 5141.78      .1       0
Bank Sta=4928.09,5074.93
XS Rating Curve= 0 ,0
Exp/Cntr=0.5,0.3

Type RM Length L Ch R = 1 ,19957.2 ,87.9,87.9,87.9
XS GIS Cut Line= 3
  3113199.68388613916804.9595386  3113210.80197413916291.3122719
  3113214.64448613916113.7896611
#Sta/Elev= 29
 4530.68   88.09 4571.45   88.05 4612.22      88 4718.21   87.66  4791.6   87.63
 4880.04   86.58 4904.03   86.22 4912.03   86.15 4928.02   86.24 4936.02   86.04
 4944.02   84.68 4952.01   82.44 4960.01   80.71 4968.01   79.93    4992    78.9
    5000   78.69 5007.99    78.9 5044.45   80.49 5051.37   81.54  5058.3   83.47
 5066.49   85.31 5074.67   84.86 5103.64   85.26 5118.43   85.07 5133.23   84.55
 5148.03   84.95 5162.82    85.6 5222.01   85.76 5244.45      87
#Mann= 5 ,-1 , 0
 4530.68      .1       0 4571.45     .07       0 4936.02     .04       0
 5066.49     .07       0 5118.43      .1       0
#XS Ineff= 2 , 0
       0    4971    86.1    5039       0    85.6
Permanent Ineff=
       F       F
Bank Sta=4936.02,5066.49
XS Rating Curve= 0 ,0
Exp/Cntr=0.5,0.3

Type RM Length L Ch R = 2 ,19932.2 ,,,
Bridge Culvert--1,0,-1,-1, 0
Deck Dist Width WeirC Skew NumUp NumDn MinLoCord MaxHiCord MaxSubmerge Is_Ogee
25,48.5,2.6,0, 2, 3, , , 0.98, 0, 4,4,,
 4848.05 5066.49
    86.9   85.31
   78.69   78.69
 4821.85 4927.12 5064.94
    86.9    86.9   84.38
   78.75   78.75   78.75
BR Coef=-1 , 0 , 0 ,, 0 ,,,0.8,-1,,0,
WSPro=,,,, 1 ,,,, 0 ,,,, 0 ,,,,-1 ,-1 ,-1 , 0 , 0 , 0 , 0 , 0
Culvert=2,4,8,54.43,0.013,0.5,1,8,1,79.85,4975,79.84,4975,Culvert #1  , 0 ,10.57
Culvert Bottom n=0.013
Culvert=2,4,8,51.26,0.013,0.5,1,8,1,79.78,4985,79.81,4985,Culvert #2  , 0 ,13.74
Culvert Bottom n=0.013
Culvert=2,4,8,48.71,0.013,0.5,1,8,1,79.78,4995,79.84,4995,Culvert #3  , 0 ,16.29
Culvert Bottom n=0.013
Culvert=2,4,9,48.71,0.013,0.5,1,8,1,78.88,5005,78.84,5005,Culvert #4  , 0 ,16.29
Culvert Bottom n=0.013
Culvert=2,4,8,48.71,0.013,0.5,1,8,1,79.79,5015,79.79,5015,Culvert #5  , 0 ,16.29
Culvert Bottom n=0.013
Culvert=2,4,8,48.71,0.013,0.5,1,8,1,79.8,5025,79.84,5025,Culvert #6  , 0 ,16.29
Culvert Bottom n=0.013
Culvert=2,4,8,48.71,0.013,0.5,1,8,1,79.8,5035,79.85,5035,Culvert #7  , 0 ,16.29
Culvert Bottom n=0.013
BC Design=,, 0 ,, 0 ,,,,,,
BC HTab HWMax=88.09
BC Use User HTab Curves=0
BC User HTab FreeFlow(D)= 0

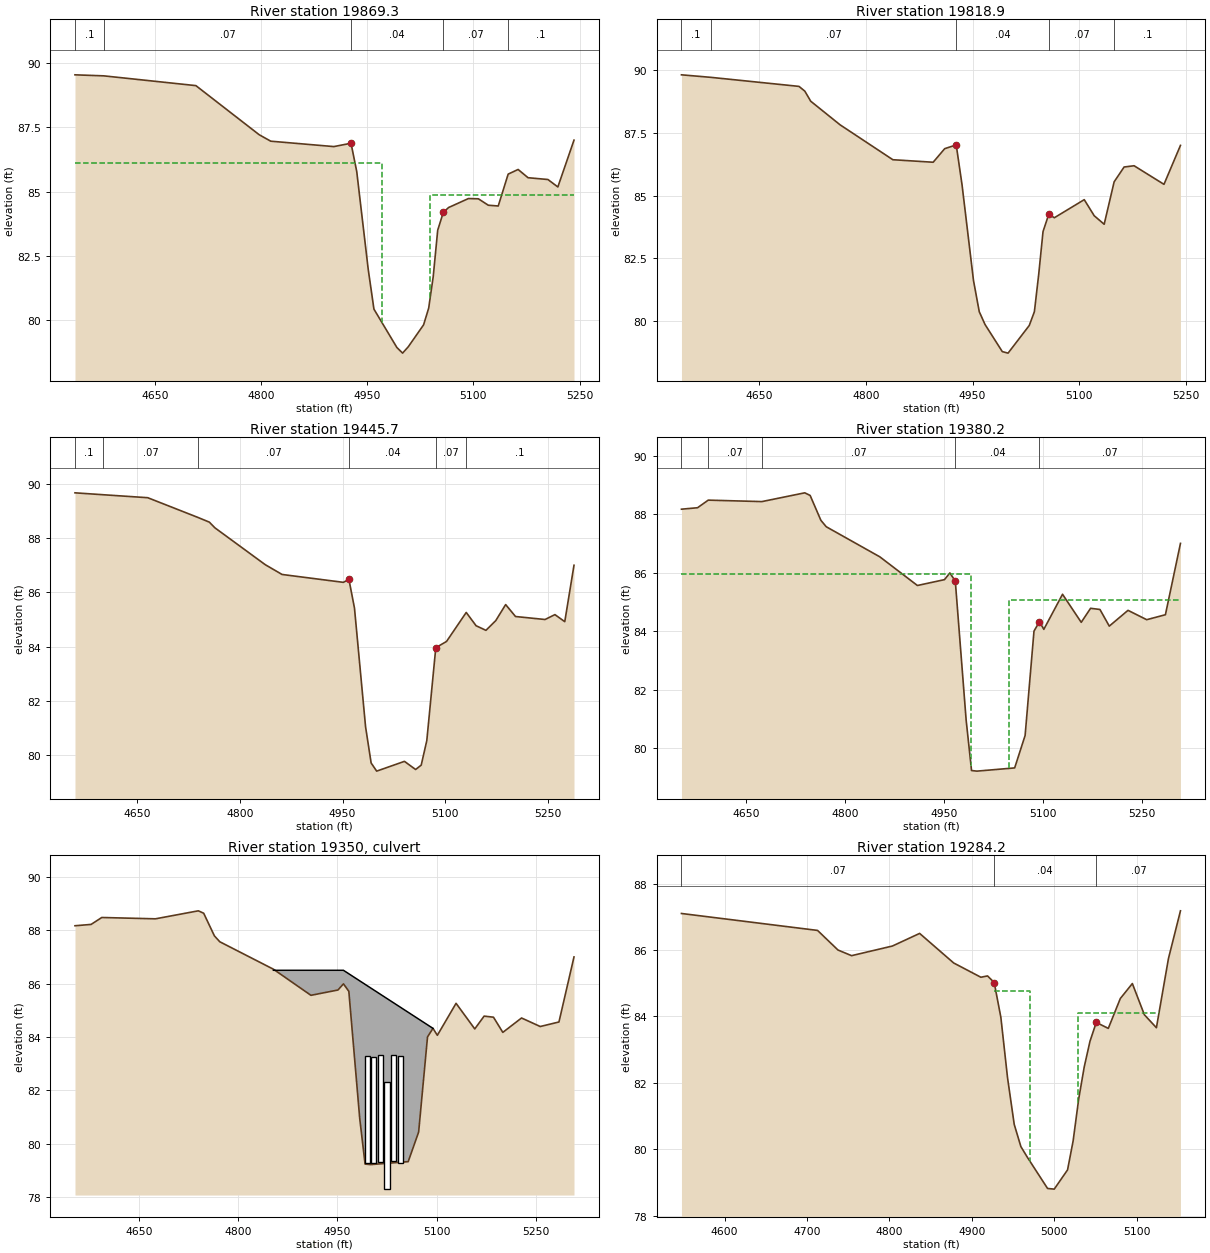
Type RM Length L Ch R = 1 ,19869.3 ,50.4,50.4,50.4
XS GIS Cut Line= 3
 3113282.975386113916793.0632369 3113297.949765613916293.5563619
 3113301.872069213916162.7165807
#Sta/Elev= 29
 4537.13   89.54  4577.8    89.5 4707.96   89.12 4797.44   87.21 4813.71   86.96
 4902.82   86.75 4927.12   86.88 4935.21   85.78 4951.41   81.98 4959.51   80.43
  4991.9   78.94    5000   78.72  5008.1   78.97 5029.66   79.82 5036.86   80.47
 5043.24   81.69 5049.61    83.5 5057.49   84.19 5064.94   84.38 5093.01   84.73
 5107.05   84.72 5121.09   84.47 5135.12   84.44 5149.16   85.68  5163.2   85.86
 5177.24   85.54 5205.31   85.47 5219.35   85.18 5242.16      87
#Mann= 5 ,-1 , 0
 4537.13      .1       0  4577.8     .07       0 4927.12     .04       0
 5057.49     .07       0 5149.16      .1       0
#XS Ineff= 2 , 0
       0    4971    86.1    5039       0   84.88
Permanent Ineff=
       F       F
Bank Sta=4927.12,5057.49
XS Rating Curve= 0 ,0
Exp/Cntr=0.5,0.3

Type RM Length L Ch R = 1 ,19818.9 ,380,373.2,375
XS GIS Cut Line= 3
 3113333.062556313916790.9907345 3113347.810230213916294.8404801
 3113353.223933313916112.7063299
#Sta/Elev= 30
 4540.68   89.81 4581.99   89.71 4705.93   89.35 4714.19   89.16 4722.45   88.76
 4763.76   87.82 4837.97   86.43 4894.68   86.33 4910.88   86.87 4927.09   87.02
 4935.19   85.45 4951.39   81.62 4959.49   80.38  4967.6   79.87  4991.9   78.79
    5000   78.73  5029.8   79.83 5037.03   80.38 5043.11   81.87 5049.17   83.57
 5057.27   84.26 5065.08   84.12 5107.13   84.84 5121.15    84.2 5135.17   83.86
 5149.18   85.55  5163.2   86.14 5177.21   86.19 5219.26   85.45 5242.45      87
#Mann= 5 ,-1 , 0
 4540.68      .1       0 4581.99     .07       0 4927.09     .04       0
 5057.27     .07       0 5149.18      .1       0
Bank Sta=4927.09,5057.27
XS Rating Curve= 0 ,0
Exp/Cntr=0.3,0.1

Type RM Length L Ch R = 1 ,19445.7 ,65.5,65.5,65.5
XS GIS Cut Line= 3
 3113696.903692113916824.2895524    3113717.092313916310.0117096
 3113725.007966613916108.3661155
#Sta/Elev= 30
 4558.67   89.67 4599.61    89.6 4665.11   89.49 4738.79   88.76 4755.17   88.59
 4763.35   88.38 4837.04   87.02  4861.6   86.66 4951.27   86.37 4959.39   86.48
 4967.52   85.42 4983.76   81.04 4991.88   79.71    5000   79.41 5040.61   79.77
 5056.93   79.47 5065.13   79.63 5073.34   80.54 5086.46   83.96 5102.17   84.19
    5131   85.26 5145.42   84.77 5159.83    84.6 5174.24   84.96 5188.66   85.55
 5203.07   85.11 5246.32      85 5260.73   85.18 5275.14   84.92 5288.64      87
#Mann= 6 ,-1 , 0
 4558.67      .1       0 4599.61     .07       0 4738.79     .07       0
 4959.39     .04       0 5086.46     .07       0    5131      .1       0
Bank Sta=4959.39,5086.46
XS Rating Curve= 0 ,0
Exp/Cntr=0.5,0.3

Type RM Length L Ch R = 1 ,19380.2 ,96,96,96
XS GIS Cut Line= 3
 3113760.498053113916832.5575805 3113781.886789913916312.8096043
 3113790.618399713916100.6282701
#Sta/Elev= 30
  4552.7   88.17 4577.05   88.22 4593.28   88.48 4674.45   88.43 4739.39   88.73
  4747.5   88.64 4763.74   87.79 4771.85   87.57 4853.02   86.54 4909.84   85.56
 4950.82   85.76 4959.02   85.99 4967.21   85.71 4983.61   80.96  4991.8   79.23
    5000   79.21 5057.07   79.32 5072.89   80.43 5086.32      84 5094.61   84.32
  5101.2   84.06 5129.52   85.26 5157.83    84.3 5171.99   84.78 5186.15   84.74
  5200.3   84.17 5228.62   84.71 5256.93   84.39 5285.25   84.56 5308.03      87
#Mann= 5 ,-1 , 0
  4552.7      .1       0 4593.28     .07       0 4674.45     .07       0
 4967.21     .04       0 5094.61     .07       0
#XS Ineff= 2 , 0
       0    4991   85.97    5049       0   85.06
Permanent Ineff=
       F       F
Bank Sta=4967.21,5094.61
XS Rating Curve= 0 ,0
Exp/Cntr=0.5,0.3

Type RM Length L Ch R = 2 ,19350   ,,,
Bridge Culvert--1,0,-1,-1, 0
Deck Dist Width WeirC Skew NumUp NumDn MinLoCord MaxHiCord MaxSubmerge Is_Ogee
30,48.5,2.6,0, 3, 2, , , 0.98, 0, 4,4,,
 4853.02 4959.02 5094.61
    86.5    86.5   84.32
    78.5    78.5    78.5
 4836.71 5051.01
    86.5   83.82
   78.37   78.37
BR Coef=-1 , 0 , 0 ,, 0 ,,,0.8,-1,,0,
WSPro=,,,, 1 ,,,, 0 ,,,, 0 ,,,,-1 ,-1 ,-1 , 0 , 0 , 0 , 0 , 0
Culvert=2,4,8,48.5,0.013,0.5,1,8,1,79.28,4995,79.31,4975,Culvert #1  , 0 ,21.5
Culvert Bottom n=0.013
Culvert=2,4,8,48.5,0.013,0.5,1,8,1,79.26,5005,79.29,4985,Culvert #2  , 0 ,21.5
Culvert Bottom n=0.013
Culvert=2,4,8,48.5,0.013,0.5,1,8,1,79.32,5015,79.23,4995,Culvert #3  , 0 ,21.5
Culvert Bottom n=0.013
Culvert=2,4,8,48.5,0.013,0.5,1,8,1,78.29,5025,78.3,5005,Culvert #4  , 0 ,21.5
Culvert Bottom n=0.013
Culvert=2,4,8,48.5,0.013,0.5,1,8,1,79.33,5035,79.33,5015,Culvert #5  , 0 ,21.5
Culvert Bottom n=0.013
Culvert=2,4,8,48.5,0.013,0.5,1,8,1,79.27,5045,79.21,5025,Culvert #6  , 0 ,21.5
Culvert Bottom n=0.013
BC Design=,, 0 ,, 0 ,,,,,,
BC HTab HWMax=88.8
BC Use User HTab Curves=0
BC User HTab FreeFlow(D)= 0

Type RM Length L Ch R = 1 ,19284.2 ,135,138.6,140
XS GIS Cut Line= 6
3113855.3666297213916805.1065199 3113871.294091313916442.1928756
3113876.7914556413916316.92737813113876.7924398913916316.9073651
3113877.4010344713916303.03731413113885.7487868113916112.8323139
#Sta/Elev= 30
 4547.75    87.1 4712.87   86.59 4737.64      86 4754.15   85.83 4803.69   86.12
 4836.71    86.5 4877.99   85.61 4911.01   85.18  4919.1   85.22 4927.19   85.02
 4935.28   83.97 4943.37   82.15 4951.46   80.75 4959.55   80.08 4967.64   79.75
 4991.91   78.82    5000    78.8 5016.18   79.38 5022.92   80.25 5029.66   81.51
  5036.4   82.48 5043.36   83.25 5051.01   83.82  5065.6   83.64 5080.19   84.54
 5094.78   84.99 5109.38   84.05 5123.97   83.66 5138.56   85.74 5153.15   87.18
#Mann= 3 ,-1 , 0
 4547.75     .07       0 4927.19     .04       0 5051.01     .07       0
#XS Ineff= 2 ,-1
    5029 5127.11   84.11 4927.19    4971   84.78
Permanent Ineff=
       F       F
Bank Sta=4927.19,5051.01
XS Rating Curve= 0 ,0
Exp/Cntr=0.5,0.3