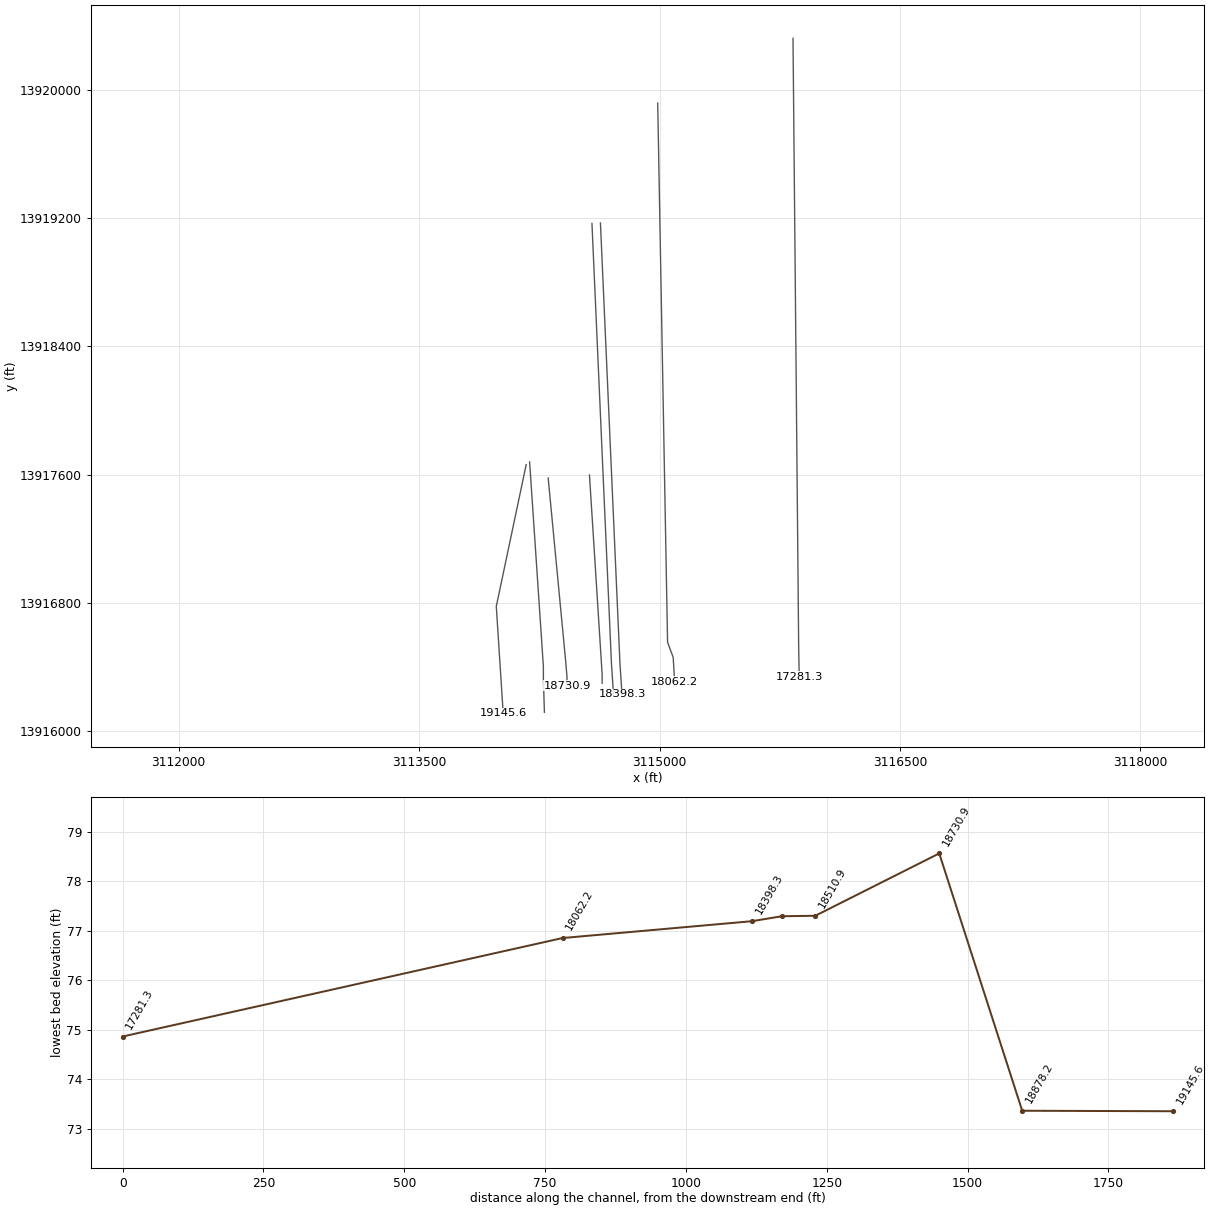
HEC-RAS study P140-00-00.prj: P140-00-00 (Hoods Bayou)

--- P140-00-00.g01 (geometry) --- (continued)

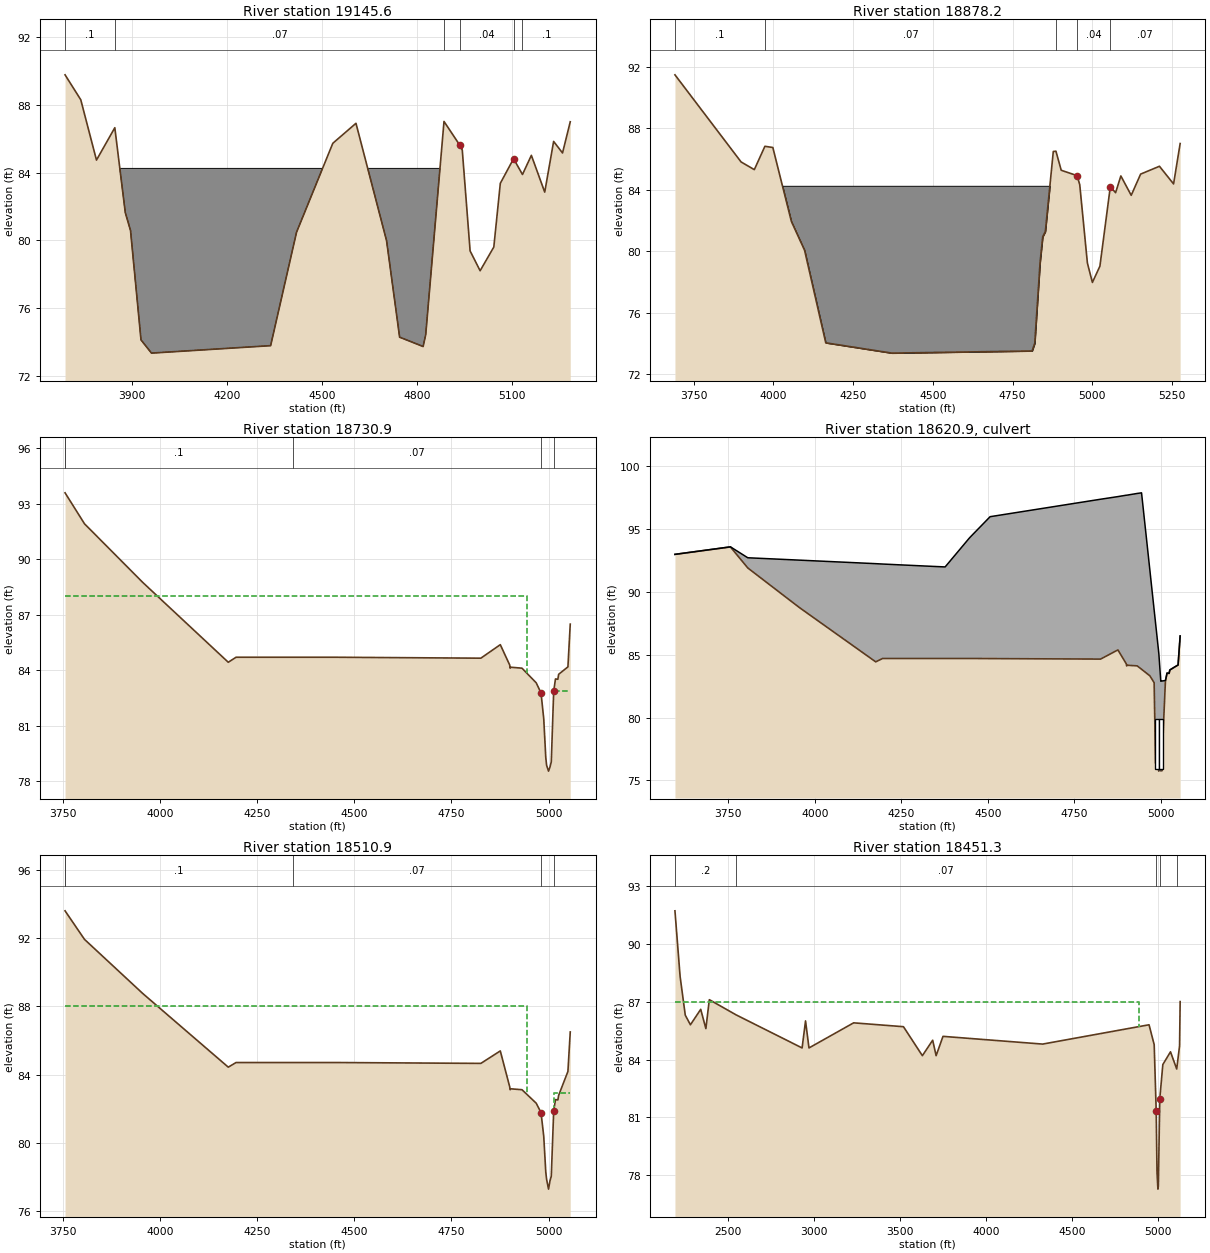
Type RM Length L Ch R = 1 ,19145.6 ,240,267.4,265
XS GIS Cut Line= 4
 3114167.767251713917662.6710778 3113981.234816413916779.0649053
 3114010.718025113916322.6901619 3114024.311501913916112.2732599
#Sta/Elev= 30
 3688.99   89.77 3738.63    88.3 3788.26   84.74 3846.17   86.65 3879.26   81.64
 3895.81   80.58  3928.9   74.13 3961.99   73.35 4338.35   73.79 4420.15   80.48
 4534.67   85.73 4607.84   86.91  4704.5   79.98 4745.73   74.29 4819.94   73.74
 4828.18   74.44  4885.9   87.02 4935.37   85.63 4943.62   85.33 4968.35   79.38
    5000   78.21 5043.22   79.61 5063.78   83.37 5105.62   84.82 5133.74   83.89
 5161.85   85.02 5204.02   82.85 5232.14   85.84 5260.25   85.16 5284.64      87
#Mann= 6 ,-1 , 0
 3688.99      .1       0 3846.17     .07       0  4885.9     .05       0
 4935.37     .04       0 5105.62     .07       0 5133.74      .1       0
#XS Ineff= 2 , 0
       0  4885.9    86.5               0
Permanent Ineff=
       F       F
#Block Obstruct= 2 , 0
       0  4885.9   84.25               0
Bank Sta=4935.37,5105.62
XS Rating Curve= 0 ,0
Exp/Cntr=0.3,0.1

Type RM Length L Ch R = 1 ,18878.2 ,140,147.3,155
XS GIS Cut Line= 5
  3114189.16189413917679.3049028 3114274.999320713916404.7251029
 3114275.009491313916334.1015564 3114275.010803613916325.4355633
 3114281.454360313916118.9536928
#Sta/Elev= 30
 3691.15   91.47 3898.53    85.8 3940.01    85.3 3973.19   86.82 3998.07   86.74
 4056.14   81.93 4097.62   80.05 4163.98   74.03 4371.36   73.36 4811.01    73.5
  4819.3      74 4835.89   79.24 4844.19   80.93 4852.48   81.27 4877.37   86.48
 4885.66    86.5 4902.25   85.26 4952.03   84.91 4960.32   84.32 4984.31   79.22
    5000   77.96 5023.54   79.02 5056.17   84.19 5072.69    83.8 5089.22   84.89
 5121.69   83.63  5151.2   85.01 5210.22   85.52 5254.49   84.37 5275.12      87
#Mann= 5 ,-1 , 0
 3691.15      .1       0 3973.19     .07       0 4885.66     .05       0
 4952.03     .04       0 5056.17     .07       0
#XS Ineff= 2 , 0
       0 4885.66    86.5               0
Permanent Ineff=
       F       F
#Block Obstruct= 2 , 0
       0 4885.66   84.25               0
Bank Sta=4952.03,5056.17
XS Rating Curve= 0 ,0
Exp/Cntr=0.5,0.3

Type RM Length L Ch R = 1 ,18730.9 ,220,220,220
BEGIN DESCRIPTION:
Upstream Section of Bridge
END DESCRIPTION:
XS GIS Cut Line= 4
      3114304.92     13917579.13      3114414.78     13916430.35
       3114422.2     13916340.48      3114422.67     13916284.58
#Sta/Elev= 27
  3755.9   93.59  3805.9   91.92  3955.9   88.75  4175.9   84.44  4195.9   84.71
  4343.4   84.71  4455.9   84.71  4825.9   84.66  4875.9   85.39  4900.1   84.29
  4901.2   84.12  4903.3   84.17  4931.7   84.12  4968.3   83.33  4980.7   82.78
  4987.7   81.39  4992.9   79.31    4995   78.88    5000   78.56  5003.7   78.78
  5007.1   79.06  5013.3   82.88  5017.9   83.54    5024   83.52  5026.1   83.79
  5049.9   84.19  5055.9    86.5
#Mann= 5 , 1 , 0
  3755.9      .2       0  3755.9      .1       0  4343.4     .07       0
  4980.7     .04       0  5013.3      .1       0
#XS Ineff= 2 , 0
       0    4945      88  5013.3       0    82.9
Permanent Ineff=
       F       F
Bank Sta=4980.7,5013.3
XS Rating Curve= 0 ,0
Exp/Cntr=0.5,0.3

Type RM Length L Ch R = 2 ,18620.9 ,,,
BEGIN DESCRIPTION:
HARDY TOLL ROAD 1
Structure ID: P40-11
END DESCRIPTION:
Bridge Culvert--1,0,-1,-1, 0
Deck Dist Width WeirC Skew NumUp NumDn MinLoCord MaxHiCord MaxSubmerge Is_Ogee
10,200,3,0, 38, 38, , , 0.95, 0, 1,1,,
  3595.5  3755.9  3805.9  3955.9  4175.9  4195.9  4343.4  4376.5  4446.5  4455.9
  4506.5  4825.9  4875.9  4900.1  4901.2  4903.3  4931.7  4944.3  4968.3  4980.7
  4984.7  4992.9  4993.9  4994.3    4995  4999.9    5000  5003.7  5007.1  5013.3
    5016  5017.9    5024  5025.6  5026.1  5041.5  5049.9  5055.9
      93    93.6   92.73   92.54   92.26   92.23   92.04      92    94.3   94.57
      96   97.39    97.6   97.71   97.71   97.72   97.85    97.9   91.76   88.58
   87.56   85.46    85.2    85.1   84.83    82.9    82.9   82.92   82.93   82.96
   83.28   83.55   83.53   83.74    83.8   84.06   84.19    86.5
      93   93.59   91.92   88.75   84.44   84.71   84.71   84.71   84.71   84.71
    84.7   84.66   85.39   84.29   84.12   84.17   84.12   83.85   83.33   82.78
   76.39   76.31   75.74   75.79   75.88   75.76   75.76   75.78   79.06   82.88
   83.27   83.54   83.52   83.73   83.79   84.05   84.19    86.5
  3595.5  3755.9  3805.9  3955.9  4175.9  4195.9  4343.4  4376.5  4446.5  4455.9
  4506.5  4825.9  4875.9  4900.1  4901.2  4903.3  4931.7  4944.3  4968.3  4980.7
  4984.7  4992.9  4993.9  4994.3    4995  4999.9    5000  5003.7  5007.1  5013.3
    5016  5017.9    5024  5025.6  5026.1  5041.5  5049.9  5055.9
      93    93.6   92.73   92.54   92.26   92.23   92.04      92    94.3   94.57
      96   97.39    97.6   97.71   97.71   97.72   97.85    97.9   91.76   88.58
   87.56   85.46    85.2    85.1   84.83    82.9    82.9   82.92   82.93   82.96
   83.28   83.55   83.53   83.74    83.8   84.06   84.19    86.5
    92.9   93.49   91.82   88.65   84.34   84.61   84.61   84.61   84.61   84.61
    84.6   84.56   85.29   84.19   84.02   84.07   84.02   83.75   83.23   82.68
   76.29   76.21   75.64   75.69   75.78   75.66   75.66   75.68   78.96   82.78
   83.17   83.44   83.42   83.63   83.69   83.95   84.09    86.4
BR Coef= 1 , 0 , 0 ,1.25, 0 ,,,0.8,-1,2,0,
WSPro=,,,, 1 ,,,, 0 ,,,, 0 ,,,,-1 ,-1 ,-1 , 0 , 0 , 0 , 0 , 0
Culvert=2,4,10,200,0.015,0.4,1,8,1,75.87,4988.8,75.8,4988.8,Culvert #1  , 0 ,10
Culvert Bottom n=0.015
Culvert=2,4,10,200,0.015,0.4,1,8,1,75.87,5000.2,75.8,5000.2,Culvert #2  , 0 ,10
Culvert Bottom n=0.015
BR U #Sta/Elev= 38
  3595.5      93  3755.9   93.59  3805.9   91.92  3955.9   88.75  4175.9   84.44
  4195.9   84.71  4343.4   84.71  4376.5   84.71  4446.5   84.71  4455.9   84.71
  4506.5    84.7  4825.9   84.66  4875.9   85.39  4900.1   84.29  4901.2   84.12
  4903.3   84.17  4931.7   84.12  4944.3   83.85  4968.3   83.33  4980.7   82.78
  4984.7   76.39  4992.9   76.31  4993.9   75.74  4994.3   75.79    4995   75.88
  4999.9   75.76    5000   75.76  5003.7   75.78  5007.1   79.06  5013.3   82.88
    5016   83.27  5017.9   83.54    5024   83.52  5025.6   83.73  5026.1   83.79
  5041.5   84.05  5049.9   84.19  5055.9    86.5
BR U #Mann= 5
  3595.5      .2  3755.9      .1  4343.4     .07  4980.7     .04  5013.3      .1
BR U Banks=4980.7,5013.3
BR D #Sta/Elev= 38
  3595.5    92.9  3755.9   93.49  3805.9   91.82  3955.9   88.65  4175.9   84.34
  4195.9   84.61  4343.4   84.61  4376.5   84.61  4446.5   84.61  4455.9   84.61
  4506.5    84.6  4825.9   84.56  4875.9   85.29  4900.1   84.19  4901.2   84.02
  4903.3   84.07  4931.7   84.02  4944.3   83.75  4968.3   83.23  4980.7   82.68
  4984.7   76.29  4992.9   76.21  4993.9   75.64  4994.3   75.69    4995   75.78
  4999.9   75.66    5000   75.66  5003.7   75.68  5007.1   78.96  5013.3   82.78
    5016   83.17  5017.9   83.44    5024   83.42  5025.6   83.63  5026.1   83.69
  5041.5   83.95  5049.9   84.09  5055.9    86.4
BR D #Mann= 5
  3595.5      .2  3755.9      .1  4343.4     .07  4980.7     .04  5013.3      .1
BR D Banks=4980.7,5013.3
BC Design=,, 0 ,, 0 ,,,,,,
BC HTab HWMax=93.59
BC Use User HTab Curves=0
BC User HTab FreeFlow(D)= 0

Type RM Length L Ch R = 1 ,18510.9 ,59.6,59.6,59.6
BEGIN DESCRIPTION:
Downstream Section of Bridge
END DESCRIPTION:
XS GIS Cut Line= 3
      3114562.48     13917597.45      3114641.58     13916355.87
      3114641.54     13916299.97
#Sta/Elev= 27
  3755.9   93.59  3805.9   91.92  3955.9   88.75  4175.9   84.44  4195.9   84.71
  4343.4   84.71  4455.9   84.71  4825.9   84.66  4875.9   85.39  4900.1   83.29
  4901.2   83.12  4903.3   83.17  4931.7   83.12  4968.3   82.33  4980.7   81.78
  4987.7   80.39  4992.9   78.31    4995   77.88    5000    77.3  5003.7   77.78
  5007.1   78.06  5013.3   81.88  5017.9   82.54    5024   82.52  5026.1   82.79
  5049.9   84.19  5055.9    86.5
#Mann= 5 , 1 , 0
  3755.9      .2       0  3755.9      .1       0  4343.4     .07       0
  4980.7     .04       0  5013.3      .1       0
#XS Ineff= 2 , 0
       0    4945      88  5013.3       0    82.9
Permanent Ineff=
       F       F
Bank Sta=4980.7,5013.3
XS Rating Curve= 0 ,0
Exp/Cntr=0.5,0.3

Type RM Length L Ch R = 1 ,18451.3 ,53,53,53
BEGIN DESCRIPTION:
Upstream Section of Bridge/Culvert/Weir
END DESCRIPTION:
XS GIS Cut Line= 5
      3114578.06     13919165.43      3114699.87     13916419.41
      3114704.96     13916342.22      3114710.72      13916257.1
      3114712.67     13916228.26
#Sta/Elev= 30
    2190    91.7    2220    88.3    2250    86.3    2280    85.8    2340    86.6
    2370    85.6    2390    87.1  2546.5   86.31    2930    84.6    2950      86
    2970    84.6    3230    85.9    3520    85.7    3630    84.2    3690      85
    3710    84.2    3750    85.2    4330    84.8  4949.2    85.8  4979.2   84.77
  4990.9   81.34  4995.6   78.17  5000.9   77.29  5003.4   77.46  5011.8   81.98
  5029.5   83.74  5074.1    84.4  5110.2   83.51  5126.9   84.71  5130.3      87
#Mann= 5 , 1 , 0
    2190      .2       0  2546.5     .07       0  4990.9     .04       0
  5011.8      .1       0  5110.2     .14       0
#XS Ineff= 2 , 0
       0    4890      87               0
Permanent Ineff=
       F       F
Bank Sta=4990.9,5011.8
XS Rating Curve= 0 ,0
Exp/Cntr=0.5,0.3

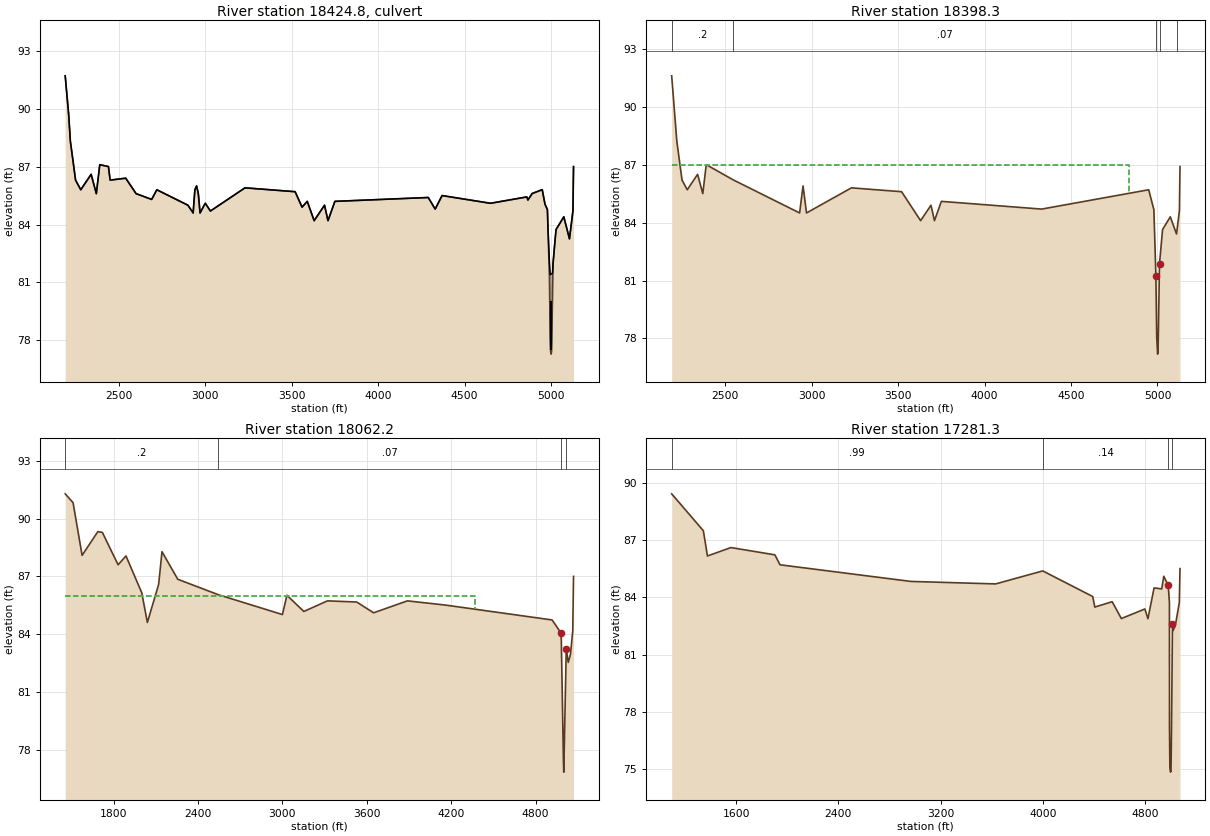
Type RM Length L Ch R = 2 ,18424.8 ,,,
BEGIN DESCRIPTION:
Access Road 5
Structure ID: P40-10
END DESCRIPTION:
Bridge Culvert--1,0,-1,-1, 0
Deck Dist Width WeirC Skew NumUp NumDn MinLoCord MaxHiCord MaxSubmerge Is_Ogee
10,33,3,0, 55, 55, , , 0.95, 0, 1,1,,
    2190    2210    2220    2250    2280    2340    2370    2390    2440    2450
    2540    2600    2690    2720    2900    2930    2940    2950    2960    2970
    3000    3030    3230    3520    3560    3590    3630    3690    3710    3750
    4290    4330    4370    4650  4859.8  4866.5  4891.1  4949.2  4965.4  4979.2
  4982.3  4990.9  4995.7  4997.9  5000.9  5003.4  5004.5  5008.9  5011.8  5023.8
  5029.5  5074.1  5106.8  5126.9  5130.3
    91.7    89.7    88.3    86.3    85.8    86.6    85.6    87.1      87    86.3
    86.4    85.6    85.3    85.8      85    84.6    85.8      86    85.6    84.6
    85.1    84.7    85.9    85.7    84.9    85.2    84.2      85    84.2    85.2
    85.4    84.8    85.5    85.1   85.43   85.27   85.61   85.81   85.05   84.78
   83.87   82.05    81.4   81.42   81.44   81.45   81.46   81.49   81.99   83.24
   83.75    84.4   83.26   84.71      87
    91.7    89.7    88.3    86.3    85.8    86.6    85.6    87.1      87    86.3
    86.4    85.6    85.3    85.8      85    84.6    85.8      86    85.6    84.6
    85.1    84.7    85.9    85.7    84.9    85.2    84.2      85    84.2    85.2
    85.4    84.8    85.5    85.1   85.43   85.27    85.6    85.8   85.04   84.77
   83.86   81.34   78.14   77.43   77.29   77.46   78.14   80.45   81.98   83.23
   83.74    84.4   83.26   84.71      87
    2190    2210    2220    2250    2280    2340    2370    2390    2440    2450
    2540    2600    2690    2720    2900    2930    2940    2950    2960    2970
    3000    3030    3230    3520    3560    3590    3630    3690    3710    3750
    4290    4330    4370    4650  4859.8  4866.5  4891.1  4949.2  4965.4  4979.2
  4982.3  4990.9  4995.7  4997.9  5000.9  5003.4  5004.5  5008.9  5011.8  5023.8
  5029.5  5074.1  5106.8  5126.9  5130.3
    91.7    89.7    88.3    86.3    85.8    86.6    85.6    87.1      87    86.3
    86.4    85.6    85.3    85.8      85    84.6    85.8      86    85.6    84.6
    85.1    84.7    85.9    85.7    84.9    85.2    84.2      85    84.2    85.2
    85.4    84.8    85.5    85.1   85.43   85.27   85.61   85.81   85.05   84.78
   83.87   82.05    81.4   81.42   81.44   81.45   81.46   81.49   81.99   83.24
   83.75    84.4   83.26   84.71      87
   91.61   89.61   88.21   86.21   85.71   86.51   85.51   87.01   86.91   86.21
   86.31   85.51   85.21   85.71   84.91   84.51   85.71   85.91   85.51   84.51
   85.01   84.61   85.81   85.61   84.81   85.11   84.11   84.91   84.11   85.11
   85.31   84.71   85.41   85.01   85.34   85.18   85.51   85.71   84.95   84.68
   83.77   81.25   78.05   77.34    77.2   77.37   78.05   80.36   81.89   83.14
   83.65   84.31   83.17   84.62   86.91
BR Coef= 1 , 0 , 0 ,1.25, 0 ,,,0.8,-1,2,0,
WSPro=,,,, 1 ,,,, 0 ,,,, 0 ,,,,-1 ,-1 ,-1 , 0 , 0 , 0 , 0 , 0
Culvert=1,2.5,,33,0.024,0.5,1,1,3,77.53,4998,77.44,4998,Culvert #1  , 0 ,10
Culvert Bottom n=0.024
Culvert=1,2.5,,33,0.024,0.5,1,1,3,77.53,5001.7,77.38,5001.7,Culvert #2  , 0 ,10
Culvert Bottom n=0.024
BR U #Sta/Elev= 62
    2190    91.7    2210    89.7    2220    88.3    2250    86.3    2280    85.8
    2340    86.6    2370    85.6    2390    87.1    2440      87    2450    86.3
    2540    86.4  2546.5   86.31    2600    85.6    2690    85.3    2720    85.8
    2900      85    2930    84.6    2940    85.8    2950      86    2960    85.6
    2970    84.6    3000    85.1    3030    84.7    3230    85.9    3520    85.7
    3560    84.9    3590    85.2    3630    84.2    3690      85    3710    84.2
    3750    85.2    4290    85.4    4330    84.8    4370    85.5    4650    85.1
  4859.8   85.43  4866.3   85.27  4866.4   85.27  4866.5   85.27  4891.1    85.6
  4949.2    85.8  4965.4   85.04  4979.2   84.77  4982.3   83.86  4990.9   81.34
  4995.6   78.17  4995.7   78.14  4997.9   77.43  5000.9   77.29  5003.4   77.46
  5004.5   78.14  5008.9   80.45  5011.8   81.98  5022.5   83.09  5023.8   83.23
  5029.5   83.74  5041.6   83.92  5074.1    84.4  5106.8   83.26  5110.2   83.51
  5126.9   84.71  5130.3      87
BR U #Mann= 5
    2190      .2  2546.5     .07  4990.9     .04  5011.8      .1  5110.2     .14
BR U Banks=4990.9,5011.8
BR D #Sta/Elev= 62
    2190   91.61    2210   89.61    2220   88.21    2250   86.21    2280   85.71
    2340   86.51    2370   85.51    2390   87.01    2440   86.91    2450   86.21
    2540   86.31  2546.5   86.22    2600   85.51    2690   85.21    2720   85.71
    2900   84.91    2930   84.51    2940   85.71    2950   85.91    2960   85.51
    2970   84.51    3000   85.01    3030   84.61    3230   85.81    3520   85.61
    3560   84.81    3590   85.11    3630   84.11    3690   84.91    3710   84.11
    3750   85.11    4290   85.31    4330   84.71    4370   85.41    4650   85.01
  4859.8   85.34  4866.3   85.18  4866.4   85.18  4866.5   85.18  4891.1   85.51
  4949.2   85.71  4965.4   84.95  4979.2   84.68  4982.3   83.77  4990.9   81.25
  4995.6   78.08  4995.7   78.05  4997.9   77.34  5000.9    77.2  5003.4   77.37
  5004.5   78.05  5008.9   80.36  5011.8   81.89  5022.5      83  5023.8   83.14
  5029.5   83.65  5041.6   83.83  5074.1   84.31  5106.8   83.17  5110.2   83.42
  5126.9   84.62  5130.3   86.91
BR D #Mann= 5
    2190      .2  2546.5     .07  4990.9     .04  5011.8      .1  5110.2     .14
BR D Banks=4990.9,5011.8
BC Design=,, 0 ,, 0 ,,,,,,
BC HTab HWMax=91.7
BC Use User HTab Curves=0
BC User HTab FreeFlow(D)= 0

Type RM Length L Ch R = 1 ,18398.3 ,336.1,336.1,336.1
BEGIN DESCRIPTION:
Downstream Section of Bridge/Culvert/Weir
END DESCRIPTION:
XS GIS Cut Line= 5
      3114630.98     13919168.33      3114752.79     13916422.31
      3114757.88     13916345.12      3114763.64       13916260.
       3114765.6     13916231.16
#Sta/Elev= 30
    2190    91.6    2220    88.2    2250    86.2    2280    85.7    2340    86.5
    2370    85.5    2390      87  2546.5   86.21    2930    84.5    2950    85.9
    2970    84.5    3230    85.8    3520    85.6    3630    84.1    3690    84.9
    3710    84.1    3750    85.1    4330    84.7  4949.2    85.7  4979.2   84.67
  4990.9   81.24  4995.6   78.07  5000.9   77.19  5003.4   77.36  5011.8   81.88
  5029.5   83.64  5074.1    84.3  5110.2   83.41  5126.9   84.61  5130.3    86.9
#Mann= 5 , 1 , 0
    2190      .2       0  2546.5     .07       0  4990.9     .04       0
  5011.8      .1       0  5110.2     .14       0
#XS Ineff= 2 , 0
       0    4838      87               0
Permanent Ineff=
       F       F
Bank Sta=4990.9,5011.8
XS Rating Curve= 0 ,0
Exp/Cntr=0.5,0.3

Type RM Length L Ch R = 1 ,18062.2 ,831.4,780.9,778.8
BEGIN DESCRIPTION:
Cross Section  18062.2
END DESCRIPTION:
XS GIS Cut Line= 6
      3114988.25     13919915.78      3115049.79     13916555.26
      3115084.89     13916461.69      3115089.61     13916379.36
      3115089.62     13916379.32      3115093.77     13916309.97
#Sta/Elev= 30
  1456.5   91.28  1512.5   90.82  1576.5   88.09  1688.5   89.32  1720.5   89.28
  1832.5    87.6  1888.5   88.06  2000.5   86.15  2040.5   84.61  2120.5   86.58
  2144.5   88.28  2256.5   86.85  2544.4   86.05  3000.5   85.02  3032.5   86.02
  3152.5   85.18  3320.5   85.73  3528.5   85.67  3648.5   85.11  3888.5   85.73
  4160.5   85.51  4917.5   84.74  4981.8   84.05  4997.8   77.39  5000.2   76.85
  5017.8   83.23    5032   82.54    5048   82.97    5064   84.19  5069.5      87
#Mann= 4 , 1 , 0
  1456.5      .2       0  2544.4     .07       0  4981.8     .04       0
  5017.8      .1       0
#XS Ineff= 2 , 0
       0    4370      86               0
Permanent Ineff=
       F       F
Bank Sta=4981.8,5017.8
XS Rating Curve= 0 ,0
Exp/Cntr=0.3,0.1

Type RM Length L Ch R = 1 ,17281.3 ,152.3,105.5,99.4
BEGIN DESCRIPTION:
Cross Section 17281.3-Interpolated
END DESCRIPTION:
XS GIS Cut Line= 4
      3115832.36     13920319.06      3115867.68     13916531.08
       3115870.4     13916377.51      3115871.12     13916340.26
#Sta/Elev= 30
  1095.3   89.41  1343.3   87.48  1375.3   86.16  1559.3    86.6  1903.3   86.22
  1943.3    85.7  2967.3   84.83  3631.3    84.7    4000   85.38  4391.3   84.04
  4407.3   83.49  4543.3   83.77  4615.3   82.89  4799.3   83.39  4823.3   82.88
  4871.3   84.49  4931.4   84.44  4947.4    85.1  4982.6   84.62  4991.5   83.71
  4992.1   77.18    4995   75.11  4999.7   74.86    5004   74.91  5007.9   77.16
  5015.4   82.63  5019.4   82.26    5037    82.5    5069   83.72  5074.3    85.5
#Mann= 4 , 1 , 0
  1095.3     .99       0    4000     .14       0  4982.6     .04       0
  5015.4      .1       0
#XS Ineff= 2 , 0
       0  4947.4    85.1               0
Permanent Ineff=
       F       F
Bank Sta=4982.6,5015.4
XS Rating Curve= 0 ,0
Exp/Cntr=0.5,0.3