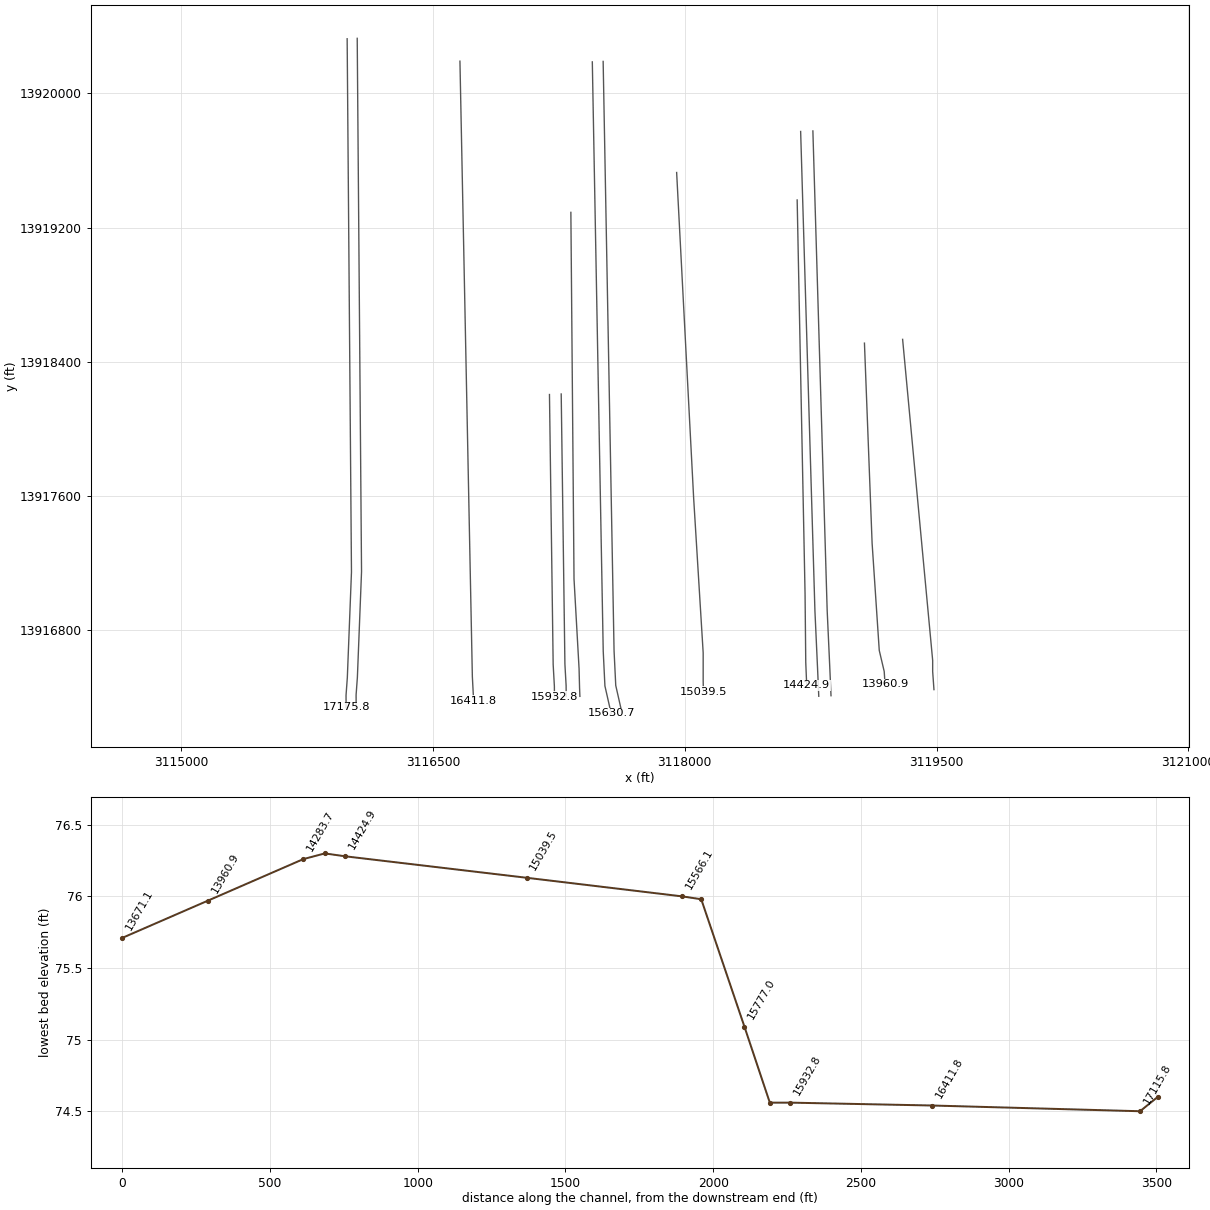
HEC-RAS study P140-00-00.prj: P140-00-00 (Hoods Bayou)

--- P140-00-00.g01 (geometry) --- (continued)

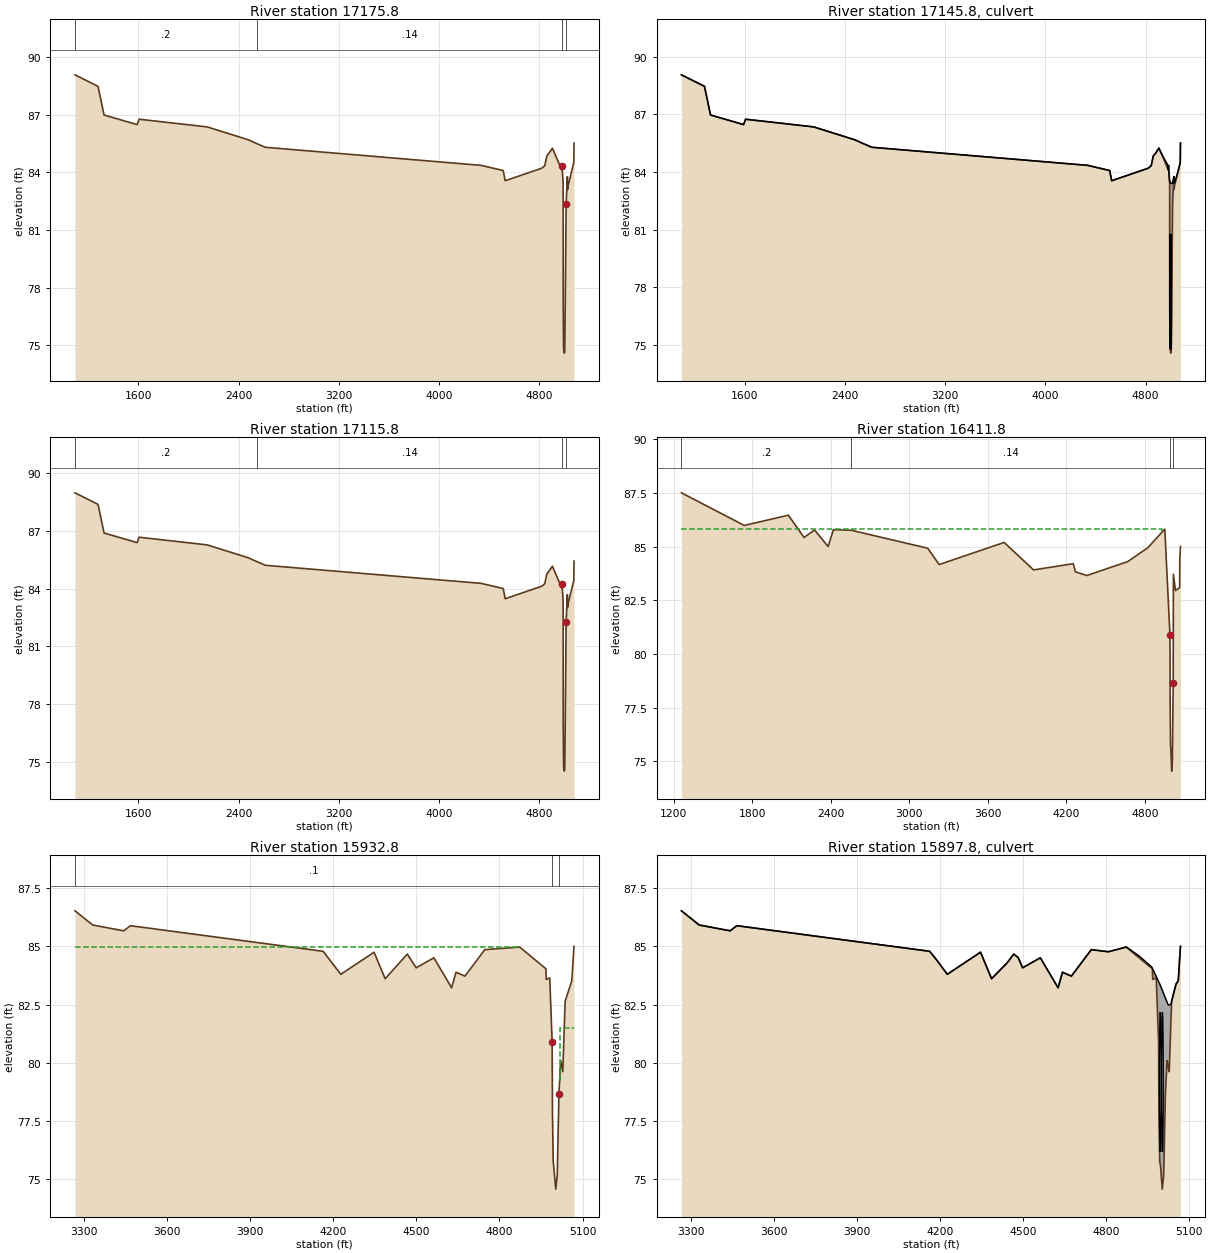
Type RM Length L Ch R = 1 ,17175.8 ,60,60,60
BEGIN DESCRIPTION:
Upstream Section of Bridge/Culvert/Weir
END DESCRIPTION:
XS GIS Cut Line= 5
      3115988.84     13920324.35      3116014.57     13917147.56
      3115989.85     13916518.75      3115982.19     13916413.64
      3115982.43     13916341.32
#Sta/Elev= 30
  1094.2   89.08  1278.2   88.48  1326.2   86.99  1590.2   86.49  1606.2   86.77
  2150.2   86.37  2478.2    85.7  2546.3    85.5  2614.2   85.31  4336.9   84.37
  4512.9    84.1  4528.9   83.57  4820.8   84.22  4844.8   84.35  4860.8   84.85
    4906   85.26  4979.8   84.14  4982.6   84.36  4991.5   83.45  4992.1   76.92
    4995   74.85  4999.7    74.6    5004   74.65  5007.9    76.9  5015.4   82.37
  5025.1   83.78  5026.4   83.11    5032   83.34  5076.6   84.52  5078.1   85.53
#Mann= 4 , 1 , 0
  1094.2      .2       0  2546.3     .14       0  4982.6     .04       0
  5015.4      .1       0
#XS Ineff= 2 , 0
       0    4906   85.23    5017       0      82
Permanent Ineff=
       F       F
Bank Sta=4982.6,5015.4
XS Rating Curve= 0 ,0
Exp/Cntr=0.5,0.3

Type RM Length L Ch R = 2 ,17145.8 ,,,
BEGIN DESCRIPTION:
Access Road 4
Structure ID: P40-9,,,,
END DESCRIPTION:
Bridge Culvert--1,0,-1,-1, 0
Deck Dist Width WeirC Skew NumUp NumDn MinLoCord MaxHiCord MaxSubmerge Is_Ogee
10,40,3,0, 39, 39, , , 0.95, 0, 1,1,,
  1094.2  1278.2  1326.2  1590.2  1606.2  2150.2  2478.2  2546.3  2614.2  4336.9
  4512.9  4528.9  4820.8    4843  4844.8  4860.8  4880.2    4906  4932.5    4973
  4979.8  4982.6    4983  4991.5  4992.1    4993    4995  4999.7    5003    5004
  5007.9    5013  5015.4  5025.1  5026.4    5032    5053  5076.6  5078.1
   89.05   88.45   86.96   86.46   86.74   86.34   85.67   85.47   85.28   84.34
   84.07   83.54   84.19   84.32   84.33   84.83   84.98   85.24   84.87    84.4
   84.12   84.34    84.3    83.5    83.5    83.5   83.48   83.43    83.4    83.4
    83.4    83.4   83.41   83.76   83.43   83.45   83.88   84.49    85.5
   89.05   88.45   86.96   86.46   86.74   86.34   85.67   85.47   85.28   84.34
   84.07   83.54   84.19   84.31   84.32   84.82   84.97   85.23   84.86   84.22
   84.11   84.33   84.29   83.42   76.89   76.25   74.82   74.57   74.61   74.62
   76.87   80.59   82.34   83.75   83.08   83.31   83.87   84.49    85.5
  1094.2  1278.2  1326.2  1590.2  1606.2  2150.2  2478.2  2546.3  2614.2  4336.9
  4512.9  4528.9  4820.8    4843  4844.8  4860.8  4880.2    4906  4932.5    4973
  4979.8  4982.6    4983  4991.5  4992.1    4993    4995  4999.7    5003    5004
  5007.9    5013  5015.4  5025.1  5026.4    5032    5053  5076.6  5078.1
   89.05   88.45   86.96   86.46   86.74   86.34   85.67   85.47   85.28   84.34
   84.07   83.54   84.19   84.32   84.33   84.83   84.98   85.24   84.87    84.4
   84.12   84.34    84.3    83.5    83.5    83.5   83.48   83.43    83.4    83.4
    83.4    83.4   83.41   83.76   83.43   83.45   83.88   84.49    85.5
   88.98   88.38   86.89   86.39   86.67   86.27    85.6    85.4   85.21   84.27
      84   83.47   84.12   84.24   84.25   84.75    84.9   85.16   84.79   84.15
   84.04   84.26   84.22   83.35   76.82   76.18   74.75    74.5   74.54   74.55
    76.8   80.52   82.27   83.68   83.01   83.24    83.8   84.42   85.43
BR Coef= 1 , 0 , 0 ,1.25, 0 ,,,0.8,-1,2,0,
WSPro=,,,, 1 ,,,, 0 ,,,, 0 ,,,,-1 ,-1 ,-1 , 0 , 0 , 0 , 0 , 0
Culvert=1,6,,40,0.024,0.5,1,1,3,74.78,4995.2,74.7,4995.2,Culvert #1  , 0 ,10
Culvert Bottom n=0.024
Culvert=1,6,,40,0.024,0.5,1,1,3,74.75,5003.8,74.65,5003.8,Culvert #2  , 0 ,10
Culvert Bottom n=0.024
BR U #Sta/Elev= 39
  1094.2   89.05  1278.2   88.45  1326.2   86.96  1590.2   86.46  1606.2   86.74
  2150.2   86.34  2478.2   85.67  2546.3   85.47  2614.2   85.28  4336.9   84.34
  4512.9   84.07  4528.9   83.54  4820.8   84.19    4843   84.31  4844.8   84.32
  4860.8   84.82  4880.2   84.97    4906   85.23  4932.5   84.86    4973   84.22
  4979.8   84.11  4982.6   84.33    4983   84.29  4991.5   83.42  4992.1   76.89
    4993   76.25    4995   74.82  4999.7   74.57    5003   74.61    5004   74.62
  5007.9   76.87    5013   80.59  5015.4   82.34  5025.1   83.75  5026.4   83.08
    5032   83.31    5053   83.87  5076.6   84.49  5078.1    85.5
BR U #Mann= 4
  1094.2      .2  2546.3     .14  4982.6     .04  5015.4      .1
BR U Banks=4982.6,5015.4
BR D #Sta/Elev= 39
  1094.2   88.98  1278.2   88.38  1326.2   86.89  1590.2   86.39  1606.2   86.67
  2150.2   86.27  2478.2    85.6  2546.3    85.4  2614.2   85.21  4336.9   84.27
  4512.9      84  4528.9   83.47  4820.8   84.12    4843   84.24  4844.8   84.25
  4860.8   84.75  4880.2    84.9    4906   85.16  4932.5   84.79    4973   84.15
  4979.8   84.04  4982.6   84.26    4983   84.22  4991.5   83.35  4992.1   76.82
    4993   76.18    4995   74.75  4999.7    74.5    5003   74.54    5004   74.55
  5007.9    76.8    5013   80.52  5015.4   82.27  5025.1   83.68  5026.4   83.01
    5032   83.24    5053    83.8  5076.6   84.42  5078.1   85.43
BR D #Mann= 4
  1094.2      .2  2546.3     .14  4982.6     .04  5015.4      .1
BR D Banks=4982.6,5015.4
BC Design=,, 0 ,, 0 ,,,,,,
BC HTab HWMax=89.08
BC Use User HTab Curves=0
BC User HTab FreeFlow(D)= 0

Type RM Length L Ch R = 1 ,17115.8 ,704,704,704
BEGIN DESCRIPTION:
Downstream Section of Bridge/Culvert/Weir
END DESCRIPTION:
XS GIS Cut Line= 5
      3116048.78     13920326.93      3116074.51     13917150.14
      3116049.79     13916521.33      3116042.13     13916416.22
      3116042.37      13916343.9
#Sta/Elev= 30
  1094.2   88.98  1278.2   88.38  1326.2   86.89  1590.2   86.39  1606.2   86.67
  2150.2   86.27  2478.2    85.6  2546.3    85.4  2614.2   85.21  4336.9   84.27
  4512.9      84  4528.9   83.47  4820.8   84.12  4844.8   84.25  4860.8   84.75
    4906   85.16  4979.8   84.04  4982.6   84.26  4991.5   83.35  4992.1   76.82
    4995   74.75  4999.7    74.5    5004   74.55  5007.9    76.8  5015.4   82.27
  5025.1   83.68  5026.4   83.01    5032   83.24  5076.6   84.42  5078.1   85.43
#Mann= 4 , 1 , 0
  1094.2      .2       0  2546.3     .14       0  4982.6     .04       0
  5015.4      .1       0
#XS Ineff= 2 , 0
       0    4906   85.16    5017       0      82
Permanent Ineff=
       F       F
Bank Sta=4982.6,5015.4
XS Rating Curve= 0 ,0
Exp/Cntr=0.5,0.3

Type RM Length L Ch R = 1 ,16411.8 ,771.2,479,476.2
BEGIN DESCRIPTION:
Cross Section 16411.8-Interpolated
END DESCRIPTION:
XS GIS Cut Line= 4
      3116660.66      13920190.9       3116734.6     13916525.16
      3116738.88     13916443.86      3116742.15     13916381.84
#Sta/Elev= 30
  1260.2    87.5  1740.2   85.98  2076.2   86.46  2196.2   85.42  2276.2   85.77
  2380.2      85  2420.2   85.78  2554.4   85.76  3140.2   84.92  3228.2   84.16
  3724.2   85.19  3948.2   83.91  4252.2    84.2  4268.2   83.82  4356.2   83.65
  4668.2    84.3  4820.2   84.94  4950.7   85.81  4990.1   80.88  4991.4   77.73
  4994.1   75.74  4997.2   75.52  5003.3   74.54  5008.6   75.13  5014.7   78.64
  5016.1   83.71  5032.1   82.95  5064.1   83.09  5065.2    84.4  5070.2      85
#Mann= 4 , 1 , 0
  1260.2      .2       0  2554.4     .14       0  4990.1     .04       0
  5014.7      .1       0
#XS Ineff= 2 , 0
       0  4926.7   85.82               0
Permanent Ineff=
       F       F
Bank Sta=4990.1,5014.7
XS Rating Curve= 0 ,0
Exp/Cntr=0.5,0.3

Type RM Length L Ch R = 1 ,15932.8 ,70,70,70
BEGIN DESCRIPTION:
Upstream Section of Bridge/Culvert/Weir
END DESCRIPTION:
XS GIS Cut Line= 4
      3117193.94     13918205.35      3117215.98     13916596.36
       3117223.2     13916467.99      3117223.71      13916403.7
#Sta/Elev= 30
  3267.1   86.53  3331.1   85.92  3443.1   85.67  3467.1   85.89  4163.1   84.79
  4227.1    83.8  4347.1   84.75  4387.1   83.61  4467.1   84.67  4499.1   84.08
  4563.1   84.51  4627.1   83.22  4643.1   83.89  4675.1   83.72  4747.1   84.86
  4873.1   84.97  4967.5   84.04    4969   83.58  4981.6   83.64  4990.1    80.9
  4991.4   77.75  4994.1   75.76  5003.3   74.56  5008.6   75.15  5014.7   78.66
  5020.9   80.09  5028.6   79.61  5037.1   82.64  5061.1   83.52  5069.1      85
#Mann= 3 , 1 , 0
  3267.1      .1       0  4990.1     .04       0  5014.7      .1       0
#XS Ineff= 2 , 0
       0  4873.1   84.98    5017       0    81.5
Permanent Ineff=
       F       F
Bank Sta=4990.1,5014.7
XS Rating Curve= 0 ,0
Exp/Cntr=0.5,0.3

Type RM Length L Ch R = 2 ,15897.8 ,,,
BEGIN DESCRIPTION:
Access Road 3
Structure ID: P40-8,,,,
END DESCRIPTION:
Bridge Culvert--1,0,-1,-1, 0
Deck Dist Width WeirC Skew NumUp NumDn MinLoCord MaxHiCord MaxSubmerge Is_Ogee
10,50,3,0, 42, 42, , , 0.95, 0, 1,1,,
  3267.1  3331.1  3443.1  3467.1  4163.1  4187.1  4227.1  4347.1  4387.1  4443.1
  4467.1  4483.1  4499.1  4563.1  4627.1  4643.1  4675.1  4747.1  4808.5    4873
  4873.1  4920.7  4965.5  4967.5    4969  4981.6  4990.1  4991.4  4994.1  4994.7
  4997.2  5003.3  5008.6  5014.7  5020.9  5024.8  5028.6  5035.3  5037.1  5053.1
  5061.1  5069.1
   86.53   85.92   85.67   85.89   84.79   84.44    83.8   84.75   83.61   84.29
   84.67   84.52   84.08   84.51   83.22   83.89   83.72   84.86   84.77   84.97
   84.98   84.58   84.11   84.06   84.02    83.7   83.49   83.45   83.39   83.37
    83.3   83.12   82.96   82.78    82.6   82.48   82.49    82.5   82.64   83.38
   83.52      85
   86.53   85.92   85.67   85.89   84.79   84.44    83.8   84.75   83.61   84.29
   84.67   84.52   84.08   84.51   83.22   83.89   83.72   84.86   84.77   84.97
   84.97    84.5   84.06   84.04   83.58   83.64    80.9   77.75   75.76   75.72
   75.54   74.56   75.15   78.66   80.09   79.85   79.61      82   82.64   83.38
   83.52      85
  3267.1  3331.1  3443.1  3467.1  4163.1  4187.1  4227.1  4347.1  4387.1  4443.1
  4467.1  4483.1  4499.1  4563.1  4627.1  4643.1  4675.1  4747.1  4808.5    4873
  4873.1  4920.7  4965.5  4967.5    4969  4981.6  4990.1  4991.4  4994.1  4994.7
  4997.2  5003.3  5008.6  5014.7  5020.9  5024.8  5028.6  5035.3  5037.1  5053.1
  5061.1  5069.1
   86.53   85.92   85.67   85.89   84.79   84.44    83.8   84.75   83.61   84.29
   84.67   84.52   84.08   84.51   83.22   83.89   83.72   84.86   84.77   84.97
   84.98   84.58   84.11   84.06   84.02    83.7   83.49   83.45   83.39   83.37
    83.3   83.12   82.96   82.78    82.6   82.48   82.49    82.5   82.64   83.38
   83.52      85
   86.47   85.86   85.61   85.83   84.73   84.38   83.74   84.69   83.55   84.23
   84.61   84.46   84.02   84.45   83.16   83.83   83.66    84.8   84.71   84.91
   84.91   84.44      84   83.98   83.52   83.58   80.84   77.69    75.7   75.66
   75.48    74.5   75.09    78.6   80.03   79.79   79.55   81.94   82.58   83.32
   83.46   84.94
BR Coef= 1 , 0 , 0 ,1.25, 0 ,,,0.8,-1,2,0,
WSPro=,,,, 1 ,,,, 0 ,,,, 0 ,,,,-1 ,-1 ,-1 , 0 , 0 , 0 , 0 , 0
Culvert=1,6,,50,0.024,0.5,1,1,3,76.17,4996.3,75.86,4996.3,Culvert #1  , 0 ,10
Culvert Bottom n=0.024
Culvert=1,6,,50,0.024,0.5,1,1,3,76.16,5003.9,75.63,5003.9,Culvert #2  , 0 ,10
Culvert Bottom n=0.024
BR U #Sta/Elev= 42
  3267.1   86.53  3331.1   85.92  3443.1   85.67  3467.1   85.89  4163.1   84.79
  4187.1   84.44  4227.1    83.8  4347.1   84.75  4387.1   83.61  4443.1   84.29
  4467.1   84.67  4483.1   84.52  4499.1   84.08  4563.1   84.51  4627.1   83.22
  4643.1   83.89  4675.1   83.72  4747.1   84.86  4808.5   84.77    4873   84.97
  4873.1   84.97  4920.7    84.5  4965.5   84.06  4967.5   84.04    4969   83.58
  4981.6   83.64  4990.1    80.9  4991.4   77.75  4994.1   75.76  4994.7   75.72
  4997.2   75.54  5003.3   74.56  5008.6   75.15  5014.7   78.66  5020.9   80.09
  5024.8   79.85  5028.6   79.61  5035.3      82  5037.1   82.64  5053.1   83.38
  5061.1   83.52  5069.1      85
BR U #Mann= 3
  3267.1      .1  4990.1     .04  5014.7      .1
BR U Banks=4990.1,5014.7
BR D #Sta/Elev= 42
  3267.1   86.47  3331.1   85.86  3443.1   85.61  3467.1   85.83  4163.1   84.73
  4187.1   84.38  4227.1   83.74  4347.1   84.69  4387.1   83.55  4443.1   84.23
  4467.1   84.61  4483.1   84.46  4499.1   84.02  4563.1   84.45  4627.1   83.16
  4643.1   83.83  4675.1   83.66  4747.1    84.8  4808.5   84.71    4873   84.91
  4873.1   84.91  4920.7   84.44  4965.5      84  4967.5   83.98    4969   83.52
  4981.6   83.58  4990.1   80.84  4991.4   77.69  4994.1    75.7  4994.7   75.66
  4997.2   75.48  5003.3    74.5  5008.6   75.09  5014.7    78.6  5020.9   80.03
  5024.8   79.79  5028.6   79.55  5035.3   81.94  5037.1   82.58  5053.1   83.32
  5061.1   83.46  5069.1   84.94
BR D #Mann= 3
  3267.1      .1  4990.1     .04  5014.7      .1
BR D Banks=4990.1,5014.7
BC Design=,, 0 ,, 0 ,,,,,,
BC HTab HWMax=86.53
BC Use User HTab Curves=0
BC User HTab FreeFlow(D)= 0

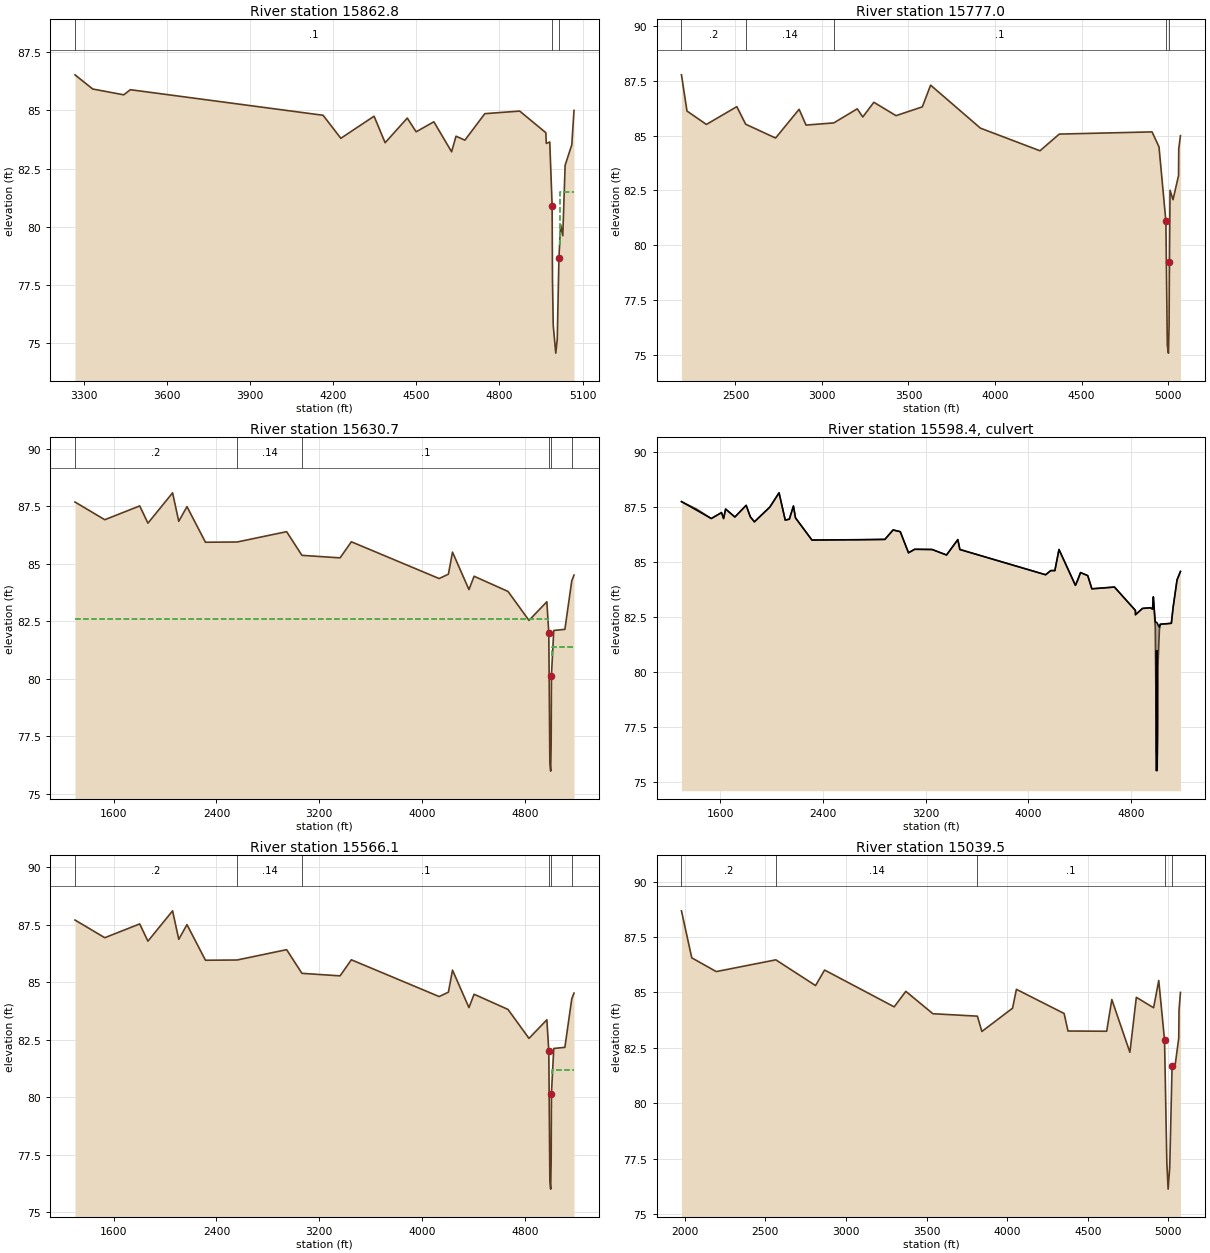
Type RM Length L Ch R = 1 ,15862.8 ,85.8,85.8,85.8
BEGIN DESCRIPTION:
Downstream Section of Bridge/Culvert/Weir
END DESCRIPTION:
XS GIS Cut Line= 4
      3117263.88     13918208.36      3117285.92     13916599.38
      3117293.14     13916471.01      3117293.64     13916406.71
#Sta/Elev= 30
  3267.1   86.53  3331.1   85.92  3443.1   85.67  3467.1   85.89  4163.1   84.79
  4227.1    83.8  4347.1   84.75  4387.1   83.61  4467.1   84.67  4499.1   84.08
  4563.1   84.51  4627.1   83.22  4643.1   83.89  4675.1   83.72  4747.1   84.86
  4873.1   84.97  4967.5   84.04    4969   83.58  4981.6   83.64  4990.1    80.9
  4991.4   77.75  4994.1   75.76  5003.3   74.56  5008.6   75.15  5014.7   78.66
  5020.9   80.09  5028.6   79.61  5037.1   82.64  5061.1   83.52  5069.1      85
#Mann= 3 , 1 , 0
  3267.1      .1       0  4990.1     .04       0  5014.7      .1       0
#XS Ineff= 2 , 0
       0  4873.1    84.9    5017       0    81.5
Permanent Ineff=
       F       F
Bank Sta=4990.1,5014.7
XS Rating Curve= 0 ,0
Exp/Cntr=0.5,0.3

Type RM Length L Ch R = 1 ,15777.0 ,157.6,146.3,143.9
BEGIN DESCRIPTION:
Cross Section 15777.0-Interpolated
END DESCRIPTION:
XS GIS Cut Line= 5
      3117321.41     13919290.38      3117340.18     13917106.76
       3117370.3     13916571.33       3117373.2     13916458.43
      3117375.16     13916407.38
#Sta/Elev= 30
  2187.9   87.77  2219.9   86.12  2331.9   85.51  2507.9   86.32    2559   85.52
  2731.9   84.89  2867.9    86.2  2907.9   85.48  3068.4   85.58  3203.9   86.22
  3235.9   85.85  3299.9   86.52  3427.9   85.91  3579.9   86.31  3627.9    87.3
  3915.9   85.34  4259.9   84.31  4371.6   85.07  4907.6   85.17  4947.8   84.49
  4987.7    81.1  4995.9   75.45  5002.4   75.09  5006.2   76.36  5008.2   79.25
  5011.8   82.51  5028.8   82.08  5060.8   83.18  5061.9    84.4  5071.9      85
#Mann= 5 , 1 , 0
  2187.9      .2       0    2559     .14       0  3068.4      .1       0
  4987.7     .05       0  5008.2      .1       0
#XS Ineff= 2 , 0
       0  4907.6   85.17               0
Permanent Ineff=
       F       F
Bank Sta=4987.7,5008.2
XS Rating Curve= 0 ,0
Exp/Cntr=0.5,0.3

Type RM Length L Ch R = 1 ,15630.7 ,64.6,64.6,64.6
BEGIN DESCRIPTION:
Upstream Section of Bridge/Culvert/Weir
END DESCRIPTION:
XS GIS Cut Line= 5
      3117449.16      13920186.7      3117514.17     13916676.16
      3117524.22     13916469.45      3117545.33     13916376.22
      3117561.23     13916305.99
#Sta/Elev= 30
  1298.2   87.69  1530.2   86.92  1802.2   87.52  1866.2   86.77  2058.2   88.09
  2106.2   86.85  2170.2   87.49  2314.2   85.94  2560.5   85.95  2946.2    86.4
  3065.4   85.37  3362.2   85.26  3450.2   85.96  4133.9   84.36  4205.9   84.55
  4237.9   85.51  4365.9   83.88  4405.9   84.46  4669.9    83.8  4833.5   82.54
  4972.6   83.35  4987.7   81.99  4995.9   76.34  5002.4   75.98  5006.2   77.25
  5008.2   80.14  5026.2    82.1  5112.9   82.15  5166.5   84.26  5183.9   84.51
#Mann= 6 , 1 , 0
  1298.2      .2       0  2560.5     .14       0  3065.4      .1       0
  4987.7     .04       0  5008.2      .1       0  5166.5      .2       0
#XS Ineff= 2 , 0
       0    4983    82.6    5016       0    81.4
Permanent Ineff=
       F       F
Bank Sta=4987.7,5008.2
XS Rating Curve= 0 ,0
Exp/Cntr=0.5,0.3

Type RM Length L Ch R = 2 ,15598.4 ,,,
BEGIN DESCRIPTION:
Access Road 2
Structure ID: P40-6A,,,,
END DESCRIPTION:
Bridge Culvert--1,0,-1,-1, 0
Deck Dist Width WeirC Skew NumUp NumDn MinLoCord MaxHiCord MaxSubmerge Is_Ogee
10,44.6,3,0, 53, 53, , , 0.95, 0, 1,1,,
  1298.2  1530.2  1610.2  1626.2  1642.2  1714.2  1802.2  1834.2  1866.2  1986.2
  2058.2  2106.2  2138.2  2170.2  2186.2  2314.2  2882.2  2946.2  3002.2  3066.2
  3114.2  3250.2  3362.2  3450.2  3466.2  4133.9  4173.9  4205.9  4237.9  4365.9
  4405.9  4461.9  4493.9  4669.9  4833.2  4833.5  4887.8  4950.2  4966.6  4972.6
  4987.7  4993.8  4995.9  4999.4  5002.4  5006.2  5008.2  5019.8  5026.2  5112.9
  5127.1  5157.4  5183.9
   87.75   86.98   87.25   86.98   87.41   87.05   87.58   87.06   86.83    87.5
   88.15   86.91   86.95   87.55   87.01      86   86.03   86.46   86.38   85.42
   85.58   85.57   85.32   86.02   85.57   84.42   84.61   84.61   85.57   83.94
   84.52   84.38   83.78   83.86    82.8    82.6   82.89   82.92   82.86   83.42
   82.28   82.26   82.26   82.25   82.22   82.18   82.15   82.03   82.17   82.21
   82.95   84.19   84.57
   87.75   86.98   87.25   86.98   87.41   87.05   87.58   87.06   86.83    87.5
   88.15   86.91   86.95   87.55   87.01      86   86.03   86.46   86.38   85.42
   85.58   85.57   85.32   86.02   85.57   84.42   84.61   84.61   85.57   83.94
   84.52   84.38   83.78   83.86   82.79    82.6   82.88   82.91   82.85   83.41
   82.05   78.21    76.4   76.15   76.04   77.31    80.2   81.91   82.16   82.21
   82.95   84.19   84.57
  1298.2  1530.2  1610.2  1626.2  1642.2  1714.2  1802.2  1834.2  1866.2  1986.2
  2058.2  2106.2  2138.2  2170.2  2186.2  2314.2  2882.2  2946.2  3002.2  3066.2
  3114.2  3250.2  3362.2  3450.2  3466.2  4133.9  4173.9  4205.9  4237.9  4365.9
  4405.9  4461.9  4493.9  4669.9  4833.2  4833.5  4887.8  4950.2  4966.6  4972.6
  4987.7  4993.8  4995.9  4999.4  5002.4  5006.2  5008.2  5019.8  5026.2  5112.9
  5127.1  5157.4  5183.9
   87.75   86.98   87.25   86.98   87.41   87.05   87.58   87.06   86.83    87.5
   88.15   86.91   86.95   87.55   87.01      86   86.03   86.46   86.38   85.42
   85.58   85.57   85.32   86.02   85.57   84.42   84.61   84.61   85.57   83.94
   84.52   84.38   83.78   83.86    82.8    82.6   82.89   82.92   82.86   83.42
   82.28   82.26   82.26   82.25   82.22   82.18   82.15   82.03   82.17   82.21
   82.95   84.19   84.57
   87.71   86.94   87.21   86.94   87.37   87.01   87.54   87.02   86.79   87.46
   88.11   86.87   86.91   87.51   86.97   85.96   85.99   86.42   86.34   85.38
   85.54   85.53   85.28   85.98   85.53   84.38   84.57   84.57   85.53    83.9
   84.48   84.34   83.74   83.82   82.75   82.56   82.84   82.87   82.81   83.37
   82.01   78.17   76.36   76.11      76   77.27   80.16   81.87   82.12   82.17
   82.91   84.15   84.53
BR Coef= 1 , 0 , 0 ,1.25, 0 ,,,0.8,-1,2,0,
WSPro=,,,, 1 ,,,, 0 ,,,, 0 ,,,,-1 ,-1 ,-1 , 0 , 0 , 0 , 0 , 0
Culvert=1,5.5,,44.6,0.015,0.5,1,1,3,75.48,4996.2,75.38,4996.2,Culvert #1  , 0 ,10
Culvert Bottom n=0.015
Culvert=1,5.5,,44.6,0.015,0.5,1,1,3,75.48,5002.8,75.34,5002.8,Culvert #2  , 0 ,10
Culvert Bottom n=0.015
BR U #Sta/Elev= 65
  1298.2   87.75  1418.2    87.4  1530.2   86.98  1610.2   87.25  1626.2   86.98
  1642.2   87.41  1714.2   87.05  1802.2   87.58  1834.2   87.06  1866.2   86.83
  1986.2    87.5  2058.2   88.15  2106.2   86.91  2138.2   86.95  2170.2   87.55
  2186.2   87.01  2314.2      86  2560.5   86.01  2690.2   86.01  2882.2   86.03
  2946.2   86.46  3002.2   86.38  3065.4   85.43  3066.2   85.42  3114.2   85.58
  3250.2   85.57  3362.2   85.32  3450.2   86.02  3466.2   85.57  4133.9   84.42
  4173.9   84.61  4205.9   84.61  4237.9   85.57  4365.9   83.94  4381.9   84.13
  4405.9   84.52  4461.9   84.38  4493.9   83.78  4669.9   83.86  4750.7   83.33
  4833.2   82.79  4833.3   82.73  4833.5    82.6  4887.8   82.88  4899.1   82.89
  4946.4   82.91  4950.2   82.91  4966.6   82.85  4972.6   83.41  4987.7   82.05
  4993.8   78.21  4995.9    76.4  4999.1   76.17  4999.4   76.15  5002.4   76.04
  5006.2   77.31  5008.2    80.2  5019.8   81.91  5026.2   82.16  5044.8   82.17
  5112.9   82.21  5127.1   82.95  5157.4   84.19  5166.5   84.32  5183.9   84.57
BR U #Mann= 6
  1298.2      .2  2560.5     .14  3065.4      .1  4987.7     .04  5008.2      .1
  5166.5      .2
BR U Banks=4987.7,5008.2
BR D #Sta/Elev= 65
  1298.2   87.71  1418.2   87.36  1530.2   86.94  1610.2   87.21  1626.2   86.94
  1642.2   87.37  1714.2   87.01  1802.2   87.54  1834.2   87.02  1866.2   86.79
  1986.2   87.46  2058.2   88.11  2106.2   86.87  2138.2   86.91  2170.2   87.51
  2186.2   86.97  2314.2   85.96  2560.5   85.97  2690.2   85.97  2882.2   85.99
  2946.2   86.42  3002.2   86.34  3065.4   85.39  3066.2   85.38  3114.2   85.54
  3250.2   85.53  3362.2   85.28  3450.2   85.98  3466.2   85.53  4133.9   84.38
  4173.9   84.57  4205.9   84.57  4237.9   85.53  4365.9    83.9  4381.9   84.09
  4405.9   84.48  4461.9   84.34  4493.9   83.74  4669.9   83.82  4750.7   83.29
  4833.2   82.75  4833.3   82.69  4833.5   82.56  4887.8   82.84  4899.1   82.85
  4946.4   82.87  4950.2   82.87  4966.6   82.81  4972.6   83.37  4987.7   82.01
  4993.8   78.17  4995.9   76.36  4999.1   76.13  4999.4   76.11  5002.4      76
  5006.2   77.27  5008.2   80.16  5019.8   81.87  5026.2   82.12  5044.8   82.13
  5112.9   82.17  5127.1   82.91  5157.4   84.15  5166.5   84.28  5183.9   84.53
BR D #Mann= 6
  1298.2      .2  2560.5     .14  3065.4      .1  4987.7     .04  5008.2      .1
  5166.5      .2
BR D Banks=4987.7,5008.2
BC Design=,, 0 ,, 0 ,,,,,,
BC HTab HWMax=88.09
BC Use User HTab Curves=0
BC User HTab FreeFlow(D)= 0

Type RM Length L Ch R = 1 ,15566.1 ,526.6,526.6,526.6
BEGIN DESCRIPTION:
Downstream Section of Bridge/Culvert/Weir
END DESCRIPTION:
XS GIS Cut Line= 5
       3117513.7     13920189.48      3117578.71     13916678.94
      3117588.76     13916472.23      3117609.87       13916379.
      3117625.77     13916308.76
#Sta/Elev= 30
  1298.2   87.71  1530.2   86.94  1802.2   87.54  1866.2   86.79  2058.2   88.11
  2106.2   86.87  2170.2   87.51  2314.2   85.96  2560.5   85.97  2946.2   86.42
  3065.4   85.39  3362.2   85.28  3450.2   85.98  4133.9   84.38  4205.9   84.57
  4237.9   85.53  4365.9    83.9  4405.9   84.48  4669.9   83.82  4833.5   82.56
  4972.6   83.37  4987.7   82.01  4995.9   76.36  5002.4      76  5006.2   77.27
  5008.2   80.16  5026.2   82.12  5112.9   82.17  5166.5   84.28  5183.9   84.53
#Mann= 6 , 1 , 0
  1298.2      .2       0  2560.5     .14       0  3065.4      .1       0
  4987.7     .04       0  5008.2      .1       0  5166.5      .2       0
#XS Ineff= 2 , 0
       0    4983    82.4    5016       0    81.2
Permanent Ineff=
       F       F
Bank Sta=4987.7,5008.2
XS Rating Curve= 0 ,0
Exp/Cntr=0.5,0.3

Type RM Length L Ch R = 1 ,15039.5 ,613.5,614.6,615.9
BEGIN DESCRIPTION:
Cross Section 15039.5-Interpolated
END DESCRIPTION:
XS GIS Cut Line= 5
      3117951.45     13919527.76      3118052.78     13917588.21
      3118109.48      13916666.9      3118109.48     13916502.87
      3118110.53     13916436.16
#Sta/Elev= 30
  1979.5   88.68  2043.5   86.56  2195.5   85.94  2565.2   86.47  2811.5   85.31
  2867.5   86.01  3299.5   84.35  3371.5   85.05  3539.5   84.04  3815.5   83.93
  3843.5   83.24  4033.7   84.29  4057.7   85.14  4353.7   84.05  4377.7   83.26
  4617.7   83.25  4649.7   84.68  4761.7    82.3  4801.7   84.78  4908.8   84.31
  4940.8   85.54  4976.8   82.85    4991   77.32  4998.9   76.13    5009   77.12
  5023.4   81.68  5040.8   81.63  5064.8   82.94  5066.5    84.2  5075.5      85
#Mann= 5 , 1 , 0
  1979.5      .2       0  2565.2     .14       0  3815.5      .1       0
  4976.8     .04       0  5023.4      .1       0
#XS Ineff= 2 , 0
       0  4801.7   84.78               0
Permanent Ineff=
       F       F
Bank Sta=4976.8,5023.4
XS Rating Curve= 0 ,0
Exp/Cntr=0.3,0.1

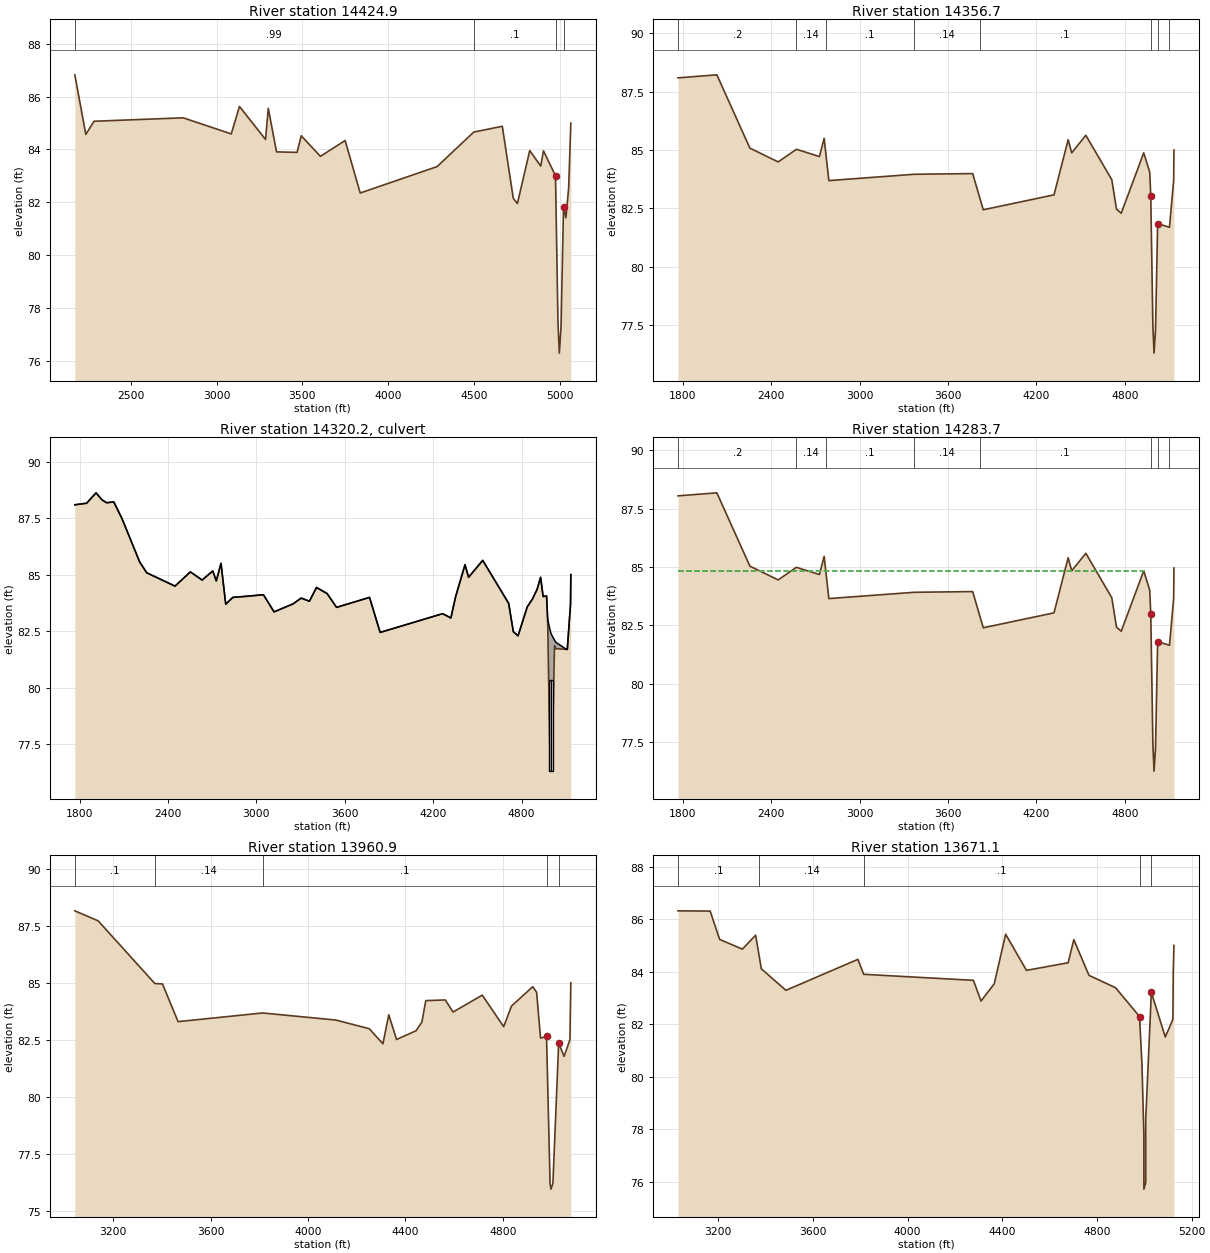
Type RM Length L Ch R = 1 ,14424.9 ,63,68.2,64.5
BEGIN DESCRIPTION:
Cross Section 14424.9-Interpolated
END DESCRIPTION:
XS GIS Cut Line= 5
      3118669.36     13919364.29       3118716.4      13917016.2
      3118720.56     13916609.16      3118724.71     13916509.47
      3118726.86     13916472.94
#Sta/Elev= 30
    2174   86.83    2238   84.57    2286   85.07    2806    85.2    3086   84.59
    3134   85.63    3286   84.38    3302   85.56    3350   83.91    3470   83.89
    3494   84.52    3606   83.74    3750   84.34    3838   82.35    4286   83.35
    4500   84.66  4666.5   84.88  4730.5   82.15  4754.5   81.95  4826.5   83.96
  4890.5   83.37  4906.5   83.95  4976.8      83    4991   77.47  4998.9   76.28
    5009   77.27  5023.4   81.83  5037.4   81.41  5053.4   82.55    5066      85
#Mann= 4 , 1 , 0
    2174     .99       0    4500      .1       0  4976.8     .04       0
  5023.4      .1       0
#XS Ineff= 2 , 0
       0  4906.5   83.95               0
Permanent Ineff=
       F       F
Bank Sta=4976.8,5023.4
XS Rating Curve= 0 ,0
Exp/Cntr=0.5,0.3

Type RM Length L Ch R = 1 ,14356.7 ,73,73,73
BEGIN DESCRIPTION:
Upstream Section of Bridge/Culvert/Weir
END DESCRIPTION:
XS GIS Cut Line= 5
      3118690.09     13919772.14      3118775.18     13916916.18
      3118790.52     13916580.89      3118792.49     13916536.31
      3118798.04     13916407.92
#Sta/Elev= 30
  1768.1   88.09  2032.1   88.22  2256.1   85.08  2448.1   84.49    2572   85.03
  2728.1   84.72  2760.1    85.5  2773.2   84.76  2792.1   83.69    3371   83.96
  3768.1   83.99  3815.8   82.96  3840.1   82.44  4320.1   83.08  4416.1   85.44
  4440.1   84.88  4536.1   85.63  4712.1   83.73  4744.1   82.47  4776.1   82.29
  4929.1   84.88  4969.6   84.05  4976.8   83.02    4991   77.49  4998.9    76.3
    5009   77.29  5023.4   81.85  5103.7   81.69  5132.1    83.7  5134.1      85
#Mann= 8 , 1 , 0
  1768.1      .2       0    2572     .14       0  2773.2      .1       0
    3371     .14       0  3815.8      .1       0  4976.8     .04       0
  5023.4      .1       0  5103.7      .2       0
#XS Ineff= 2 , 0
       0  4929.1   84.85    5021       0    80.8
Permanent Ineff=
       F       F
Bank Sta=4976.8,5023.4
XS Rating Curve= 0 ,0
Exp/Cntr=0.5,0.3

Type RM Length L Ch R = 2 ,14320.2 ,,,
BEGIN DESCRIPTION:
Access Road 1
Structure ID: P40-6,,,,
END DESCRIPTION:
Bridge Culvert--1,0,-1,-1, 0
Deck Dist Width WeirC Skew NumUp NumDn MinLoCord MaxHiCord MaxSubmerge Is_Ogee
10,53,3,0, 53, 53, , , 0.95, 0, 1,1,,
  1768.1  1848.1  1912.1  1952.1  1984.1  2032.1  2088.1  2208.1  2256.1  2448.1
  2552.1  2632.1  2704.1  2728.1  2760.1  2792.1  2840.1  3048.1  3120.1  3248.1
  3304.1  3360.1  3408.1  3480.1  3544.1  3768.1  3840.1  4264.1  4320.1  4352.1
  4416.1  4440.1  4536.1  4712.1  4744.1  4776.1  4838.2  4873.9  4905.4  4929.1
  4946.1  4969.6  4976.8    4991  4995.4  4998.9    5009  5023.4  5031.2  5103.7
  5110.3  5132.1  5134.1
   88.09   88.16   88.62   88.31   88.18   88.22   87.48   85.56   85.08   84.49
   85.12   84.76   85.16   84.72    85.5   83.69   83.99   84.11   83.35    83.7
   83.96   83.82   84.43   84.16   83.55   83.99   82.44   83.27   83.08   84.02
   85.44   84.88   85.63   83.73   82.47   82.29   83.57   83.92   84.35   84.88
   84.03   84.06   83.03   82.61    82.5   82.41   82.27    82.1   82.01   81.69
   81.69    83.7      85
   88.09   88.16   88.62   88.31   88.18   88.22   87.48   85.56   85.08   84.49
   85.12   84.76   85.16   84.72    85.5   83.69   83.99   84.11   83.35    83.7
   83.96   83.82   84.43   84.16   83.55   83.99   82.44   83.27   83.08   84.02
   85.44   84.88   85.63   83.73   82.47   82.29   83.57   83.92   84.35   84.88
   84.03   84.05   83.02   77.49   76.99    76.3   77.29   81.85   81.72   81.69
   81.69    83.7      85
  1768.1  1848.1  1912.1  1952.1  1984.1  2032.1  2088.1  2208.1  2256.1  2448.1
  2552.1  2632.1  2704.1  2728.1  2760.1  2792.1  2840.1  3048.1  3120.1  3248.1
  3304.1  3360.1  3408.1  3480.1  3544.1  3768.1  3840.1  4264.1  4320.1  4352.1
  4416.1  4440.1  4536.1  4712.1  4744.1  4776.1  4838.2  4873.9  4905.4  4929.1
  4946.1  4969.6  4976.8    4991  4995.4  4998.9    5009  5023.4  5031.2  5103.7
  5110.3  5132.1  5134.1
   88.09   88.16   88.62   88.31   88.18   88.22   87.48   85.56   85.08   84.49
   85.12   84.76   85.16   84.72    85.5   83.69   83.99   84.11   83.35    83.7
   83.96   83.82   84.43   84.16   83.55   83.99   82.44   83.27   83.08   84.02
   85.44   84.88   85.63   83.73   82.47   82.29   83.57   83.92   84.35   84.88
   84.03   84.06   83.03   82.61    82.5   82.41   82.27    82.1   82.01   81.69
   81.69    83.7      85
   88.06   88.13   88.59   88.28   88.15   88.19   87.45   85.53   85.05   84.46
   85.09   84.73   85.13   84.69   85.47   83.66   83.96   84.08   83.32   83.67
   83.93   83.79    84.4   84.13   83.52   83.96   82.41   83.24   83.05   83.99
   85.41   84.85    85.6    83.7   82.44   82.26   83.54   83.89   84.32   84.85
      84   84.02   82.99   77.46   76.96   76.27   77.26   81.82   81.69   81.66
   81.66   83.67   84.97
BR Coef= 1 , 0 , 0 ,1.25, 0 ,,,0.8,-1,2,0,
WSPro=,,,, 1 ,,,, 0 ,,,, 0 ,,,,-1 ,-1 ,-1 , 0 , 0 , 0 , 0 , 0
Culvert=2,4,11,53,0.015,0.4,1,8,1,76.32,4992,76.2,4992,Culvert #1  , 0 ,10
Culvert Bottom n=0.015
Culvert=2,4,11,53,0.015,0.4,1,8,1,76.32,5005.6,76.2,5005.6,Culvert #2  , 0 ,10
Culvert Bottom n=0.015
BR U #Sta/Elev= 62
  1768.1   88.09  1848.1   88.16  1912.1   88.62  1952.1   88.31  1984.1   88.18
  2032.1   88.22  2088.1   87.48  2208.1   85.56  2256.1   85.08  2448.1   84.49
  2552.1   85.12    2572   85.03  2632.1   84.76  2704.1   85.16  2728.1   84.72
  2760.1    85.5  2773.2   84.76  2792.1   83.69  2840.1   83.99  2944.1   84.04
  3048.1   84.11  3120.1   83.35  3248.1    83.7  3304.1   83.96  3360.1   83.82
    3371   83.96  3408.1   84.43  3480.1   84.16  3544.1   83.55  3768.1   83.99
  3815.8   82.96  3840.1   82.44  4264.1   83.27  4320.1   83.08  4352.1   84.02
  4416.1   85.44  4440.1   84.88  4536.1   85.63  4712.1   83.73  4744.1   82.47
  4776.1   82.29  4838.2   83.57  4873.9   83.92  4905.4   84.35  4929.1   84.88
  4946.1   84.03  4957.8   84.04  4969.6   84.05  4976.1   83.12  4976.8   83.02
    4991   77.49  4995.4   76.99  4998.9    76.3  5000.7   76.48    5009   77.29
  5023.4   81.85  5031.2   81.72  5032.1   81.72  5103.7   81.69  5110.3   81.69
  5132.1    83.7  5134.1      85
BR U #Mann= 8
  1768.1      .2    2572     .14  2773.2      .1    3371     .14  3815.8      .1
  4976.8     .04  5023.4      .1  5103.7      .2
BR U Banks=4976.8,5023.4
BR D #Sta/Elev= 62
  1768.1   88.06  1848.1   88.13  1912.1   88.59  1952.1   88.28  1984.1   88.15
  2032.1   88.19  2088.1   87.45  2208.1   85.53  2256.1   85.05  2448.1   84.46
  2552.1   85.09    2572      85  2632.1   84.73  2704.1   85.13  2728.1   84.69
  2760.1   85.47  2773.2   84.73  2792.1   83.66  2840.1   83.96  2944.1   84.01
  3048.1   84.08  3120.1   83.32  3248.1   83.67  3304.1   83.93  3360.1   83.79
    3371   83.93  3408.1    84.4  3480.1   84.13  3544.1   83.52  3768.1   83.96
  3815.8   82.93  3840.1   82.41  4264.1   83.24  4320.1   83.05  4352.1   83.99
  4416.1   85.41  4440.1   84.85  4536.1    85.6  4712.1    83.7  4744.1   82.44
  4776.1   82.26  4838.2   83.54  4873.9   83.89  4905.4   84.32  4929.1   84.85
  4946.1      84  4957.8   84.01  4969.6   84.02  4976.1   83.09  4976.8   82.99
    4991   77.46  4995.4   76.96  4998.9   76.27  5000.7   76.45    5009   77.26
  5023.4   81.82  5031.2   81.69  5032.1   81.69  5103.7   81.66  5110.3   81.66
  5132.1   83.67  5134.1   84.97
BR D #Mann= 8
  1768.1      .2    2572     .14  2773.2      .1    3371     .14  3815.8      .1
  4976.8     .04  5023.4      .1  5103.7      .2
BR D Banks=4976.8,5023.4
BC Design=,, 0 ,, 0 ,,,,,,
BC HTab HWMax=88.62
BC Use User HTab Curves=0
BC User HTab FreeFlow(D)= 0

Type RM Length L Ch R = 1 ,14283.7 ,322.8,322.8,322.8
BEGIN DESCRIPTION:
Downstream Section of Bridge/Culvert/Weir
END DESCRIPTION:
XS GIS Cut Line= 5
      3118763.01     13919775.37       3118848.1     13916919.42
      3118863.44     13916584.13      3118865.41     13916539.55
      3118870.97     13916411.15
#Sta/Elev= 30
  1768.1   88.05  2032.1   88.18  2256.1   85.04  2448.1   84.45    2572   84.99
  2728.1   84.68  2760.1   85.46  2773.2   84.72  2792.1   83.65    3371   83.92
  3768.1   83.95  3815.8   82.92  3840.1    82.4  4320.1   83.04  4416.1    85.4
  4440.1   84.84  4536.1   85.59  4712.1   83.69  4744.1   82.43  4776.1   82.25
  4929.1   84.84  4969.6   84.01  4976.8   82.98    4991   77.45  4998.9   76.26
    5009   77.25  5023.4   81.81  5103.7   81.65  5132.1   83.66  5134.1   84.96
#Mann= 8 , 1 , 0
  1768.1      .2       0    2572     .14       0  2773.2      .1       0
    3371     .14       0  3815.8      .1       0  4976.8     .04       0
  5023.4      .1       0  5103.7      .2       0
#XS Ineff= 2 , 0
       0  4929.1   84.85    5021       0    80.6
Permanent Ineff=
       F       F
Bank Sta=4976.8,5023.4
XS Rating Curve= 0 ,0
Exp/Cntr=0.5,0.3

Type RM Length L Ch R = 1 ,13960.9 ,302.7,289.8,288.4
BEGIN DESCRIPTION:
Cross Section 13960.9-Interpolated
END DESCRIPTION:
XS GIS Cut Line= 5
      3119070.17     13918511.37      3119115.82      13917318.9
      3119158.35     13916681.07      3119187.83     13916555.77
      3119192.85     13916480.24
#Sta/Elev= 30
  3042.4   88.15  3138.4   87.71  3370.8   84.97  3402.4   84.95  3466.4    83.3
  3813.4   83.68  4114.4   83.37  4251.7   82.99  4307.7   82.33  4331.7    83.6
  4363.7   82.52  4443.7    82.9  4467.7   83.28  4483.7   84.22  4563.7   84.25
  4595.7   83.72  4715.7   84.46  4803.7   83.08  4835.7   83.98    4923   84.83
    4939   84.58    4955   82.58  4979.7   82.65  4994.2   76.21    4998   75.97
  5005.8   76.22  5029.5   82.36  5051.7   81.78  5075.7   82.51  5079.4      85
#Mann= 5 , 1 , 0
  3042.4      .1       0  3370.8     .14       0  3813.4      .1       0
  4979.7     .04       0  5029.5      .1       0
#XS Ineff= 2 , 0
       0    4923   84.83               0
Permanent Ineff=
       F       F
Bank Sta=4979.7,5029.5
XS Rating Curve= 0 ,0
Exp/Cntr=0.3,0.1

Type RM Length L Ch R = 1 ,13671.1 ,102.1,121.8,130.2
BEGIN DESCRIPTION:
Cross Section 13671.1-Interpolated
END DESCRIPTION:
XS GIS Cut Line= 4
       3119297.5     13918533.84       3119476.5     13916621.62
       3119476.5     13916555.16      3119484.19     13916447.48
#Sta/Elev= 30
    3030   86.32    3166   86.31    3206   85.23    3302   84.86    3358   85.39
  3372.9    84.6    3382   84.11    3486   83.29    3790   84.47  3814.4    83.9
    4278   83.67    4310   82.88    4366   83.54    4414   85.43    4502   84.05
    4678   84.34    4702   85.22    4766   83.86    4878   83.39  4979.7   82.29
  4989.9   80.45  4997.9   77.79    4998   75.71  5005.8   75.96  5005.9    78.4
  5029.5   83.21  5088.4   81.51  5120.4   82.18    5122      84    5125      85
#Mann= 5 , 1 , 0
    3030      .1       0  3372.9     .14       0  3814.4      .1       0
  4979.7     .04       0  5029.5      .2       0
#XS Ineff= 2 , 0
       0    4702   85.22               0
Permanent Ineff=
       F       F
Bank Sta=4979.7,5029.5
XS Rating Curve= 0 ,0
Exp/Cntr=0.5,0.3