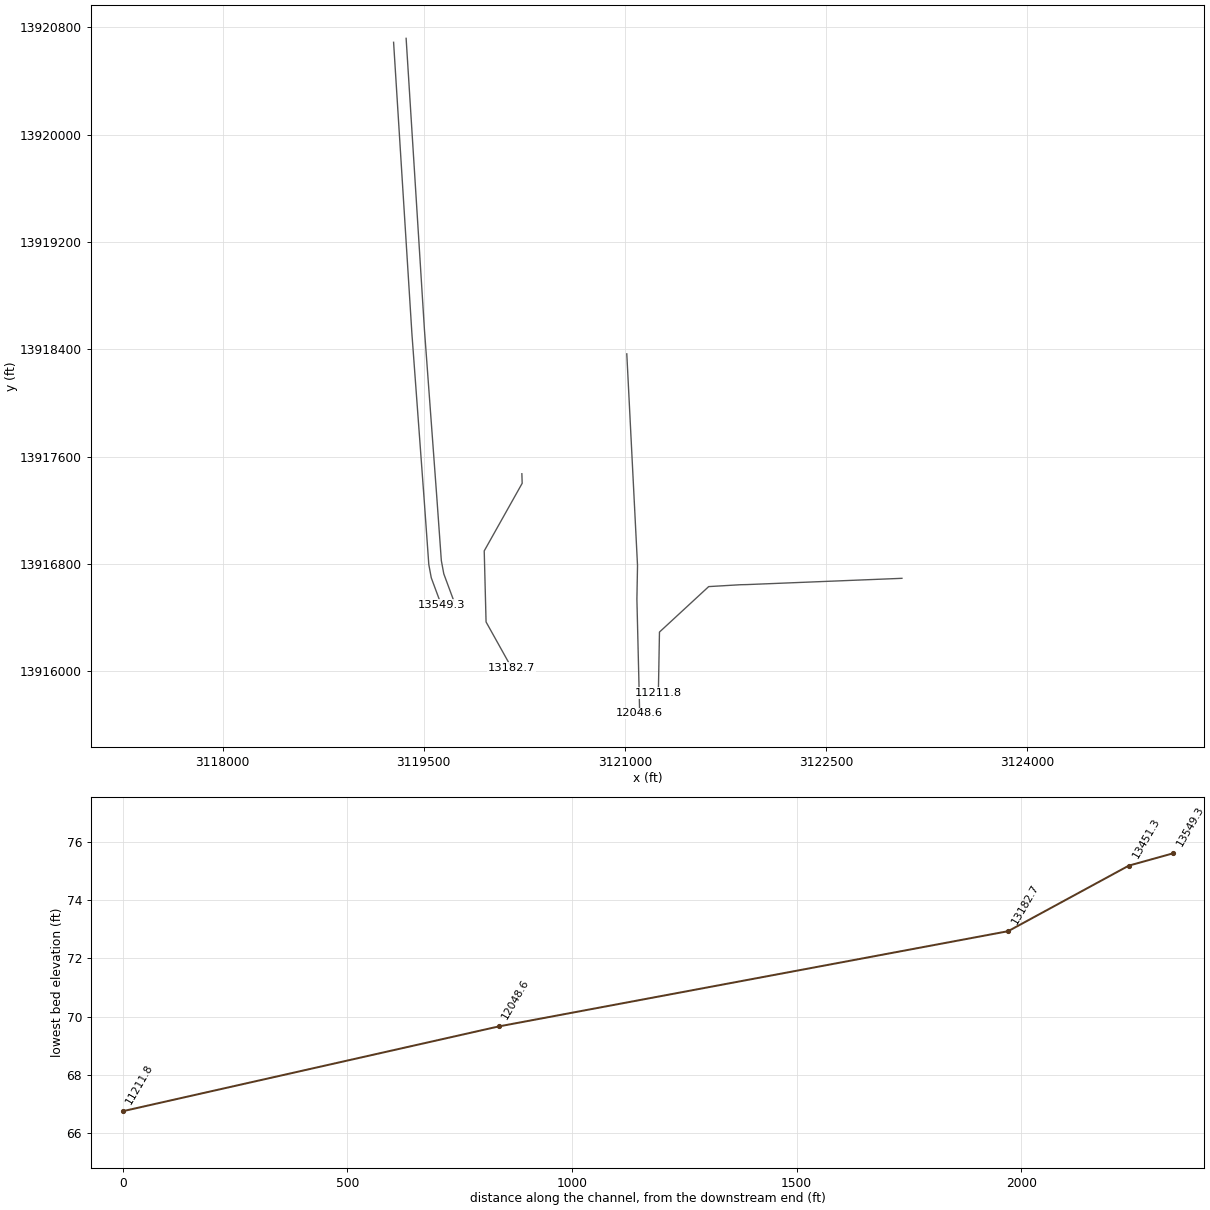
HEC-RAS study P140-00-00.prj: P140-00-00 (Hoods Bayou)

--- P140-00-00.g01 (geometry) --- (continued)

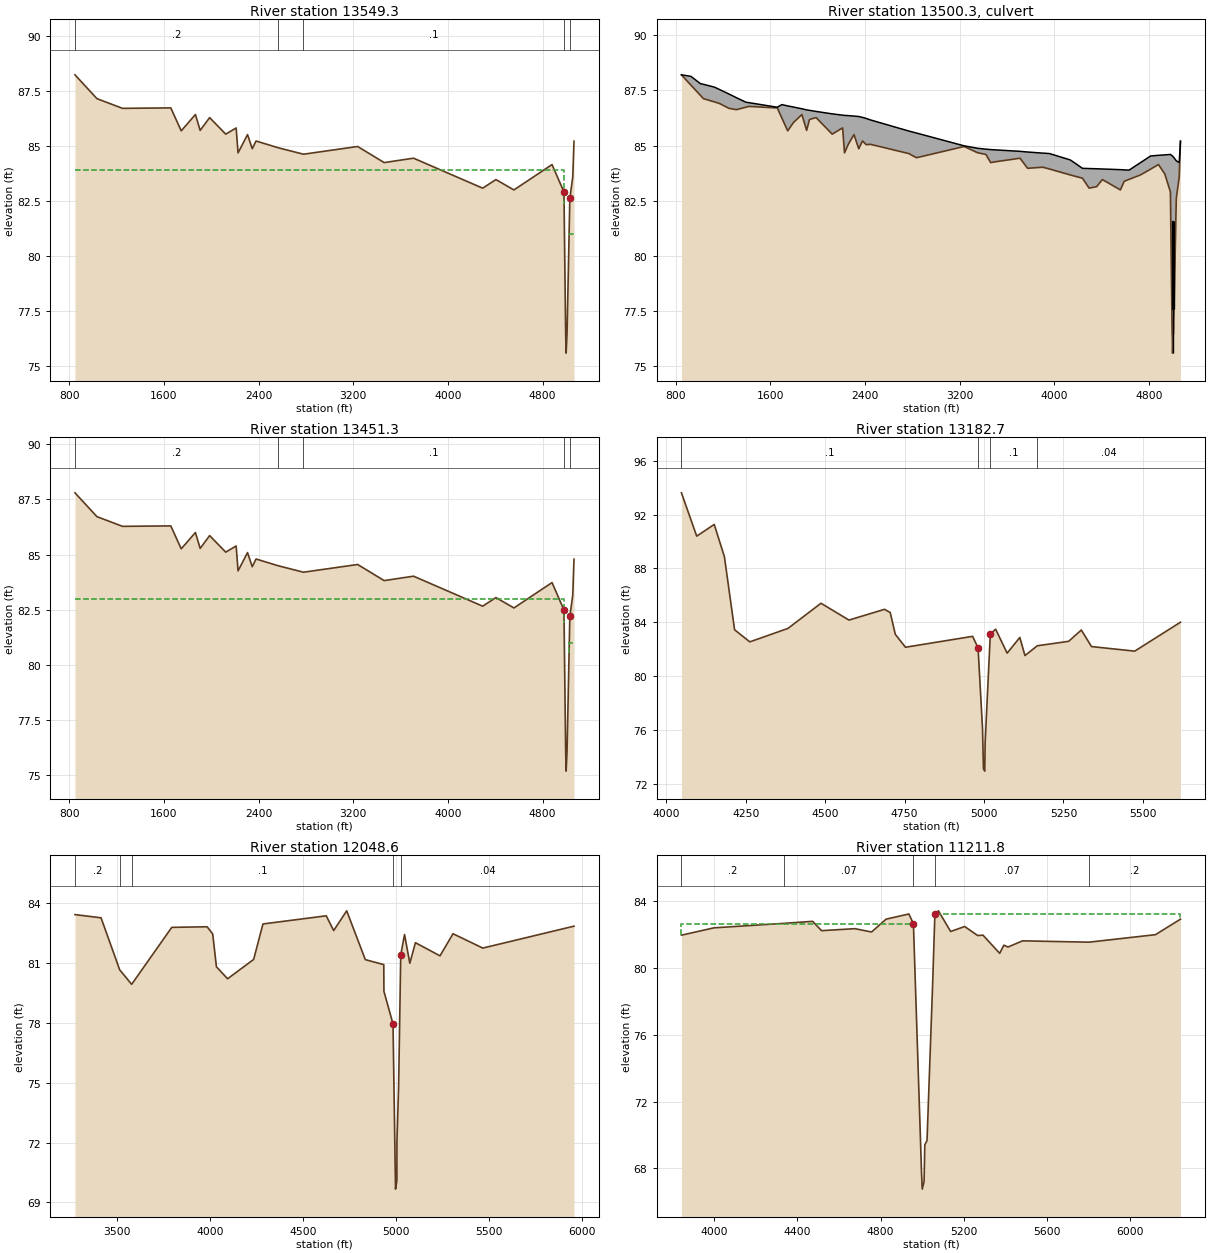
Type RM Length L Ch R = 1 ,13549.3 ,98,98,98
BEGIN DESCRIPTION:
Upstream Section of Bridge/Culvert/Weir
END DESCRIPTION:
XS GIS Cut Line= 6
      3119275.09     13920687.96      3119411.54     13918519.71
      3119504.08     13917266.91       3119537.8     13916796.08
      3119556.14     13916697.54       3119630.5     13916496.96
#Sta/Elev= 30
   849.7   88.22    1035   87.14    1251    86.7    1659   86.72    1747   85.68
    1867   86.42    1907    85.7    1987   86.28    2123   85.53    2211   85.81
    2227   84.68    2307   85.51    2347   84.87    2379   85.22  2561.4   84.92
  2779.5   84.62  3237.2   84.97  3461.2   84.24  3709.2   84.44  4293.2   83.08
  4405.2   83.47  4557.2      83  4879.1   84.15  4979.7   82.91  4994.2   76.47
    4998    75.6  5005.8   76.48  5029.5   82.62  5054.1   83.58  5064.6   85.21
#Mann= 5 , 1 , 0
   849.7      .2       0  2561.4     .14       0  2779.5      .1       0
  4979.7     .04       0  5029.5      .1       0
#XS Ineff= 2 , 0
       0    4981    83.9    5023       0      81
Permanent Ineff=
       F       F
Bank Sta=4979.7,5029.5
XS Rating Curve= 0 ,0
Exp/Cntr=0.5,0.3

Type RM Length L Ch R = 2 ,13500.3 ,,,
BEGIN DESCRIPTION:
Aldine Westfield Road
Structure ID: P40-05
END DESCRIPTION:
Bridge Culvert--1,0,-1,-1, 0
Deck Dist Width WeirC Skew NumUp NumDn MinLoCord MaxHiCord MaxSubmerge Is_Ogee
10,78,3,0, 55, 55, , , 0.95, 0, 1,1,,
   849.7   929.7  1009.7    1035  1129.7    1251    1315  1393.7    1659  1697.7
    1747    1795    1867    1907    1931    1987    2123    2211    2227    2259
    2307    2347    2379    2411    2443    2771    2835  3237.2  3349.2  3421.2
  3461.2  3709.2  3773.2  3901.2  3958.2  4134.2  4237.2  4293.2  4357.2  4405.2
  4557.2  4589.2    4631  4812.4  4879.1  4932.7  4979.7  4994.2  4995.7    4998
  5002.1  5005.8  5029.5  5054.1  5064.6
   88.21   88.14   87.81   87.78   87.65   87.34   87.17   86.97   86.74   86.86
    86.8   86.75   86.67   86.62    86.6   86.55   86.44   86.38   86.37   86.36
   86.34   86.32   86.28   86.23   86.17   85.66   85.57   84.99   84.88   84.84
   84.82   84.74   84.71   84.66   84.64   84.35   83.97   83.96   83.95   83.94
   83.91    83.9   83.89   84.53   84.56   84.58    84.6   84.54   84.53   84.52
    84.5   84.48   84.31   84.23    85.2
   88.21   87.74   87.28   87.13   86.98   86.69   86.63   86.74   86.71   86.25
   85.67   86.04   86.41   85.69   86.18   86.27   85.52    85.8   84.67   85.06
    85.5   84.86   85.21   85.04   85.06   84.64   84.45   84.96   84.68    84.6
   84.23   84.43   83.97   84.02   83.94   83.67   83.52   83.07   83.14   83.46
   82.99   83.38   83.47   83.93   84.14   83.71    82.9   76.46   76.37   75.59
   76.36   76.47   82.61   83.57    85.2
   849.7   929.7  1009.7    1035  1129.7    1251    1315  1393.7    1659  1697.7
    1747    1795    1867    1907    1931    1987    2123    2211    2227    2259
    2307    2347    2379    2411    2443    2771    2835  3237.2  3349.2  3421.2
  3461.2  3709.2  3773.2  3901.2  3958.2  4134.2  4237.2  4293.2  4357.2  4405.2
  4557.2  4589.2    4631  4812.4  4879.1  4932.7  4979.7  4994.2  4995.7    4998
  5002.1  5005.8  5029.5  5054.1  5064.6
   88.21   88.14   87.81   87.78   87.65   87.34   87.17   86.97   86.74   86.86
    86.8   86.75   86.67   86.62    86.6   86.55   86.44   86.38   86.37   86.36
   86.34   86.32   86.28   86.23   86.17   85.66   85.57   84.99   84.88   84.84
   84.82   84.74   84.71   84.66   84.64   84.35   83.97   83.96   83.95   83.94
   83.91    83.9   83.89   84.53   84.56   84.58    84.6   84.54   84.53   84.52
    84.5   84.48   84.31   84.23    85.2
   87.88   87.41   86.95    86.8   86.65   86.36    86.3   86.41   86.38   85.92
   85.34   85.71   86.08   85.36   85.85   85.94   85.19   85.47   84.34   84.73
   85.17   84.53   84.88   84.71   84.73   84.31   84.12   84.63   84.35   84.27
    83.9    84.1   83.64   83.69   83.61   83.34   83.19   82.74   82.81   83.13
   82.66   83.05   83.14    83.6   83.81   83.38   82.57   76.13   76.04   75.26
   76.03   76.14   82.28   83.24   84.87
BR Coef= 1 , 0 , 0 ,1.25, 0 ,,,0.8,-1,2,0,
WSPro=,,,, 1 ,,,, 0 ,,,, 0 ,,,,-1 ,-1 ,-1 , 0 , 0 , 0 , 0 , 0
Culvert=2,4,6,78,0.015,0.4,1,8,1,77.59,4994.8,77.15,4994.8,Culvert #1  , 0 ,10
Culvert Bottom n=0.015
Culvert=2,5.8,6,78,0.015,0.4,1,8,1,75.59,5001.8,75.35,5001.8,Culvert #2  , 0 ,10
Culvert Bottom n=0.015
Culvert=2,4,6,78,0.015,0.4,1,8,1,77.59,5010,77.15,5010,Culvert #3  , 0 ,10
Culvert Bottom n=0.015
BR U #Sta/Elev= 81
   849.7   88.21   929.7   87.74  1009.7   87.28    1035   87.13  1129.7   86.98
    1171   86.91    1251   86.69    1315   86.63  1393.7   86.74    1419   86.78
  1441.7   86.77  1649.7   86.71    1659   86.71  1697.7   86.25    1747   85.67
    1795   86.04    1867   86.41    1907   85.69    1931   86.18  1953.7   86.22
    1987   86.27    2123   85.52  2209.7    85.8    2211    85.8    2227   84.67
    2259   85.06    2307    85.5    2347   84.86  2353.7   84.93    2379   85.21
    2411   85.04    2443   85.06  2561.4   84.91  2753.7   84.66    2771   84.64
  2777.7   84.62  2779.5   84.61    2835   84.45  3237.2   84.96  3294.2   84.82
  3349.2   84.68  3421.2    84.6  3461.2   84.23  3518.2   84.28  3686.2   84.41
  3709.2   84.43  3773.2   83.97  3901.2   84.02  3958.2   83.94  4134.2   83.67
  4237.2   83.52  4238.2   83.51  4293.2   83.07  4357.2   83.14  4405.2   83.46
  4557.2   82.99  4589.2   83.38    4631   83.47  4721.8   83.66    4743   83.72
  4812.4   83.93  4814.2   83.94  4879.1   84.14  4932.7   83.71  4979.7    82.9
 4982.09   81.84  4982.2   81.79 4982.31   81.74  4994.2   76.46  4995.7   76.37
    4998   75.59  5002.1   76.36  5005.8   76.47  5022.5    80.8 5027.99   82.22
  5028.1   82.25 5028.21   82.28  5029.5   82.61  5054.1   83.57  5064.5   85.18
  5064.6    85.2
BR U #Mann= 5
   849.7      .2  2561.4     .14  2779.5      .1  4979.7     .04  5029.5      .1
BR U Banks=4979.7,5029.5
BR D #Sta/Elev= 81
   849.7   87.88   929.7   87.41  1009.7   86.95    1035    86.8  1129.7   86.65
    1171   86.58    1251   86.36    1315    86.3  1393.7   86.41    1419   86.45
  1441.7   86.44  1649.7   86.38    1659   86.38  1697.7   85.92    1747   85.34
    1795   85.71    1867   86.08    1907   85.36    1931   85.85  1953.7   85.89
    1987   85.94    2123   85.19  2209.7   85.47    2211   85.47    2227   84.34
    2259   84.73    2307   85.17    2347   84.53  2353.7    84.6    2379   84.88
    2411   84.71    2443   84.73  2561.4   84.58  2753.7   84.33    2771   84.31
  2777.7   84.29  2779.5   84.28    2835   84.12  3237.2   84.63  3294.2   84.49
  3349.2   84.35  3421.2   84.27  3461.2    83.9  3518.2   83.95  3686.2   84.08
  3709.2    84.1  3773.2   83.64  3901.2   83.69  3958.2   83.61  4134.2   83.34
  4237.2   83.19  4238.2   83.18  4293.2   82.74  4357.2   82.81  4405.2   83.13
  4557.2   82.66  4589.2   83.05    4631   83.14  4721.8   83.33    4743   83.39
  4812.4    83.6  4814.2   83.61  4879.1   83.81  4932.7   83.38  4979.7   82.57
 4982.09   81.51  4982.2   81.46 4982.31   81.41  4994.2   76.13  4995.7   76.04
    4998   75.26  5002.1   76.03  5005.8   76.14  5022.5   80.47 5027.99   81.89
  5028.1   81.92 5028.21   81.95  5029.5   82.28  5054.1   83.24  5064.5   84.85
  5064.6   84.87
BR D #Mann= 5
   849.7      .2  2561.4     .14  2779.5      .1  4979.7     .04  5029.5      .1
BR D Banks=4979.7,5029.5
BC Design=,, 0 ,, 0 ,,,,,,
BC HTab HWMax=88.22
BC Use User HTab Curves=0
BC User HTab FreeFlow(D)= 0

Type RM Length L Ch R = 1 ,13451.3 ,268.6,268.6,268.6
BEGIN DESCRIPTION:
Downstream Section of Bridge/Culvert/Weir
END DESCRIPTION:
XS GIS Cut Line= 6
      3119368.57     13920717.38      3119505.02     13918549.13
      3119597.56     13917296.33      3119631.28      13916825.5
      3119649.62     13916726.96      3119723.98     13916526.37
#Sta/Elev= 30
   849.7    87.8    1035   86.72    1251   86.28    1659    86.3    1747   85.26
    1867      86    1907   85.28    1987   85.86    2123   85.11    2211   85.39
    2227   84.26    2307   85.09    2347   84.45    2379    84.8  2561.4    84.5
  2779.5    84.2  3237.2   84.55  3461.2   83.82  3709.2   84.02  4293.2   82.66
  4405.2   83.05  4557.2   82.58  4879.1   83.73  4979.7   82.49  4994.2   76.05
    4998   75.18  5005.8   76.06  5029.5    82.2  5054.1   83.16  5064.6   84.79
#Mann= 5 , 1 , 0
   849.7      .2       0  2561.4     .14       0  2779.5      .1       0
  4979.7     .04       0  5029.5      .1       0
#XS Ineff= 2 , 0
       0    4981      83    5023       0      81
Permanent Ineff=
       F       F
Bank Sta=4979.7,5029.5
XS Rating Curve= 0 ,0
Exp/Cntr=0.5,0.3

Type RM Length L Ch R = 1 ,13182.7 ,1137.6,1134.1,1129.3
BEGIN DESCRIPTION:
Cross Section  13182.7
END DESCRIPTION:
XS GIS Cut Line= 5
      3120232.05     13917472.85      3120234.33     13917401.72
       3119951.2     13916897.88      3119964.95     13916368.51
      3120155.97     13916026.26
#Sta/Elev= 30
  4047.6   93.62  4095.6    90.4  4150.8   91.27  4182.8   88.87  4214.8   83.44
  4262.8   82.54  4382.8   83.54  4486.8   85.41  4574.8   84.16  4686.8   84.96
  4704.7   84.72  4720.7    83.1  4752.7   82.14    4964   82.95  4981.2   82.09
  4995.1   76.13  4998.1   73.12  5002.2   72.93  5003.5   75.07  5019.7   83.11
  5036.5   83.48  5072.7    81.7  5112.7   82.87  5128.7   81.52  5167.7   82.25
  5266.2   82.58  5306.2   83.42  5338.2   82.19  5474.2   81.85  5618.2      84
#Mann= 4 , 1 , 0
  4047.6      .1       0  4981.2     .04       0  5019.7      .1       0
  5167.7     .04       0
#XS Ineff= 2 , 0
       0  4486.8   85.41  5036.5       0   83.48
Permanent Ineff=
       F       F
Bank Sta=4981.2,5019.7
XS Rating Curve= 0 ,0
Exp/Cntr=0.3,0.1

Type RM Length L Ch R = 1 ,12048.6 ,926.9,836.8,370.8
BEGIN DESCRIPTION:
Cross Section  12048.6
END DESCRIPTION:
XS GIS Cut Line= 4
      3121014.69      13918366.2      3121094.73     13916789.02
      3121090.14     13916536.95      3121110.85     13915687.27
#Sta/Elev= 30
  3275.7   83.44  3415.7   83.28  3515.8   80.67  3580.2   79.94  3795.7    82.8
  3985.7   82.83  4015.7   82.47  4035.7   80.82  4095.7   80.22  4235.7   81.19
  4285.7   82.97  4625.7   83.38  4665.7   82.64  4735.7   83.63  4835.7   81.18
  4934.9   80.93  4935.7   79.59  4984.6   77.95    4998   69.66  5005.5   70.08
  5005.6   72.03  5014.5   74.75  5026.1   81.42  5046.5   82.44  5074.9      81
  5104.9   82.03    5237   81.37    5307   82.48    5467   81.76    5957   82.86
#Mann= 5 , 1 , 0
  3275.7      .2       0  3515.8     .04       0  3580.2      .1       0
  4984.6     .04       0  5026.1     .04       0
#XS Ineff= 2 , 0
       0  4285.7   82.97               0
Permanent Ineff=
       F       F
Bank Sta=4984.6,5026.1
XS Rating Curve= 0 ,0
Exp/Cntr=0.5,0.3

Type RM Length L Ch R = 1 ,11211.8 ,16.2,16.2,16.2
BEGIN DESCRIPTION:
Upstream Section of Bridge/Culvert/Weir
END DESCRIPTION:
XS GIS Cut Line= 6
      3123067.12     13916693.61      3121912.06     13916646.98
      3121862.57     13916645.91      3121625.67     13916631.94
       3121258.5     13916293.21      3121250.21     13915838.95
#Sta/Elev= 30
    3844   81.98  4000.3   82.42  4338.5   82.69  4474.1   82.81    4517   82.25
    4677   82.37    4757   82.17 4826.71   82.94 4936.21   83.25 4958.11   82.67
 4995.31   68.44 4996.81   67.79 5000.51   66.75 5009.31   67.21 5012.81   69.41
 5023.41   69.66 5050.31   79.03 5061.21   83.25 5078.21   83.44 5137.01    82.2
 5204.21    82.5 5266.51   81.96  5292.4   81.98  5372.4   80.89  5392.4   81.38
  5412.4   81.27  5482.4   81.64  5801.3   81.56  6120.7   82.01  6240.7   82.94
#Mann= 5 , 1 , 0
    3844      .2       0  4338.5     .07       0 4958.11     .04       0
 5061.21     .07       0  5801.3      .2       0
#XS Ineff= 2 , 0
       0  4957.9   82.64    5062       0   83.22
Permanent Ineff=
       F       F
Bank Sta=4958.11,5061.21
XS Rating Curve= 0 ,0
Exp/Cntr=0.5,0.3