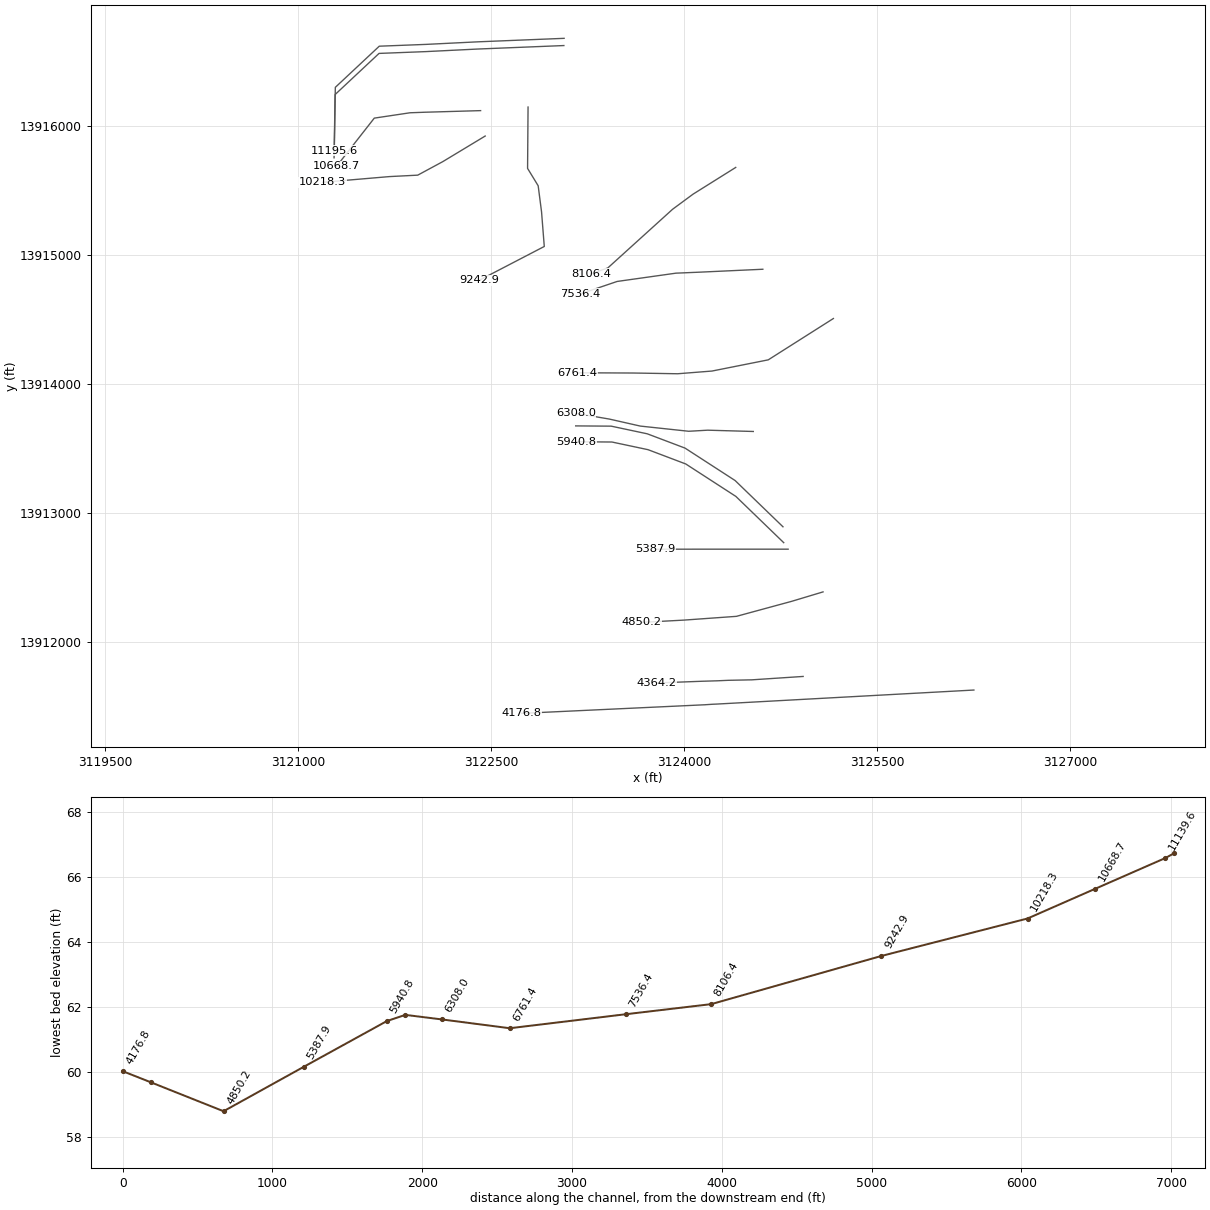
HEC-RAS study P140-00-00.prj: P140-00-00 (Hoods Bayou)

--- P140-00-00.g01 (geometry) --- (continued)

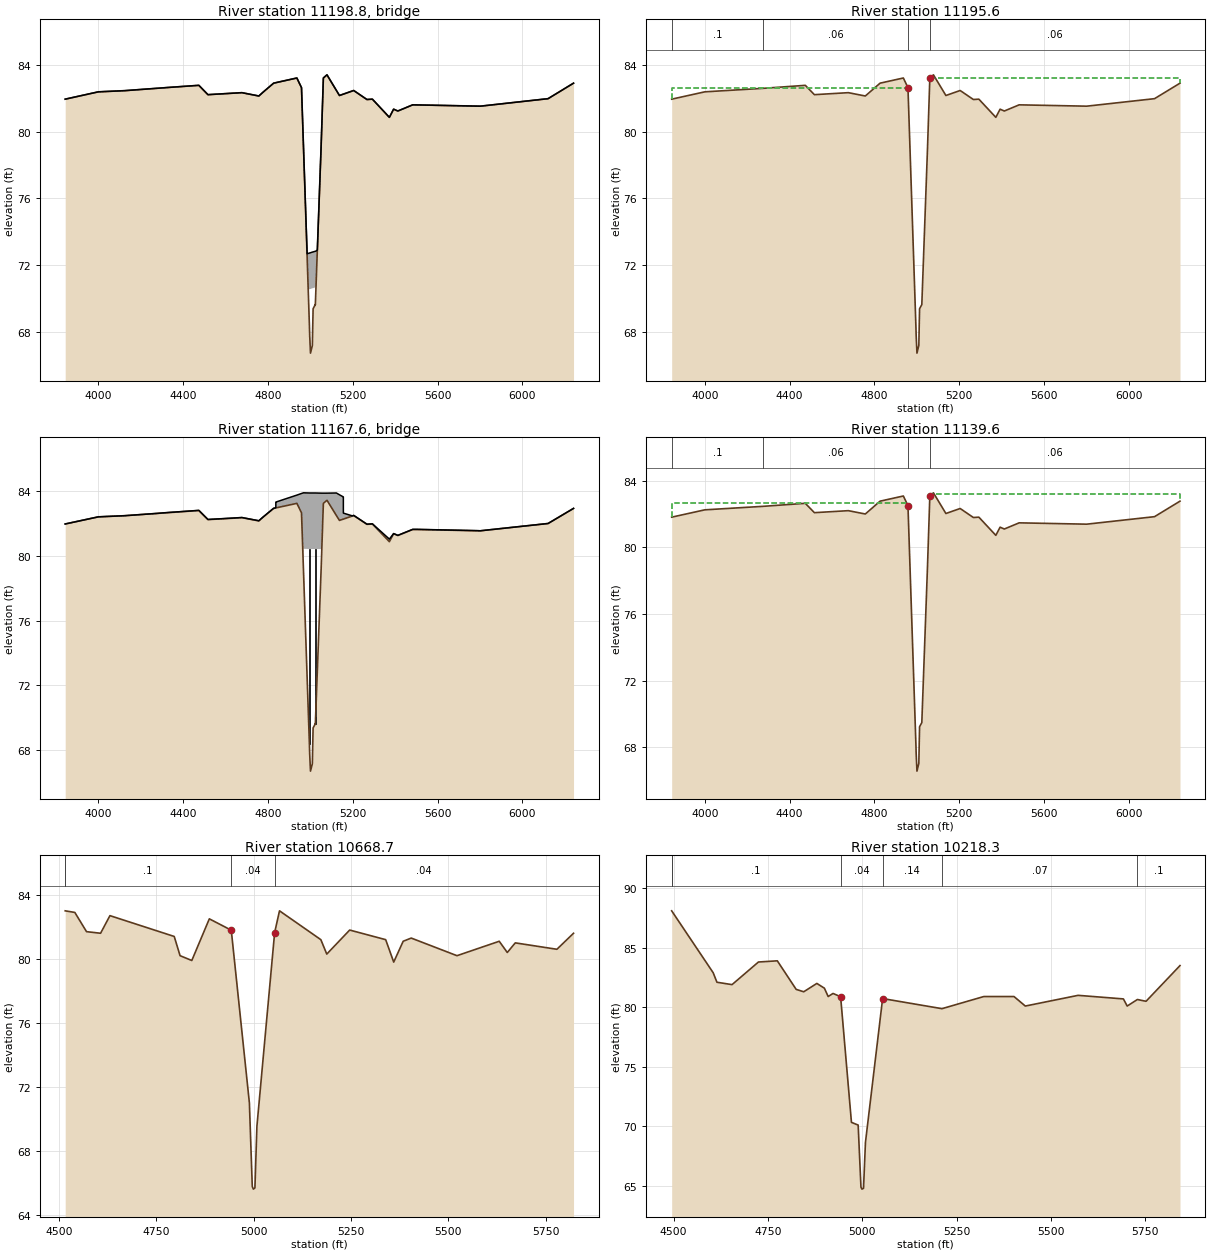
Type RM Length L Ch R = 3 ,11198.8 ,,,
BEGIN DESCRIPTION:
2 26" PIPLINES U/S OF RANKIN ROAD
END DESCRIPTION:
Bridge Culvert--1,0,-1,-1, 0
Deck Dist Width WeirC Skew NumUp NumDn MinLoCord MaxHiCord MaxSubmerge Is_Ogee
10,6,2.6,0, 42, 42, , , 0.95, 0, 1,1,,
    3844  4000.3  4124.1  4338.5  4474.1    4517    4677    4757 4777.01 4826.71
 4936.21 4958.11 4969.01 4984.71 4989.62 4989.71 4995.31 4996.81 5000.51 5009.31
 5010.21 5012.81 5023.31 5023.41  5026.3 5026.41 5032.81 5050.31 5061.21 5078.21
 5137.01 5204.21 5266.51  5292.4  5372.4  5392.4  5412.4  5482.4  5800.7  5801.3
  6120.7  6240.7
   81.95   82.39   82.46   82.66   82.78   82.22   82.34   82.14   82.37   82.91
   83.22   82.64    78.5   72.68    72.7    72.7   72.72   72.73   72.74   72.78
   72.78   72.79   72.83   72.83   72.84   72.84   72.91      79   83.22   83.41
   82.17   82.47   81.93   81.95   80.86   81.35   81.24   81.61   81.53   81.53
   81.98   82.91
   81.95   82.39   82.46   82.66   82.78   82.22   82.34   82.14   82.37   82.91
   83.22   82.64    78.5   72.48   70.59   70.56   70.55   70.56   70.57   70.61
   70.61   70.62   70.66   70.66   70.67   70.67    72.9      79   83.22   83.41
   82.17   82.47   81.93   81.95   80.86   81.35   81.24   81.61   81.53   81.53
   81.98   82.91
    3844  4000.3  4124.1  4338.5  4474.1    4517    4677    4757 4777.01 4826.71
 4936.21 4958.11 4969.01 4984.71 4989.62 4989.71 4995.31 4996.81 5000.51 5009.31
 5010.21 5012.81 5023.31 5023.41  5026.3 5026.41 5032.81 5050.31 5061.21 5078.21
 5137.01 5204.21 5266.51  5292.4  5372.4  5392.4  5412.4  5482.4  5800.7  5801.3
  6120.7  6240.7
   81.95   82.39   82.46   82.66   82.78   82.22   82.34   82.14   82.37   82.91
   83.22   82.64    78.5   72.68    72.7    72.7   72.72   72.73   72.74   72.78
   72.78   72.79   72.83   72.83   72.84   72.84   72.91      79   83.22   83.41
   82.17   82.47   81.93   81.95   80.86   81.35   81.24   81.61   81.53   81.53
   81.98   82.91
   81.95   82.39   82.46   82.66   82.78   82.22   82.34   82.14   82.37   82.91
   83.22   82.64    78.5   72.48   70.59   70.56   70.55   70.56   70.57   70.61
   70.61   70.62   70.66   70.66   70.67   70.67    72.9      79   83.22   83.41
   82.17   82.47   81.93   81.95   80.86   81.35   81.24   81.61   81.53   81.53
   81.98   82.91
BR Coef= 1 , 1 , 0 ,1.25, 0 ,,,0.8,0,2,0,
WSPro=,,,, 1 ,,,, 0 ,,,, 0 ,,,,-1 ,-1 ,-1 , 0 , 0 , 0 , 0 , 0
BR U #Sta/Elev= 42
    3844   81.95  4000.3   82.39  4124.1   82.46  4338.5   82.66  4474.1   82.78
    4517   82.22    4677   82.34    4757   82.14 4777.01   82.37 4826.71   82.91
 4936.21   83.22 4958.11   82.64 4969.01    78.5 4984.71   72.48 4989.62   70.59
 4989.71   70.56 4995.31   68.41 4996.81   67.76 5000.51   66.72 5009.31   67.18
 5010.21   67.79 5012.81   69.38 5023.31   69.64 5023.41   69.63  5026.3   70.64
 5026.41   70.67 5032.81    72.9 5050.31      79 5061.21   83.22 5078.21   83.41
 5137.01   82.17 5204.21   82.47 5266.51   81.93  5292.4   81.95  5372.4   80.86
  5392.4   81.35  5412.4   81.24  5482.4   81.61  5800.7   81.53  5801.3   81.53
  6120.7   81.98  6240.7   82.91
BR U #Mann= 5
    3844      .2  4338.5     .07 4958.11     .04 5061.21     .07  5801.3      .2
BR U Banks=4958.11,5061.21
BR D #Sta/Elev= 42
    3844   81.95  4000.3   82.39  4124.1   82.46  4338.5   82.66  4474.1   82.78
    4517   82.22    4677   82.34    4757   82.14 4777.01   82.37 4826.71   82.91
 4936.21   83.22 4958.11   82.64 4969.01    78.5 4984.71   72.48 4989.62   70.59
 4989.71   70.56 4995.31   68.41 4996.81   67.76 5000.51   66.72 5009.31   67.18
 5010.21   67.79 5012.81   69.38 5023.31   69.64 5023.41   69.63  5026.3   70.64
 5026.41   70.67 5032.81    72.9 5050.31      79 5061.21   83.22 5078.21   83.41
 5137.01   82.17 5204.21   82.47 5266.51   81.93  5292.4   81.95  5372.4   80.86
  5392.4   81.35  5412.4   81.24  5482.4   81.61  5800.7   81.53  5801.3   81.53
  6120.7   81.98  6240.7   82.91
BR D #Mann= 5
    3844      .2  4338.5     .07 4958.11     .04 5061.21     .07  5801.3      .2
BR D Banks=4958.11,5061.21
BC Design=,, 0 ,, 0 ,,,,,,
BC HTab HWMax=83.44
BC Use User HTab Curves=0
BC User HTab FreeFlow(D)= 0

Type RM Length L Ch R = 1 ,11195.6 ,56,56,56
BEGIN DESCRIPTION:
Upstream Section of Bridge/Culvert/Weir
END DESCRIPTION:
XS GIS Cut Line= 6
      3123066.48      13916679.8      3122395.01     13916652.69
      3121992.89     13916632.83      3121629.39     13916618.83
      3121287.65     13916299.65       3121279.7     13915809.03
#Sta/Elev= 30
    3844   81.95  4000.3   82.39  4275.4    82.6  4474.1   82.78    4517   82.22
    4677   82.34    4757   82.14  4826.7   82.91  4936.3   83.22  4958.1   82.64
  4995.3   68.41  4996.8   67.76  5000.5   66.72  5009.3   67.18  5012.8   69.38
  5023.4   69.63  5050.2      79  5061.2   83.22  5078.2   83.41    5137   82.17
  5204.2   82.47  5266.5   81.93  5292.4   81.95  5372.4   80.86  5392.4   81.35
  5412.4   81.24  5482.4   81.61  5800.7   81.53  6120.7   81.98  6240.7   82.91
#Mann= 4 , 1 , 0
    3844      .1       0  4275.4     .06       0  4958.1     .04       0
  5061.2     .06       0
#XS Ineff= 2 , 0
       0  4957.9   82.64  5061.3       0   83.22
Permanent Ineff=
       F       F
Bank Sta=4958.1,5061.2
XS Rating Curve= 0 ,0
Exp/Cntr=0.5,0.3

Type RM Length L Ch R = 3 ,11167.6 ,,,
BEGIN DESCRIPTION:
RANKIN ROAD
Structure ID: P40-4,,,,
END DESCRIPTION:
Bridge Culvert--1,0,-1,-1, 0
Deck Dist Width WeirC Skew NumUp NumDn MinLoCord MaxHiCord MaxSubmerge Is_Ogee
10,36,2.6,0, 59, 59, , , 0.95, 0, 1,1,,
    3844  4000.3  4124.1  4275.4  4309.8  4474.1    4517  4599.8  4639.8    4677
    4757    4776    4777  4826.7  4827.3 4836.99  4837.1 4837.21  4936.3  4958.1
  4967.2 4967.31  4967.4  4968.9    4969  4995.3  4996.8  5000.5  5009.3  5010.2
  5012.8  5023.3  5023.4  5050.2  5050.3 5051.49  5051.6  5051.7  5061.2  5078.2
  5122.6    5137 5155.29  5155.4 5155.51  5197.7  5204.2  5266.5    5281  5292.4
  5372.4  5392.4  5412.4  5482.4  5502.2  5789.4  5800.7  6120.7  6240.7
   81.95   82.39   82.46    82.6   82.64   82.79   82.23   82.29   82.32   82.35
   82.15   82.37   82.38   82.92   82.92   82.95    83.3    83.3   83.73   83.83
   83.87   83.87   83.87   83.87   83.87   83.86   83.86   83.86   83.86   83.86
   83.86   83.86   83.86   83.85   83.85   83.85   83.85   83.85   83.85   83.85
   83.86   83.75   83.62   83.62   82.62   82.45   82.48   81.94   81.95   81.96
   81.02   81.36   81.25   81.62   81.62   81.54   81.53   81.98   82.91
   81.95   82.39   82.46    82.6   82.63   82.78   82.22   82.28   82.31   82.34
   82.14   82.36   82.37   82.91   82.91   82.94   82.94   82.94   83.22   82.64
   79.18   79.14   80.42   80.42   80.42   80.41   80.41   80.41   80.41   80.41
   80.41   80.41   80.41    80.4    80.4    80.4   79.54   79.58   83.22   83.41
   82.47   82.17   82.25   82.25   82.25   82.44   82.47   81.93   81.94   81.95
   80.86   81.35   81.24   81.61   81.61   81.53   81.53   81.98   82.91
    3844  4000.3  4124.1  4275.4  4309.8  4474.1    4517  4599.8  4639.8    4677
    4757    4776    4777  4826.7  4827.3 4836.99  4837.1 4837.21  4936.3  4958.1
  4967.2 4967.31  4967.4  4968.9    4969  4995.3  4996.8  5000.5  5009.3  5010.2
  5012.8  5023.3  5023.4  5050.2  5050.3 5051.49  5051.6  5051.7  5061.2  5078.2
  5122.6    5137 5155.29  5155.4 5155.51  5197.7  5204.2  5266.5    5281  5292.4
  5372.4  5392.4  5412.4  5482.4  5502.2  5789.4  5800.7  6120.7  6240.7
   81.95   82.39   82.46    82.6   82.64   82.79   82.23   82.29   82.32   82.35
   82.15   82.37   82.38   82.92   82.92   82.95    83.3    83.3   83.73   83.83
   83.87   83.87   83.87   83.87   83.87   83.86   83.86   83.86   83.86   83.86
   83.86   83.86   83.86   83.85   83.85   83.85   83.85   83.85   83.85   83.85
   83.86   83.75   83.62   83.62   82.62   82.45   82.48   81.94   81.95   81.96
   81.02   81.36   81.25   81.62   81.62   81.54   81.53   81.98   82.91
   81.83   82.27   82.34   82.48   82.51   82.66    82.1   82.16   82.19   82.22
   82.02   82.24   82.25   82.79   82.79   82.82   82.82   82.82    83.1   82.52
   79.06   79.02    80.3    80.3    80.3   80.29   80.29   80.29   80.29   80.29
   80.29   80.29   80.29   80.28   80.28   80.28   79.42   79.46    83.1   83.29
   82.35   82.05   82.13   82.13   82.13   82.32   82.35   81.81   81.82   81.83
   80.74   81.23   81.12   81.49   81.49   81.41   81.41   81.86   82.79
Pier Skew, UpSta & Num, DnSta & Num=  ,4995.3, 2 ,4995.3, 2 , 0 , 0 , 0 ,,
       2       2
   66.98   81.41
       2       2
   66.86   81.29
Pier Skew, UpSta & Num, DnSta & Num=  ,5023.4, 2 ,5023.4, 2 , 0 , 0 , 0 ,,
       2       2
   68.62   81.41
       2       2
    68.5   81.29
Abutment Skew #Up #Dn= , 2 , 2
  4967.2    4969
   80.42    78.5
  4967.2    4969
    80.3   78.38
Abutment Skew #Up #Dn= , 2 , 2
  5050.3 5051.69
   79.04    80.4
  5050.3 5051.69
   78.92   80.28
BR Coef= 1 , 1 , 0 ,1.25, 0 ,,,0.8,0,2,0,
WSPro=,,,, 1 ,,,, 0 ,,,, 0 ,,,,-1 ,-1 ,-1 , 0 , 0 , 0 , 0 , 0
BR U #Sta/Elev= 59
    3844   81.95  4000.3   82.39  4124.1   82.46  4275.4    82.6  4309.8   82.63
  4474.1   82.78    4517   82.22  4599.8   82.28  4639.8   82.31    4677   82.34
    4757   82.14    4776   82.36    4777   82.37  4826.7   82.91  4827.3   82.91
 4836.99   82.94  4837.1   82.94 4837.21   82.94  4936.3   83.22  4958.1   82.64
  4967.2   79.18 4967.31   79.14  4967.4   79.11  4968.9   78.54    4969    78.5
  4995.3   68.41  4996.8   67.76  5000.5   66.72  5009.3   67.18  5010.2   67.79
  5012.8   69.38  5023.3   69.64  5023.4   69.63  5050.2      79  5050.3   79.04
 5051.49   79.49  5051.6   79.54  5051.7   79.58  5061.2   83.22  5078.2   83.41
  5122.6   82.47    5137   82.17 5155.29   82.25  5155.4   82.25 5155.51   82.25
  5197.7   82.44  5204.2   82.47  5266.5   81.93    5281   81.94  5292.4   81.95
  5372.4   80.86  5392.4   81.35  5412.4   81.24  5482.4   81.61  5502.2   81.61
  5789.4   81.53  5800.7   81.53  6120.7   81.98  6240.7   82.91
BR U #Mann= 4
    3844      .1  4275.4     .06  4958.1     .04  5061.2     .06
BR U Banks=4958.1,5061.2
BR D #Sta/Elev= 59
    3844   81.83  4000.3   82.27  4124.1   82.34  4275.4   82.48  4309.8   82.51
  4474.1   82.66    4517    82.1  4599.8   82.16  4639.8   82.19    4677   82.22
    4757   82.02    4776   82.24    4777   82.25  4826.7   82.79  4827.3   82.79
 4836.99   82.82  4837.1   82.82 4837.21   82.82  4936.3    83.1  4958.1   82.52
  4967.2   79.06 4967.31   79.02  4967.4   78.99  4968.9   78.42    4969   78.38
  4995.3   68.29  4996.8   67.64  5000.5    66.6  5009.3   67.06  5010.2   67.67
  5012.8   69.26  5023.3   69.52  5023.4   69.51  5050.2   78.88  5050.3   78.92
 5051.49   79.37  5051.6   79.42  5051.7   79.46  5061.2    83.1  5078.2   83.29
  5122.6   82.35    5137   82.05 5155.29   82.13  5155.4   82.13 5155.51   82.13
  5197.7   82.32  5204.2   82.35  5266.5   81.81    5281   81.82  5292.4   81.83
  5372.4   80.74  5392.4   81.23  5412.4   81.12  5482.4   81.49  5502.2   81.49
  5789.4   81.41  5800.7   81.41  6120.7   81.86  6240.7   82.79
BR D #Mann= 4
    3844      .1  4275.4     .06  4958.1     .04  5061.2     .06
BR D Banks=4958.1,5061.2
BC Design=,, 0 ,, 0 ,,,,,,
BC HTab HWMax=83.41
BC Use User HTab Curves=0
BC User HTab FreeFlow(D)= 0

Type RM Length L Ch R = 1 ,11139.6 ,470.9,470.9,470.9
BEGIN DESCRIPTION:
Downstream Section of Bridge/Culvert/Weir
END DESCRIPTION:
XS GIS Cut Line= 6
       3123064.7     13916623.83      3122393.23     13916596.71
      3121991.11     13916576.85      3121627.61     13916562.85
      3121285.87     13916243.67      3121277.92     13915753.06
#Sta/Elev= 30
    3844   81.81  4000.3   82.25  4275.4   82.46  4474.1   82.64    4517   82.08
    4677    82.2    4757      82  4826.7   82.77  4936.3   83.08  4958.1    82.5
  4995.3   68.27  4996.8   67.62  5000.5   66.58  5009.3   67.04  5012.8   69.24
  5023.4   69.49  5050.2   78.86  5061.2   83.08  5078.2   83.27    5137   82.03
  5204.2   82.33  5266.5   81.79  5292.4   81.81  5372.4   80.72  5392.4   81.21
  5412.4    81.1  5482.4   81.47  5800.7   81.39  6120.7   81.84  6240.7   82.77
#Mann= 4 , 1 , 0
    3844      .1       0  4275.4     .06       0  4958.1     .04       0
  5061.2     .06       0
#XS Ineff= 2 , 0
       0  4957.9   82.64  5061.3       0   83.22
Permanent Ineff=
       F       F
Bank Sta=4958.1,5061.2
XS Rating Curve= 0 ,0
Exp/Cntr=0.5,0.3

Type RM Length L Ch R = 1 ,10668.7 ,438.5,450.4,479.2
BEGIN DESCRIPTION:
Cross Section 10668.7-Interpolated
END DESCRIPTION:
XS GIS Cut Line= 5
      3122417.22     13916119.04      3121985.25     13916106.58
      3121868.95     13916102.42      3121590.66     13916060.89
      3121297.57      13915687.5
#Sta/Elev= 30
  4516.5      83  4541.2    82.9  4571.2    81.7  4607.3    81.6  4631.3    82.7
  4796.3    81.4  4811.3    80.2  4841.4    79.9  4886.4    82.5  4942.7   81.79
  4989.2   71.01  4996.6    65.8  4999.3   65.63  5003.4    65.7  5008.5   69.55
    5054   81.64  5066.5      83  5172.6    81.2  5187.8    80.3  5246.6    81.8
    5339    81.2  5359.6    79.8  5383.9    81.1  5404.5    81.3    5522    80.2
  5630.4    81.1  5651.1    80.4  5671.6      81  5778.4    80.6  5821.1    81.6
#Mann= 4 , 1 , 0
  4516.5      .2       0  4516.5      .1       0  4942.7     .04       0
    5054     .04       0
#XS Ineff= 2 , 0
       0  4886.4    82.5               0
Permanent Ineff=
       F       F
Bank Sta=4942.7,5054
XS Rating Curve= 0 ,0
Exp/Cntr=0.3,0.1

Type RM Length L Ch R = 1 ,10218.3 ,887.7,975.4,1172.3
BEGIN DESCRIPTION:
Cross Section  10218.3
END DESCRIPTION:
XS GIS Cut Line= 5
      3122452.84      13915921.9      3122123.22     13915723.38
      3121928.45      13915618.5      3121707.45     13915607.26
      3121189.36     13915563.11
#Sta/Elev= 30
  4494.9    88.1  4604.9    82.9  4614.9    82.1  4654.9    81.9  4724.9    83.8
  4774.9    83.9  4824.9    81.5  4844.9    81.3  4879.7      82  4899.7    81.6
  4909.7    80.9  4922.6   81.16  4942.7   80.88  4971.4   70.33  4989.2    70.1
  4996.6   64.89  4999.3   64.72  5003.4   64.79  5008.5   68.64    5054   80.73
  5211.3   79.88  5322.2    80.9  5402.2    80.9  5432.2    80.1  5572.2      81
  5692.2    80.7  5702.2    80.1  5729.3   80.65  5752.2    80.5  5842.2    83.5
#Mann= 6 , 1 , 0
  4494.9      .2       0  4494.9      .1       0  4942.7     .04       0
    5054     .14       0  5211.3     .07       0  5729.3      .1       0
Bank Sta=4942.7,5054
XS Rating Curve= 0 ,0
Exp/Cntr=0.3,0.1

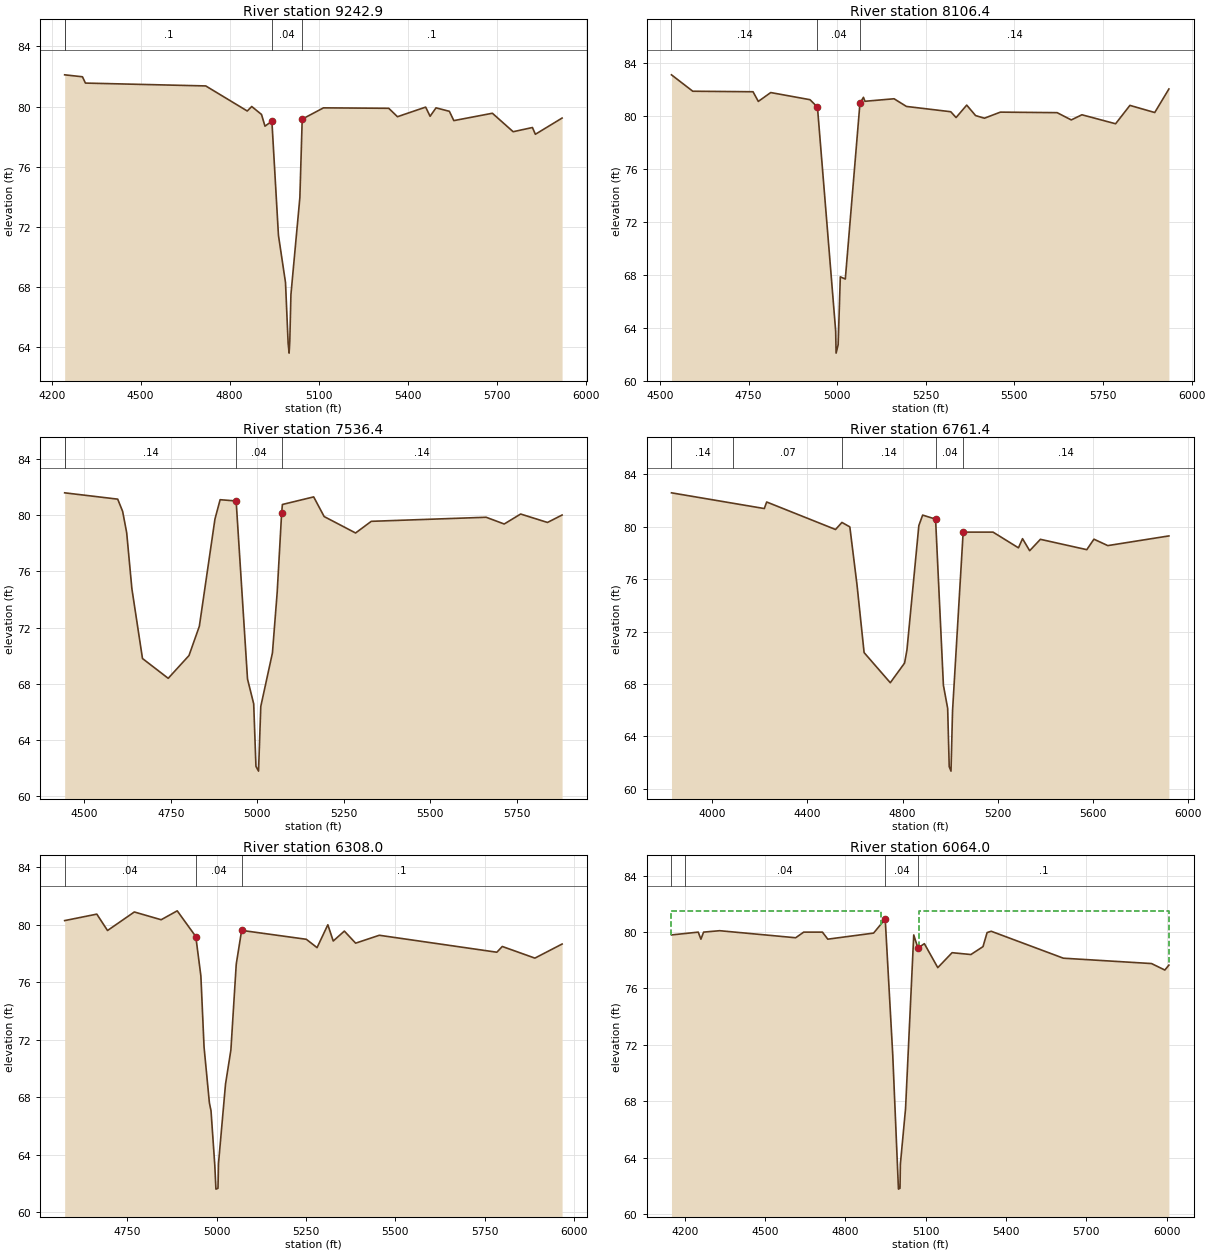
Type RM Length L Ch R = 1 ,9242.9  ,1196.5,1136.5,587.7
BEGIN DESCRIPTION:
Cross Section 9242.9
END DESCRIPTION:
XS GIS Cut Line= 6
       3122786.2     13916146.64      3122782.46     13915670.94
      3122864.86     13915536.09      3122891.08     13915333.83
      3122912.33     13915065.27      3122406.28     13914802.88
#Sta/Elev= 30
  4243.8   82.11  4303.8   81.98  4313.8   81.56  4719.5   81.37  4859.5    79.7
  4874.5      80  4907.5   79.47  4919.2   78.69  4942.5   79.02  4964.6   71.42
  4988.4   68.27  4997.2   64.25  5000.5   63.57  5002.8   64.33  5006.7   67.48
  5036.8   73.93  5044.7   79.16  5116.5   79.91  5336.5   79.88  5365.9   79.32
  5460.9   79.96  5475.9   79.35  5495.9   79.91  5540.9   79.68  5555.9   79.06
  5685.9   79.55  5755.9   78.32  5820.9    78.6  5830.9   78.15  5920.9   79.23
#Mann= 4 , 1 , 0
  4243.8      .2       0  4243.8      .1       0  4942.5     .04       0
  5044.7      .1       0
Bank Sta=4942.5,5044.7
XS Rating Curve= 0 ,0
Exp/Cntr=0.3,0.1

Type RM Length L Ch R = 1 ,8106.4  ,614.6,570,173.9
BEGIN DESCRIPTION:
Cross Section 8106.4
END DESCRIPTION:
XS GIS Cut Line= 5
      3124400.81     13915678.38      3124069.47     13915471.29
      3123910.65     13915354.43      3123405.83      13914898.3
      3123278.16     13914854.35
#Sta/Elev= 30
  4532.5   83.13  4592.5   81.89  4762.5   81.85  4777.5   81.12  4812.5   81.79
  4923.3   81.25  4944.3   80.69  4995.7   63.77  4996.9   62.09  5002.7   62.72
  5008.8   67.86  5022.9   67.69  5064.2   80.98  5074.1   81.43  5078.3   81.13
  5160.4   81.32  5195.4   80.74  5320.4   80.34  5335.4    79.9  5365.4   80.84
  5390.4   80.05  5415.4   79.85  5460.4   80.31  5620.4   80.27  5660.4   79.72
  5690.4   80.11  5785.4   79.43  5825.8   80.82  5895.8   80.28  5935.8   82.06
#Mann= 3 , 1 , 0
  4532.5     .14       0  4944.3     .04       0  5064.2     .14       0
Bank Sta=4944.3,5064.2
XS Rating Curve= 0 ,0
Exp/Cntr=0.3,0.1

Type RM Length L Ch R = 1 ,7536.4  ,764.7,775,725
BEGIN DESCRIPTION:
Cross Section 7536.4-Interpolated
END DESCRIPTION:
XS GIS Cut Line= 5
       3124611.7     13914888.59      3124118.53     13914865.82
      3123936.43     13914858.24        3123479.     13914793.91
      3123193.98     13914697.53
#Sta/Elev= 30
  4442.7    81.6  4596.1   81.15  4610.4   80.28  4622.1   78.76  4637.1   74.78
  4667.8    69.8  4742.2   68.39  4802.3   70.01  4832.3    72.1  4877.4   79.73
  4892.4   81.11  4938.7   81.02  4971.6   68.34  4989.5   66.57    4996   62.12
  5003.5   61.78    5010   66.39  5043.7    70.2  5057.5   74.54  5070.3   80.16
  5072.5   80.77    5163   81.31  5193.3   79.91  5284.2   78.74  5329.6   79.57
  5661.8   79.86  5714.1   79.38  5761.6   80.09  5839.3   79.49  5881.5   80.02
#Mann= 4 , 1 , 0
  4442.7      .2       0  4442.7     .14       0  4938.7     .04       0
  5070.3     .14       0
#XS Ineff= 2 , 0
       0    4892    80.5               0
Permanent Ineff=
       F       F
Bank Sta=4938.7,5070.3
XS Rating Curve= 0 ,0
Exp/Cntr=0.3,0.1

Type RM Length L Ch R = 1 ,6761.4  ,472.9,453.4,395.6
BEGIN DESCRIPTION:
Cross Section 6761.4
END DESCRIPTION:
XS GIS Cut Line= 6
       3125160.2     13914506.41      3124653.79     13914185.78
       3124216.3     13914098.88       3123949.6     13914077.91
      3123606.71     13914083.56      3123172.51     13914085.38
#Sta/Elev= 30
    3829    82.6  4088.8    81.8    4219    81.4    4229    81.9  4518.4    79.8
  4545.2   80.34  4578.4      80  4608.4    75.6  4638.4    70.4  4748.4    68.1
  4808.4    69.6  4818.4    70.6  4868.4    80.1  4884.4    80.9  4938.7   80.59
  4971.6   67.91  4989.5   66.14    4996   61.69  5003.5   61.35    5010   65.96
  5054.6    79.6  5180.1    79.6  5286.9    78.4  5304.1    79.1  5334.1   78.18
  5379.1   79.05  5574.1   78.26  5604.1   79.06  5662.3   78.57  5919.1   79.31
#Mann= 6 , 1 , 0
    3829      .2       0    3829     .14       0  4088.8     .07       0
  4545.2     .14       0  4938.7     .04       0  5054.6     .14       0
#XS Ineff= 2 , 0
       0    4884    80.5               0
Permanent Ineff=
       F       F
Bank Sta=4938.7,5054.6
XS Rating Curve= 0 ,0
Exp/Cntr=0.3,0.1

Type RM Length L Ch R = 1 ,6308.0  ,263.4,244,34.5
BEGIN DESCRIPTION:
Cross Section 6308.0-Interpolated
END DESCRIPTION:
XS GIS Cut Line= 6
      3124537.47     13913630.12      3124182.92     13913640.13
      3124035.39     13913631.73      3123659.34     13913671.93
      3123418.69     13913726.27       3123157.5     13913771.13
#Sta/Elev= 30
  4574.5    80.3  4664.5   80.75  4694.5   79.61  4769.5    80.9  4844.6   80.36
  4889.6   80.98  4941.6   79.19  4955.8   76.45  4964.7    71.5  4979.7   67.61
  4984.2   67.07  4994.8   63.27 4997.92   61.62 5003.72   61.68 5005.11    63.4
  5024.8   68.93  5039.8    71.3  5054.8   77.27  5069.9   79.62  5250.9      79
    5281   78.42  5311.2   80.01  5326.3   78.88  5357.4   79.57    5389   78.73
  5455.2   79.28  5784.3    78.1  5799.5    78.5  5890.8   77.69  5966.9   78.67
#Mann= 3 , 1 , 0
  4574.5     .04       0  4941.6     .04       0  5069.9      .1       0
Bank Sta=4941.6,5069.9
XS Rating Curve= 0 ,0
Exp/Cntr=0.5,0.3

Type RM Length L Ch R = 1 ,6064.0  ,123.2,123.2,123.2
BEGIN DESCRIPTION:
Upstream Section of Bridge/Culvert/Weir
END DESCRIPTION:
XS GIS Cut Line= 6
       3124768.2     13912890.77      3124396.21     13913249.47
      3124006.66     13913501.18      3123713.01     13913612.05
      3123432.49     13913671.44      3123156.48     13913673.36
#Sta/Elev= 30
  4149.9   79.79  4200.4   79.89  4249.9   79.99  4259.9   79.49  4269.9   79.99
  4329.9   80.09  4613.9   79.59  4643.9   79.99  4713.9   79.99  4733.9   79.49
    4905   79.92 4948.47   80.92 4976.53   71.32 4997.92   61.76 5003.72   61.82
 5005.11   63.54 5024.42   67.46 5055.06   79.79 5070.67   78.86 5094.74   79.17
 5144.88   77.47 5198.31   78.53 5268.63    78.4  5313.8   78.96  5329.2   79.96
  5344.6   80.05  5614.2   78.14  5943.4   77.76  5993.3    77.3  6008.4   77.65
#Mann= 4 , 1 , 0
  4149.9      .2       0  4200.4     .04       0 4948.47     .04       0
 5070.67      .1       0
#XS Ineff= 2 , 0
       0    4931    81.5    5075       0    81.5
Permanent Ineff=
       F       F
Bank Sta=4948.47,5070.67
XS Rating Curve= 0 ,0
Exp/Cntr=0.5,0.3

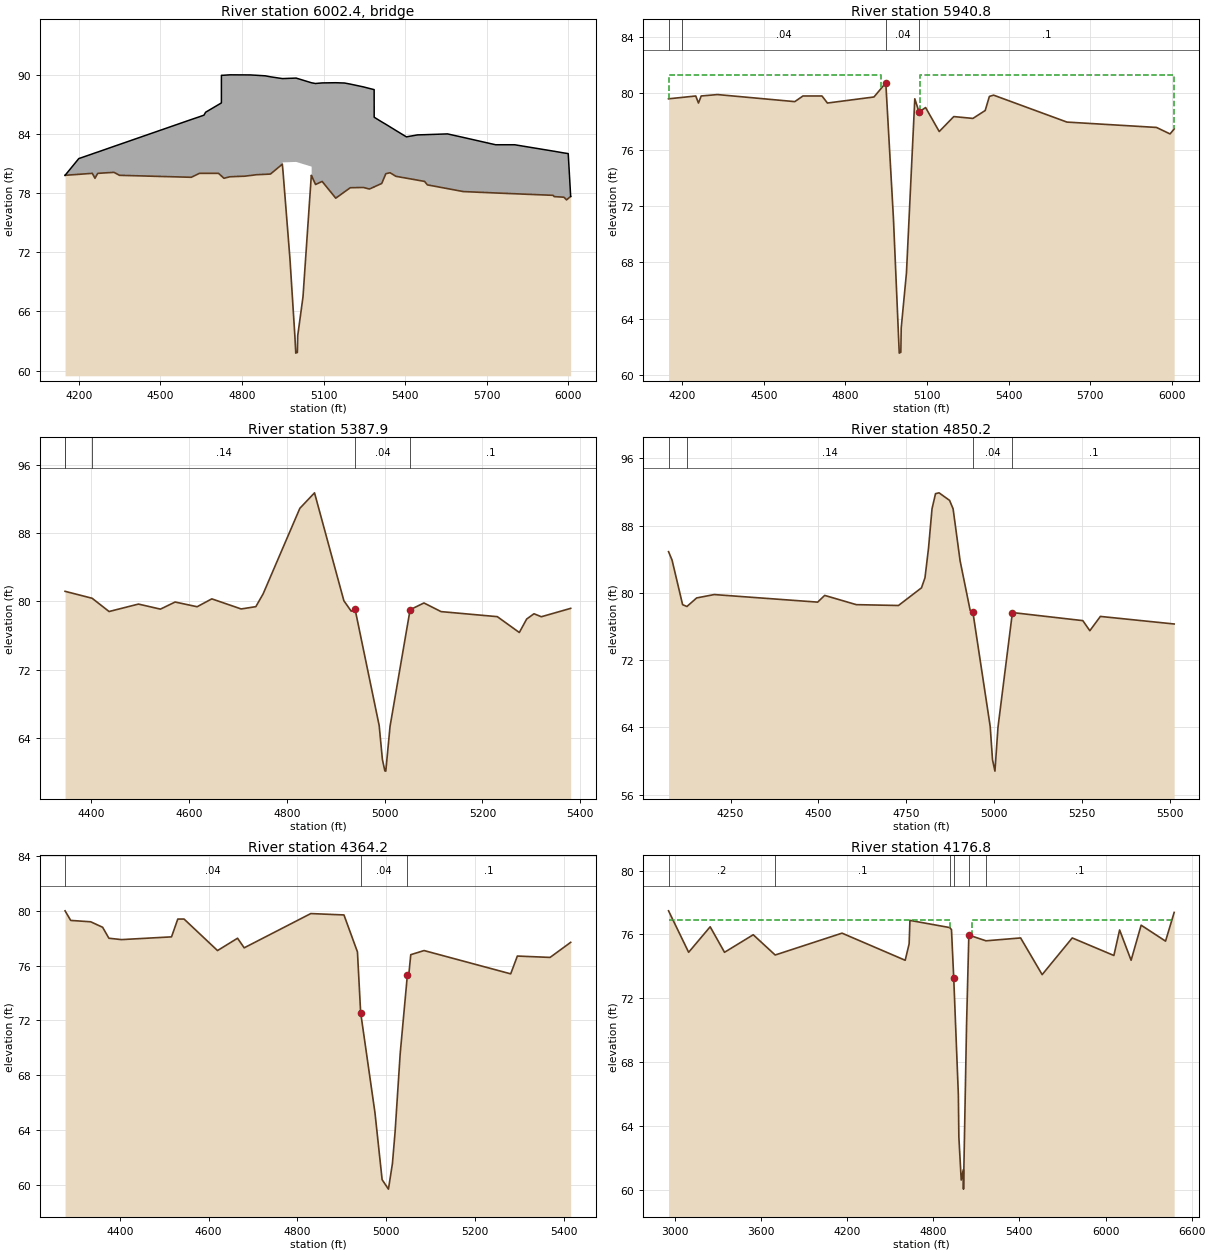
Type RM Length L Ch R = 3 ,6002.4  ,,,
BEGIN DESCRIPTION:
HARDY AIRPORT CONNECTOR, SKEW ANGLE OF 30 DEGREES
Structure ID: P40-3,,,,
END DESCRIPTION:
Bridge Culvert--1,0,-1,-1, 0
Deck Dist Width WeirC Skew NumUp NumDn MinLoCord MaxHiCord MaxSubmerge Is_Ogee
10,103.2,2.6,0, 52, 52, , , 0.95, 0, 1,1,,
  4149.9  4200.4  4249.9  4259.9  4269.9  4329.9  4349.9  4613.9  4643.9  4660.4
  4666.6  4713.9 4724.49  4724.6  4733.9 4755.44    4831  4885.7    4905 4948.47
 4949.77 4949.86 4999.31 5056.27 5056.38 5070.67 5094.74 5144.88    5177 5198.31
 5246.03 5268.63    5286 5286.11  5313.8  5329.2  5344.6  5365.8  5404.5  5445.6
  5471.4  5481.7  5555.6  5614.2  5732.4  5802.4  5943.4  5947.9  5983.4  5993.3
  5999.4  6008.4
    79.8    81.5   81.97   82.07   82.16   82.74   82.93   85.46   85.74    85.9
    86.2   86.97   87.14   89.94   89.95   89.99   89.98   89.89   89.79   89.61
   89.61   89.61   89.66   89.18   89.18   89.11   89.17   89.19   89.16   89.05
   88.77   88.61   88.49   85.69   85.22   84.97   84.71   84.35    83.7    83.9
   83.92   83.93      84   83.64    82.9    82.9   82.26   82.24   82.07   82.03
      82   77.66
    79.8    79.9      80    79.5      80    80.1    79.8    79.6      80      80
      80      80   79.74   79.73    79.5   79.65   79.78    79.9   79.93   80.93
   80.55   81.11   81.16   80.68   79.72   78.87   79.18   77.48   78.12   78.54
   78.57   78.41   78.63   78.63   78.97   79.97   80.06    79.7   79.51   79.31
   79.18   78.83   78.45   78.15   78.01   77.93   77.77   77.64   77.58   77.31
   77.45   77.66
  4149.9  4200.4  4249.9  4259.9  4269.9  4329.9  4349.9  4613.9  4643.9  4660.4
  4666.6  4713.9 4724.49  4724.6  4733.9 4755.44    4831  4885.7    4905 4948.47
 4949.77 4949.86 4999.31 5056.27 5056.38 5070.67 5094.74 5144.88    5177 5198.31
 5246.03 5268.63    5286 5286.11  5313.8  5329.2  5344.6  5365.8  5404.5  5445.6
  5471.4  5481.7  5555.6  5614.2  5732.4  5802.4  5943.4  5947.9  5983.4  5993.3
  5999.4  6008.4
    79.8    81.5   81.97   82.07   82.16   82.74   82.93   85.46   85.74    85.9
    86.2   86.97   87.14   89.94   89.95   89.99   89.98   89.89   89.79   89.61
   89.61   89.61   89.66   89.18   89.18   89.11   89.17   89.19   89.16   89.05
   88.77   88.61   88.49   85.69   85.22   84.97   84.71   84.35    83.7    83.9
   83.92   83.93      84   83.64    82.9    82.9   82.26   82.24   82.07   82.03
      82   77.66
   79.63   79.73   79.83   79.33   79.83   79.93   79.63   79.43   79.83   79.83
   79.83   79.83   79.57   79.56   79.33   79.48   79.61   79.73   79.76   80.76
   80.38   80.94   80.99   80.51   79.55    78.7   79.01   77.31   77.95   78.37
    78.4   78.24   78.46   78.46    78.8    79.8   79.89   79.53   79.34   79.14
   79.01   78.66   78.28   77.98   77.84   77.76    77.6   77.47   77.41   77.14
   77.28   77.49
Abutment Skew #Up #Dn= , 2 , 2
 4949.66 4950.81
   81.11   80.25
 4949.66 4950.81
   80.94   80.08
Abutment Skew #Up #Dn= , 2 , 2
 5055.16 5056.47
   79.79   80.68
 5055.16 5056.47
   79.62   80.51
BR Coef= 1 , 1 , 0 ,1.25, 0 ,,,0.8,0,2,0,
WSPro=,,,, 1 ,,,, 0 ,,,, 0 ,,,,-1 ,-1 ,-1 , 0 , 0 , 0 , 0 , 0
BR U #Sta/Elev= 74
  4149.9    79.8  4200.4    79.9  4249.9      80  4259.9    79.5  4269.9      80
  4329.9    80.1  4349.9    79.8  4613.9    79.6  4643.9      80  4660.4      80
  4666.6      80  4713.9      80  4724.4   79.74 4724.49   79.74  4724.6   79.73
 4724.71   79.73  4733.9    79.5 4755.44   79.65  4778.8   79.68 4809.13   79.71
    4831   79.78 4853.13   79.86  4885.7    79.9    4905   79.93  4942.1   80.78
 4948.47   80.93 4949.77   80.55 4949.86   80.53 4950.71   80.28 4950.81   80.25
 4976.53   71.33  4994.8   63.42 4997.92   61.77 4999.31   61.82 5003.72   61.83
  5004.2   62.42 5005.11   63.55 5024.42   67.47 5055.06    79.8 5055.16   79.79
 5056.27   79.73 5056.38   79.72  5065.1    79.2 5070.67   78.87 5094.74   79.18
  5119.3   78.35 5144.88   77.48    5177   78.12 5198.31   78.54  5232.7   78.56
 5246.03   78.57 5268.63   78.41  5285.8   78.62 5285.89   78.62    5286   78.63
 5286.11   78.63  5313.8   78.97  5329.2   79.97  5344.6   80.06  5365.8    79.7
  5404.5   79.51  5445.6   79.31  5471.4   79.18  5481.7   78.83  5555.6   78.45
  5614.2   78.15  5732.4   78.01  5802.4   77.93  5943.4   77.77  5947.9   77.64
  5983.4   77.58  5993.3   77.31  5999.4   77.45  6008.4   77.66
BR U #Mann= 4
  4149.9      .2  4200.4     .04 4948.47     .04 5070.67      .1
BR U Banks=4948.47,5070.67
BR D #Sta/Elev= 74
  4149.9   79.63  4200.4   79.73  4249.9   79.83  4259.9   79.33  4269.9   79.83
  4329.9   79.93  4349.9   79.63  4613.9   79.43  4643.9   79.83  4660.4   79.83
  4666.6   79.83  4713.9   79.83  4724.4   79.57 4724.49   79.57  4724.6   79.56
 4724.71   79.56  4733.9   79.33 4755.44   79.48  4778.8   79.51 4809.13   79.54
    4831   79.61 4853.13   79.69  4885.7   79.73    4905   79.76  4942.1   80.61
 4948.47   80.76 4949.77   80.38 4949.86   80.36 4950.71   80.11 4950.81   80.08
 4976.53   71.16  4994.8   63.25 4997.92    61.6 4999.31   61.65 5003.72   61.66
  5004.2   62.25 5005.11   63.38 5024.42    67.3 5055.06   79.63 5055.16   79.62
 5056.27   79.56 5056.38   79.55  5065.1   79.03 5070.67    78.7 5094.74   79.01
  5119.3   78.18 5144.88   77.31    5177   77.95 5198.31   78.37  5232.7   78.39
 5246.03    78.4 5268.63   78.24  5285.8   78.45 5285.89   78.45    5286   78.46
 5286.11   78.46  5313.8    78.8  5329.2    79.8  5344.6   79.89  5365.8   79.53
  5404.5   79.34  5445.6   79.14  5471.4   79.01  5481.7   78.66  5555.6   78.28
  5614.2   77.98  5732.4   77.84  5802.4   77.76  5943.4    77.6  5947.9   77.47
  5983.4   77.41  5993.3   77.14  5999.4   77.28  6008.4   77.49
BR D #Mann= 4
  4149.9      .2  4200.4     .04 4948.47     .04 5070.67      .1
BR D Banks=4948.47,5070.67
BC Design=,, 0 ,, 0 ,,,,,,
BC HTab HWMax=80.92
BC Use User HTab Curves=0
BC User HTab FreeFlow(D)= 0

Type RM Length L Ch R = 1 ,5940.8  ,552.9,552.9,552.9
BEGIN DESCRIPTION:
Downstream Section of Bridge/Culvert/Weir
END DESCRIPTION:
XS GIS Cut Line= 6
      3124773.94      13912767.7      3124401.95     13913126.41
       3124012.4     13913378.12      3123718.75     13913488.99
      3123438.23     13913548.38      3123162.22      13913550.3
#Sta/Elev= 30
  4149.9    79.6  4200.4    79.7  4249.9    79.8  4259.9    79.3  4269.9    79.8
  4329.9    79.9  4613.9    79.4  4643.9    79.8  4713.9    79.8  4733.9    79.3
    4905   79.73 4948.47   80.73 4976.53   71.13 4997.92   61.57 5003.72   61.63
 5005.11   63.35 5024.42   67.27 5055.06    79.6 5070.67   78.67 5094.74   78.98
 5144.88   77.28 5198.31   78.34 5268.63   78.21  5313.8   78.77  5329.2   79.77
  5344.6   79.86  5614.2   77.95  5943.4   77.57  5993.3   77.11  6008.4   77.46
#Mann= 4 , 1 , 0
  4149.9      .2       0  4200.4     .04       0 4948.47     .04       0
 5070.67      .1       0
#XS Ineff= 2 , 0
       0    4931    81.3    5075       0    81.3
Permanent Ineff=
       F       F
Bank Sta=4948.47,5070.67
XS Rating Curve= 0 ,0
Exp/Cntr=0.5,0.3

Type RM Length L Ch R = 1 ,5387.9  ,532.7,537.7,600.9
BEGIN DESCRIPTION:
Cross Section 5387.9-Interpolated
END DESCRIPTION:
XS GIS Cut Line= 4
      3124808.27     13912717.08      3124218.28     13912717.08
       3124109.6     13912717.08      3123774.61     13912716.84
#Sta/Elev= 30
  4346.8   81.18  4402.1   80.37  4436.8   78.82  4496.8   79.69  4541.8    79.1
  4571.8   79.93  4616.8   79.38  4646.8    80.3  4706.8   79.12  4736.8   79.39
  4751.8   80.89  4826.8   90.88  4856.8   92.69  4916.8   80.08  4931.8   78.86
  4939.7   79.09    4989   65.49  4995.6   61.52  5000.6    60.2  5002.5   60.17
  5011.2    65.4  5052.2   79.03  5080.5   79.82  5115.5   78.81  5230.5   78.22
  5275.5   76.37  5290.5   77.94  5305.5   78.56  5320.5   78.21  5380.5   79.19
#Mann= 5 , 1 , 0
  4346.8      .2       0  4346.8     .04       0  4402.1     .14       0
  4939.7     .04       0  5052.2      .1       0
Bank Sta=4939.7,5052.2
XS Rating Curve= 0 ,0
Exp/Cntr=0.3,0.1

Type RM Length L Ch R = 1 ,4850.2  ,489,486,482.6
BEGIN DESCRIPTION:
Cross Section 4850.2
END DESCRIPTION:
XS GIS Cut Line= 5
      3125079.82     13912385.75      3124836.14     13912312.65
      3124406.12     13912196.03      3123997.96     13912166.88
      3123668.49     13912149.23
#Sta/Elev= 30
  4073.5    84.9  4083.5    83.9  4113.5    78.6  4125.8   78.38  4153.5    79.4
  4203.5    79.8  4497.9    78.9  4517.9    79.7  4607.9    78.6  4727.9    78.5
  4793.4    80.6  4803.4    81.8  4813.4    85.3  4823.4      90  4833.4    91.8
  4843.4    91.9  4873.4      91  4883.4      90  4903.4    83.8  4932.1    77.9
  4939.7   77.72    4989   64.12  4995.6   60.15  5002.5    58.8  5011.2   64.03
  5052.2   77.66  5252.6    76.7  5272.6    75.5  5302.6    77.2  5512.6    76.3
#Mann= 4 , 1 , 0
  4073.5     .07       0  4125.8     .14       0  4939.7     .04       0
  5052.2      .1       0
Bank Sta=4939.7,5052.2
XS Rating Curve= 0 ,0
Exp/Cntr=0.3,0.1

Type RM Length L Ch R = 1 ,4364.2  ,185.1,187.4,242.7
BEGIN DESCRIPTION:
Cross Section 4364.2-Interpolated
END DESCRIPTION:
XS GIS Cut Line= 6
      3124925.08     13911729.89      3124525.48     13911703.55
      3124342.62     13911699.85       3124259.5     13911696.16
       3124137.6     13911692.46      3123787.47     13911679.42
#Sta/Elev= 30
  4276.7      80  4289.4    79.3  4334.4    79.2  4361.3    78.8  4375.4      78
  4403.6    77.9  4516.5    78.1  4530.6    79.4  4544.7    79.4  4620.1    77.1
  4665.2      78  4680.2    77.3  4830.2    79.8  4904.9    79.7  4935.3      77
 4942.49   72.58 4974.69   65.28 4990.89   60.38 5005.09   59.69 5014.09   61.56
 5019.99   63.83 5031.59   69.59 5047.69   75.29  5050.8    75.3  5055.4    76.8
  5085.4    77.1  5280.5    75.4  5295.5    76.7  5369.2    76.6  5415.6    77.7
#Mann= 3 , 1 , 0
  4276.7     .04       0 4942.49     .04       0 5047.69      .1       0
Bank Sta=4942.49,5047.69
XS Rating Curve= 0 ,0
Exp/Cntr=0.5,0.3

Type RM Length L Ch R = 1 ,4176.8  ,22,22,22
BEGIN DESCRIPTION:
Upstream Section of Bridge/Culvert/Weir
END DESCRIPTION:
XS GIS Cut Line= 5
      3126252.72     13911624.43      3124255.63     13911515.69
      3124219.88     13911514.09      3124160.17     13911510.15
      3122734.71     13911443.39
#Sta/Elev= 30
  2955.5   77.48  3095.5   74.88  3245.5   76.48  3345.5   74.88  3545.5   75.98
  3698.5   74.71  4164.2   76.08  4604.2   74.38 4631.69   75.41 4637.39   76.88
  4914.7   76.43 4926.79    76.3 4942.49   73.25 4974.69   65.95 4978.19    63.3
 4994.69    60.6 5009.09   61.25 5010.39   60.03 5031.59   70.26 5047.69   75.96
  5166.9    75.6  5408.5   75.78  5558.5   73.48  5768.2   75.78  6058.2   74.68
  6098.2   76.28  6178.2   74.38  6248.2   76.58  6418.2   75.58  6478.2   77.38
#Mann= 6 , 1 , 0
  2955.5      .2       0  3698.5      .1       0  4914.7     .07       0
 4942.49     .04       0 5047.69     .07       0  5166.9      .1       0
#XS Ineff= 2 , 0
       0    4917    76.9    5073       0    76.9
Permanent Ineff=
       F       F
Bank Sta=4942.49,5047.69
XS Rating Curve= 0 ,0
Exp/Cntr=0.5,0.3