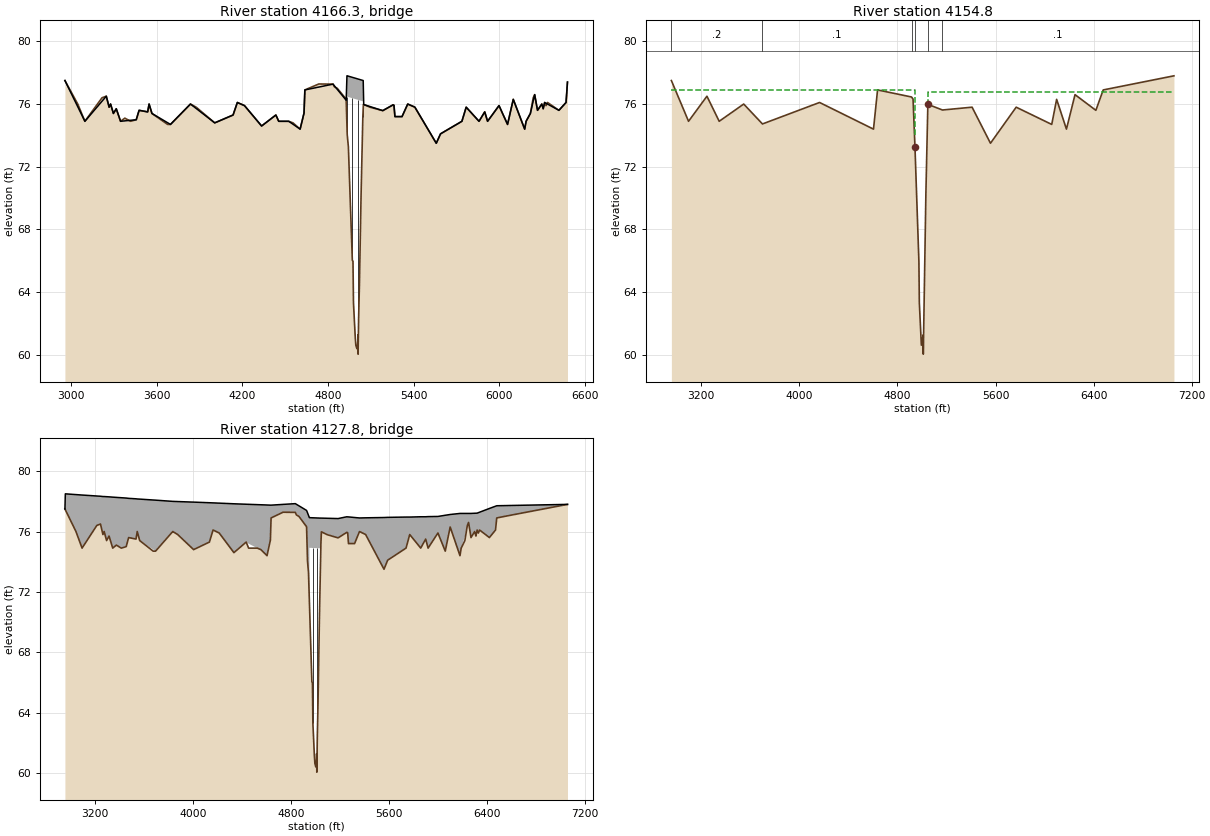
HEC-RAS study P140-00-00.prj: P140-00-00 (Hoods Bayou)

--- P140-00-00.g01 (geometry) --- (continued)

Type RM Length L Ch R = 3 ,4166.3  ,,,
BEGIN DESCRIPTION:
16" PIPELINE U/S of GREENS ROAD
END DESCRIPTION:
Bridge Culvert--1,0,-1,-1, 0
Deck Dist Width WeirC Skew NumUp NumDn MinLoCord MaxHiCord MaxSubmerge Is_Ogee
10,1,2.6,0, 60, 60, , , 0.95, 0, 1,1,,
  2955.5  3095.5  3245.5  3265.5  3275.5  3295.5  3315.5  3345.5  3455.5  3475.5
  3535.5  3545.5  3565.5  3695.5  3835.5  4005.5  4134.2  4164.2  4214.2  4334.2
  4434.2  4454.2  4524.2  4604.2 4631.69 4637.39 4834.89 4927.09 4932.29 4934.19
 5046.39 5049.99 5183.49 5255.99 5262.19  5268.6  5318.5  5358.5  5408.5  5558.5
  5588.5  5738.2  5768.2  5858.2  5898.2  5918.2  5998.2  6058.2  6098.2  6178.2
  6188.2  6218.2  6248.2  6268.2  6298.2  6308.2  6318.2  6418.2  6468.2  6478.2
    77.5    74.9    76.5    75.8      76    75.4    75.7    74.9      75    75.6
    75.5      76    75.4    74.7      76    74.8    75.3    76.1    75.9    74.6
    75.3    74.9    74.9    74.4   75.43    76.9   77.27   76.24    77.8    77.8
    77.5   75.97   75.58   75.95   75.92    75.2    75.2      76    75.8    73.5
    74.1    74.9    75.8    74.9    75.5    74.9    75.9    74.7    76.3    74.4
    74.9    75.4    76.6    75.6      76    75.7    76.1    75.6    76.1    77.4
    77.5    74.9    76.5    75.8      76    75.4    75.7    74.9      75    75.6
    75.5      76    75.4    74.7      76    74.8    75.3    76.1    75.9    74.6
    75.3    74.9    74.9    74.4   75.43    76.9   77.27   76.23   76.47   76.47
   76.17   75.97   75.58   75.95   75.92    75.2    75.2      76    75.8    73.5
    74.1    74.9    75.8    74.9    75.5    74.9    75.9    74.7    76.3    74.4
    74.9    75.4    76.6    75.6      76    75.7    76.1    75.6    76.1    77.4
  2955.5  3095.5  3245.5  3265.5  3275.5  3295.5  3315.5  3345.5  3455.5  3475.5
  3535.5  3545.5  3565.5  3695.5  3835.5  4005.5  4134.2  4164.2  4214.2  4334.2
  4434.2  4454.2  4524.2  4604.2 4631.69 4637.39 4834.89 4927.09 4932.29 4934.19
 5046.39 5049.99 5183.49 5255.99 5262.19  5268.6  5318.5  5358.5  5408.5  5558.5
  5588.5  5738.2  5768.2  5858.2  5898.2  5918.2  5998.2  6058.2  6098.2  6178.2
  6188.2  6218.2  6248.2  6268.2  6298.2  6308.2  6318.2  6418.2  6468.2  6478.2
    77.5    74.9    76.5    75.8      76    75.4    75.7    74.9      75    75.6
    75.5      76    75.4    74.7      76    74.8    75.3    76.1    75.9    74.6
    75.3    74.9    74.9    74.4   75.43    76.9   77.27   76.24    77.8    77.8
    77.5   75.97   75.58   75.95   75.92    75.2    75.2      76    75.8    73.5
    74.1    74.9    75.8    74.9    75.5    74.9    75.9    74.7    76.3    74.4
    74.9    75.4    76.6    75.6      76    75.7    76.1    75.6    76.1    77.4
    77.5    74.9    76.5    75.8      76    75.4    75.7    74.9      75    75.6
    75.5      76    75.4    74.7      76    74.8    75.3    76.1    75.9    74.6
    75.3    74.9    74.9    74.4   75.43    76.9   77.27   76.23   76.47   76.47
   76.17   75.97   75.58   75.95   75.92    75.2    75.2      76    75.8    73.5
    74.1    74.9    75.8    74.9    75.5    74.9    75.9    74.7    76.3    74.4
    74.9    75.4    76.6    75.6      76    75.7    76.1    75.6    76.1    77.4
Pier Skew, UpSta & Num, DnSta & Num=  ,4934.2, 2 ,4934.2, 2 , 0 , 0 , 0 ,,
     1.5     1.5
   72.99   77.47
     1.5     1.5
   72.99   77.47
Pier Skew, UpSta & Num, DnSta & Num=  ,4970.1, 2 ,4970.1, 2 , 0 , 0 , 0 ,,
     1.5     1.5
   65.03   77.37
     1.5     1.5
   65.03   77.37
Pier Skew, UpSta & Num, DnSta & Num=  ,5010.4, 2 ,5010.4, 2 , 0 , 0 , 0 ,,
     1.5     1.5
    59.5   77.27
     1.5     1.5
    59.5   77.27
Pier Skew, UpSta & Num, DnSta & Num=  ,5043.8, 2 ,5043.8, 2 , 0 , 0 , 0 ,,
     1.5     1.5
   73.89   77.18
     1.5     1.5
   73.89   77.18
BR Coef= 1 , 1 , 0 ,1.25, 0 ,,,0.8,0,2,0,
WSPro=,,,, 1 ,,,, 0 ,,,, 0 ,,,,-1 ,-1 ,-1 , 0 , 0 , 0 , 0 , 0
BR U #Sta/Elev= 98
  2955.5    77.5  3045.5      76  3095.5    74.9  3215.5    76.4  3245.5    76.5
  3265.5    75.8  3275.5      76  3295.5    75.4  3315.5    75.7  3345.5    74.9
  3375.5    75.1  3415.5    74.9  3455.5      75  3475.5    75.6  3535.5    75.5
  3545.5      76  3565.5    75.4  3675.5    74.7  3695.5    74.7  3698.5   74.73
  3835.5      76  3875.5    75.8  4005.5    74.8  4134.2    75.3  4164.2    76.1
  4214.2    75.9  4334.2    74.6  4434.2    75.3  4454.2    74.9  4524.2    74.9
  4554.2    74.8  4604.2    74.4 4631.69   75.43 4637.39    76.9 4735.19   77.28
 4834.89   77.27 4844.29    77.1 4864.79      77  4914.7   76.45 4926.79   76.32
 4926.89   76.29    4927   76.26 4927.09   76.23 4932.29   74.64 4934.19   74.06
 4942.49   73.27 4970.09   66.04 4974.69   65.97 4978.19   63.32 4990.89   61.07
 4994.69   60.62 5000.99   60.43 5005.09   60.38 5008.99   60.94 5009.09   61.27
 5010.39   60.05 5014.09   62.25 5019.99   64.52 5031.59   70.28 5043.79   75.19
 5046.39   75.72 5047.69   75.98 5049.78   75.97 5049.89   75.97 5049.99   75.97
 5093.29    75.8  5166.9   75.62 5183.49   75.58 5255.99   75.95 5262.19   75.92
  5268.6    75.2  5318.5    75.2  5358.5      76  5408.5    75.8  5558.5    73.5
  5588.5    74.1  5738.2    74.9  5768.2    75.8  5858.2    74.9  5898.2    75.5
  5918.2    74.9  5998.2    75.9  6058.2    74.7  6098.2    76.3  6178.2    74.4
  6188.2    74.9  6218.2    75.4  6238.2    76.4  6248.2    76.6  6268.2    75.6
  6298.2      76  6308.2    75.7  6318.2    76.1  6328.2    75.9  6338.2    76.1
  6418.2    75.6  6468.2    76.1  6478.2    77.4
BR U #Mann= 6
  2955.5      .2  3698.5      .1  4914.7     .07 4942.49     .04 5047.69     .07
  5166.9      .1
BR U Banks=4942.49,5047.69
BR D #Sta/Elev= 98
  2955.5    77.5  3045.5      76  3095.5    74.9  3215.5    76.4  3245.5    76.5
  3265.5    75.8  3275.5      76  3295.5    75.4  3315.5    75.7  3345.5    74.9
  3375.5    75.1  3415.5    74.9  3455.5      75  3475.5    75.6  3535.5    75.5
  3545.5      76  3565.5    75.4  3675.5    74.7  3695.5    74.7  3698.5   74.73
  3835.5      76  3875.5    75.8  4005.5    74.8  4134.2    75.3  4164.2    76.1
  4214.2    75.9  4334.2    74.6  4434.2    75.3  4454.2    74.9  4524.2    74.9
  4554.2    74.8  4604.2    74.4 4631.69   75.43 4637.39    76.9 4735.19   77.28
 4834.89   77.27 4844.29    77.1 4864.79      77  4914.7   76.45 4926.79   76.32
 4926.89   76.29    4927   76.26 4927.09   76.23 4932.29   74.64 4934.19   74.06
 4942.49   73.27 4970.09   66.04 4974.69   65.97 4978.19   63.32 4990.89   61.07
 4994.69   60.62 5000.99   60.43 5005.09   60.38 5008.99   60.94 5009.09   61.27
 5010.39   60.05 5014.09   62.25 5019.99   64.52 5031.59   70.28 5043.79   75.19
 5046.39   75.72 5047.69   75.98 5049.78   75.97 5049.89   75.97 5049.99   75.97
 5093.29    75.8  5166.9   75.62 5183.49   75.58 5255.99   75.95 5262.19   75.92
  5268.6    75.2  5318.5    75.2  5358.5      76  5408.5    75.8  5558.5    73.5
  5588.5    74.1  5738.2    74.9  5768.2    75.8  5858.2    74.9  5898.2    75.5
  5918.2    74.9  5998.2    75.9  6058.2    74.7  6098.2    76.3  6178.2    74.4
  6188.2    74.9  6218.2    75.4  6238.2    76.4  6248.2    76.6  6268.2    75.6
  6298.2      76  6308.2    75.7  6318.2    76.1  6328.2    75.9  6338.2    76.1
  6418.2    75.6  6468.2    76.1  6478.2    77.4
BR D #Mann= 6
  2955.5      .2  3698.5      .1  4914.7     .07 4942.49     .04 5047.69     .07
  5166.9      .1
BR D Banks=4942.49,5047.69
BC Design=,, 0 ,, 0 ,,,,,,
BC HTab HWMax=77.48
BC Use User HTab Curves=0
BC User HTab FreeFlow(D)= 0

Type RM Length L Ch R = 1 ,4154.8  ,54,54,54
BEGIN DESCRIPTION:
Upstream Section of Bridge/Culvert/Weir
END DESCRIPTION:
XS GIS Cut Line= 6
      3126254.52     13911584.53      3125067.75      13911522.3
      3124264.36     13911475.66      3124178.38     13911475.66
      3123442.26     13911438.86        3122160.     13911384.82
#Sta/Elev= 30
  2955.5    77.5  3095.5    74.9  3245.5    76.5  3345.5    74.9  3545.5      76
  3698.5   74.73  4164.2    76.1  4604.2    74.4  4637.4    76.9  4914.7   76.45
  4926.8   76.32  4942.5   73.27  4974.6   65.97  4978.2   63.32  4994.7   60.62
  5009.1   61.27  5010.4   60.05  5031.6   70.28  5047.7   75.98  5166.9   75.62
  5408.5    75.8  5558.5    73.5  5768.2    75.8  6058.2    74.7  6098.2    76.3
  6178.2    74.4  6248.2    76.6  6418.2    75.6  6478.2    76.9  7055.1    77.8
#Mann= 6 , 1 , 0
  2955.5      .2       0  3698.5      .1       0  4914.7     .07       0
  4942.5     .04       0  5047.7     .07       0  5166.9      .1       0
#XS Ineff= 2 , 0
       0    4939    76.9    5051       0    76.8
Permanent Ineff=
       F       F
Bank Sta=4942.5,5047.7
XS Rating Curve= 0 ,0
Exp/Cntr=0.5,0.3

Type RM Length L Ch R = 3 ,4127.8  ,,,
BEGIN DESCRIPTION:
GREENS ROAD
Structure ID: P40-02
END DESCRIPTION:
Bridge Culvert--1,0,-1,-1, 0
Deck Dist Width WeirC Skew NumUp NumDn MinLoCord MaxHiCord MaxSubmerge Is_Ogee
10,34,2.6,0, 60, 60, , , 0.95, 0, 1,1,,
  2955.5  2958.9  3095.5  3245.5  3265.5  3275.5  3295.5  3315.5  3345.5  3455.5
  3475.5  3535.5  3545.5  3565.5  3695.5  3835.5  4005.5  4134.2  4164.2  4334.2
  4434.2  4604.2  4631.7  4637.4  4834.9  4926.8  4934.2  4942.5 4949.81  4949.9
 5040.79  5040.9  5043.8  5047.7  5183.5    5256  5262.2  5268.6  5318.5  5358.5
  5408.5  5558.5  5588.5  5738.2  5768.2  5858.2  5898.2  5918.2  5998.2  6058.2
  6098.2  6178.2  6248.2  6268.2  6318.2  6418.2  6468.2  6478.2    7055  7055.1
    77.5    78.5   78.42   78.34   78.32   78.32   78.31    78.3   78.28   78.22
    78.2   78.17   78.16   78.15   78.08      78   77.95   77.91    77.9   77.84
   77.81   77.76   77.75   77.75   77.85    77.4   77.25   77.07   76.92   76.92
   76.89   76.89   76.89   76.89   76.86   76.98   76.97   76.97   76.93    76.9
   76.91   76.93   76.94   76.96   76.96   76.98   76.98   76.99      77   77.08
   77.13    77.2    77.2    77.2   77.22   77.53   77.68   77.71    77.8    77.8
    77.5   77.44    74.9    76.5    75.8      76    75.4    75.7    74.9      75
    75.6    75.5      76    75.4    74.7      76    74.8    75.3    76.1    74.6
    75.3    74.4   75.43    76.9   77.27   76.32   74.06   73.27   71.36   74.92
   74.89   74.02   75.19   75.98   75.58   75.95   75.92    75.2    75.2      76
    75.8    73.5    74.1    74.9    75.8    74.9    75.5    74.9    75.9    74.7
    76.3    74.4    76.6    75.6    76.1    75.6    76.1    76.9    77.8    77.8
  2955.5  2958.9  3095.5  3245.5  3265.5  3275.5  3295.5  3315.5  3345.5  3455.5
  3475.5  3535.5  3545.5  3565.5  3695.5  3835.5  4005.5  4134.2  4164.2  4334.2
  4434.2  4604.2  4631.7  4637.4  4834.9  4926.8  4934.2  4942.5 4949.81  4949.9
 5040.79  5040.9  5043.8  5047.7  5183.5    5256  5262.2  5268.6  5318.5  5358.5
  5408.5  5558.5  5588.5  5738.2  5768.2  5858.2  5898.2  5918.2  5998.2  6058.2
  6098.2  6178.2  6248.2  6268.2  6318.2  6418.2  6468.2  6478.2    7055  7055.1
    77.5    78.5   78.42   78.34   78.32   78.32   78.31    78.3   78.28   78.22
    78.2   78.17   78.16   78.15   78.08      78   77.95   77.91    77.9   77.84
   77.81   77.76   77.75   77.75   77.85    77.4   77.25   77.07   76.92   76.92
   76.89   76.89   76.89   76.89   76.86   76.98   76.97   76.97   76.93    76.9
   76.91   76.93   76.94   76.96   76.96   76.98   76.98   76.99      77   77.08
   77.13    77.2    77.2    77.2   77.22   77.53   77.68   77.71    77.8    77.8
    77.2   77.14    74.6    76.2    75.5    75.7    75.1    75.4    74.6    74.7
    75.3    75.2    75.7    75.1    74.4    75.7    74.5      75    75.8    74.3
      75    74.1   75.13    76.6   76.97   76.02   73.76   72.97   71.06   74.62
   74.59   73.72   74.89   75.68   75.28   75.65   75.62    74.9    74.9    75.7
    75.5    73.2    73.8    74.6    75.5    74.6    75.2    74.6    75.6    74.4
      76    74.1    76.3    75.3    75.8    75.3    75.8    76.6    77.5    77.5
Pier Skew, UpSta & Num, DnSta & Num=  ,4978.2, 2 ,4978.2, 2 , 0 , 0 , 0 ,,
     1.4     1.4
    62.2   75.91
     1.4     1.4
    61.9   75.61
Pier Skew, UpSta & Num, DnSta & Num=  ,5009, 2 ,5009, 2 , 0 , 0 , 0 ,,
     1.4     1.4
   59.71    75.9
     1.4     1.4
   59.41    75.6
Abutment Skew #Up #Dn= , 2 , 2
  4949.7  4974.7
   74.92    65.9
  4949.7  4974.7
   74.62    65.6
Abutment Skew #Up #Dn= , 2 , 2
  5031.6 5040.99
   70.28   74.89
  5031.6 5040.99
   69.98   74.59
BR Coef= 1 , 1 , 0 ,1.25, 0 ,,,0.8,0,2,0,
WSPro=,,,, 1 ,,,, 0 ,,,, 0 ,,,,-1 ,-1 ,-1 , 0 , 0 , 0 , 0 , 0
BR U #Sta/Elev= 120
  2955.5    77.5  2958.9   77.44  3045.5      76  3095.5    74.9  3215.5    76.4
  3245.5    76.5  3265.5    75.8  3275.5      76  3295.5    75.4  3315.5    75.7
  3345.5    74.9  3375.5    75.1  3415.5    74.9  3455.5      75  3475.5    75.6
  3535.5    75.5  3545.5      76  3565.5    75.4  3675.5    74.7  3695.5    74.7
  3698.5   74.73  3830.9   75.96  3835.5      76  3875.5    75.8  4005.5    74.8
  4134.2    75.3  4164.2    76.1  4214.2    75.9  4334.2    74.6  4434.2    75.3
  4454.2    74.9  4524.2    74.9  4554.2    74.8  4604.2    74.4  4631.7   75.43
  4635.3   76.36  4637.4    76.9    4735   77.28  4735.2   77.28  4834.9   77.27
  4841.4   77.15  4844.3    77.1  4864.8      77  4914.7   76.45  4926.8   76.32
  4927.1   76.23  4934.2   74.06  4942.5   73.27  4949.7   71.38 4949.81   71.36
  4949.9   71.33 4949.99   71.31  4950.1   71.28 4950.21   71.25  4970.1   66.04
  4974.6   65.97  4974.7    65.9  4978.2   63.32  4990.9   61.07  4994.7   60.62
    5001   60.43  5005.1   60.38    5009   60.94  5009.1   61.27  5010.4   60.05
  5014.1   62.25    5020   64.52  5031.5   70.23  5031.6   70.28 5040.29   73.78
  5040.4   73.82 5040.51   73.87 5040.79   73.98  5040.9   74.02    5041   74.06
  5043.8   75.19  5047.7   75.98  5093.3    75.8  5096.3   75.79  5166.9   75.62
  5183.5   75.58  5187.9    75.6  5255.7   75.95    5256   75.95  5262.2   75.92
  5268.6    75.2  5318.5    75.2  5354.6   75.92  5358.5      76  5408.5    75.8
  5558.5    73.5  5588.5    74.1  5738.2    74.9  5768.2    75.8  5858.2    74.9
  5898.2    75.5  5918.2    74.9  5998.2    75.9  6001.7   75.83  6058.2    74.7
  6098.2    76.3  6151.7   75.03  6178.2    74.4  6188.2    74.9  6218.2    75.4
  6238.2    76.4  6248.2    76.6  6268.2    75.6  6298.2      76  6308.2    75.7
  6311.7   75.84  6318.2    76.1  6328.2    75.9  6338.2    76.1  6418.2    75.6
  6468.2    76.1  6478.2    76.9  6571.7   77.05    7055    77.8  7055.1    77.8
BR U #Mann= 6
  2955.5      .2  3698.5      .1  4914.7     .07  4942.5     .04  5047.7     .07
  5166.9      .1
BR U Banks=4942.5,5047.7
BR D #Sta/Elev= 120
  2955.5    77.2  2958.9   77.14  3045.5    75.7  3095.5    74.6  3215.5    76.1
  3245.5    76.2  3265.5    75.5  3275.5    75.7  3295.5    75.1  3315.5    75.4
  3345.5    74.6  3375.5    74.8  3415.5    74.6  3455.5    74.7  3475.5    75.3
  3535.5    75.2  3545.5    75.7  3565.5    75.1  3675.5    74.4  3695.5    74.4
  3698.5   74.43  3830.9   75.66  3835.5    75.7  3875.5    75.5  4005.5    74.5
  4134.2      75  4164.2    75.8  4214.2    75.6  4334.2    74.3  4434.2      75
  4454.2    74.6  4524.2    74.6  4554.2    74.5  4604.2    74.1  4631.7   75.13
  4635.3   76.06  4637.4    76.6    4735   76.98  4735.2   76.98  4834.9   76.97
  4841.4   76.85  4844.3    76.8  4864.8    76.7  4914.7   76.15  4926.8   76.02
  4927.1   75.93  4934.2   73.76  4942.5   72.97  4949.7   71.08 4949.81   71.06
  4949.9   71.03 4949.99   71.01  4950.1   70.98 4950.21   70.95  4970.1   65.74
  4974.6   65.67  4974.7    65.6  4978.2   63.02  4990.9   60.77  4994.7   60.32
    5001   60.13  5005.1   60.08    5009   60.64  5009.1   60.97  5010.4   59.75
  5014.1   61.95    5020   64.22  5031.5   69.93  5031.6   69.98 5040.29   73.48
  5040.4   73.52 5040.51   73.57 5040.79   73.68  5040.9   73.72    5041   73.76
  5043.8   74.89  5047.7   75.68  5093.3    75.5  5096.3   75.49  5166.9   75.32
  5183.5   75.28  5187.9    75.3  5255.7   75.65    5256   75.65  5262.2   75.62
  5268.6    74.9  5318.5    74.9  5354.6   75.62  5358.5    75.7  5408.5    75.5
  5558.5    73.2  5588.5    73.8  5738.2    74.6  5768.2    75.5  5858.2    74.6
  5898.2    75.2  5918.2    74.6  5998.2    75.6  6001.7   75.53  6058.2    74.4
  6098.2      76  6151.7   74.73  6178.2    74.1  6188.2    74.6  6218.2    75.1
  6238.2    76.1  6248.2    76.3  6268.2    75.3  6298.2    75.7  6308.2    75.4
  6311.7   75.54  6318.2    75.8  6328.2    75.6  6338.2    75.8  6418.2    75.3
  6468.2    75.8  6478.2    76.6  6571.7   76.75    7055    77.5  7055.1    77.5
BR D #Mann= 6
  2955.5      .2  3698.5      .1  4914.7     .07  4942.5     .04  5047.7     .07
  5166.9      .1
BR D Banks=4942.5,5047.7
BC Design=,, 0 ,, 0 ,,,,,,
BC HTab HWMax=77.8
BC Use User HTab Curves=0
BC User HTab FreeFlow(D)= 0