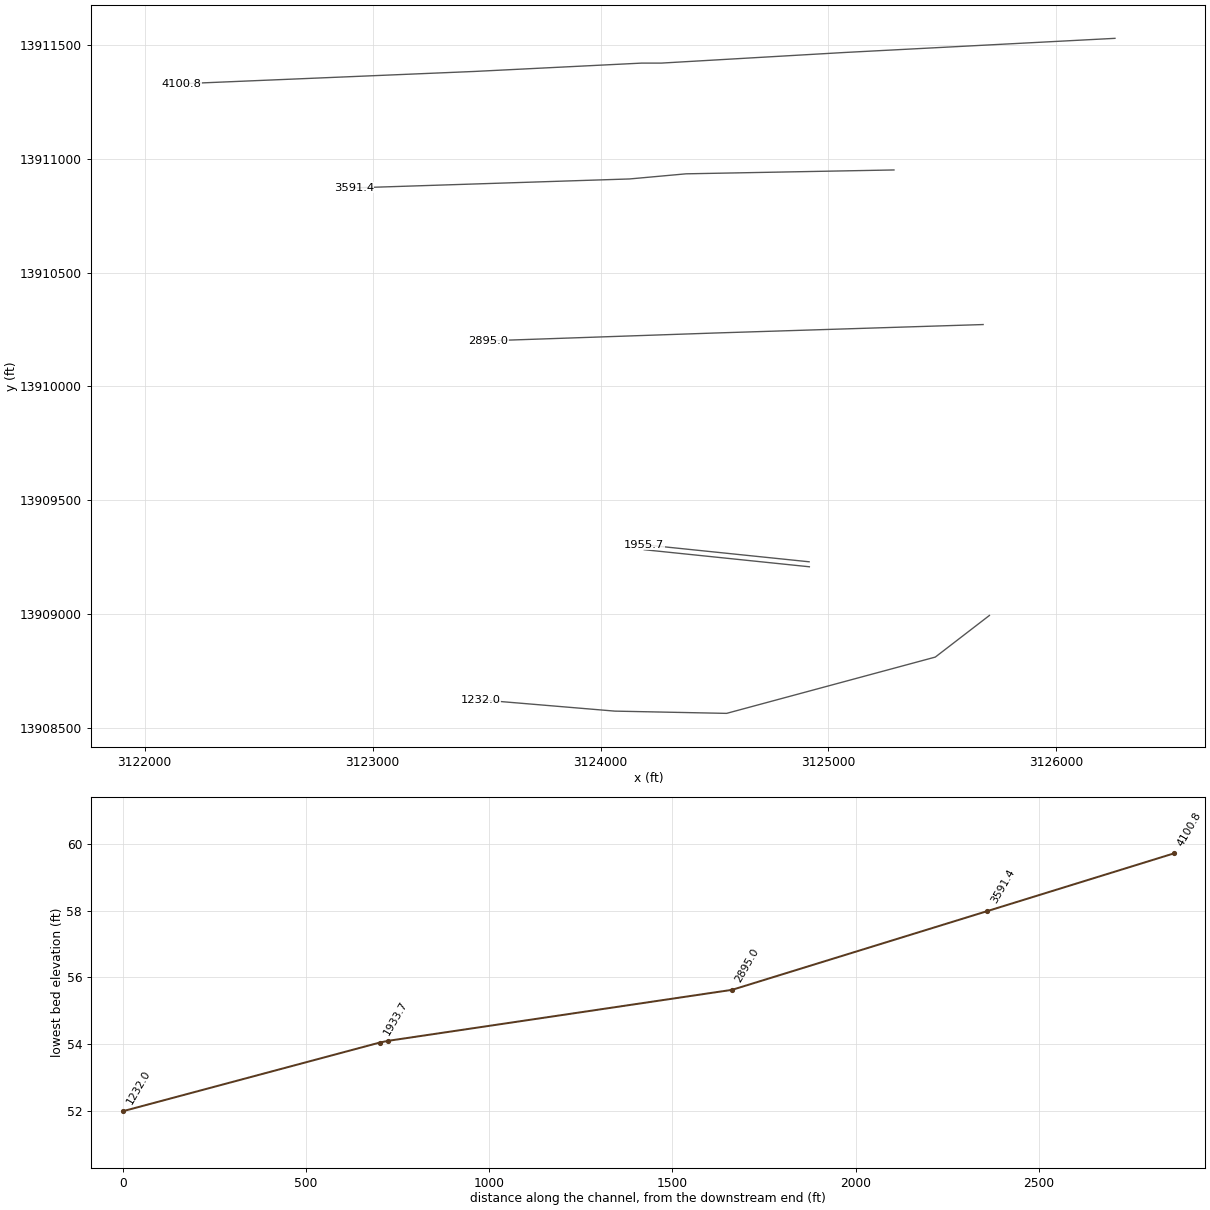
HEC-RAS study P140-00-00.prj: P140-00-00 (Hoods Bayou)

--- P140-00-00.g01 (geometry) --- (continued)

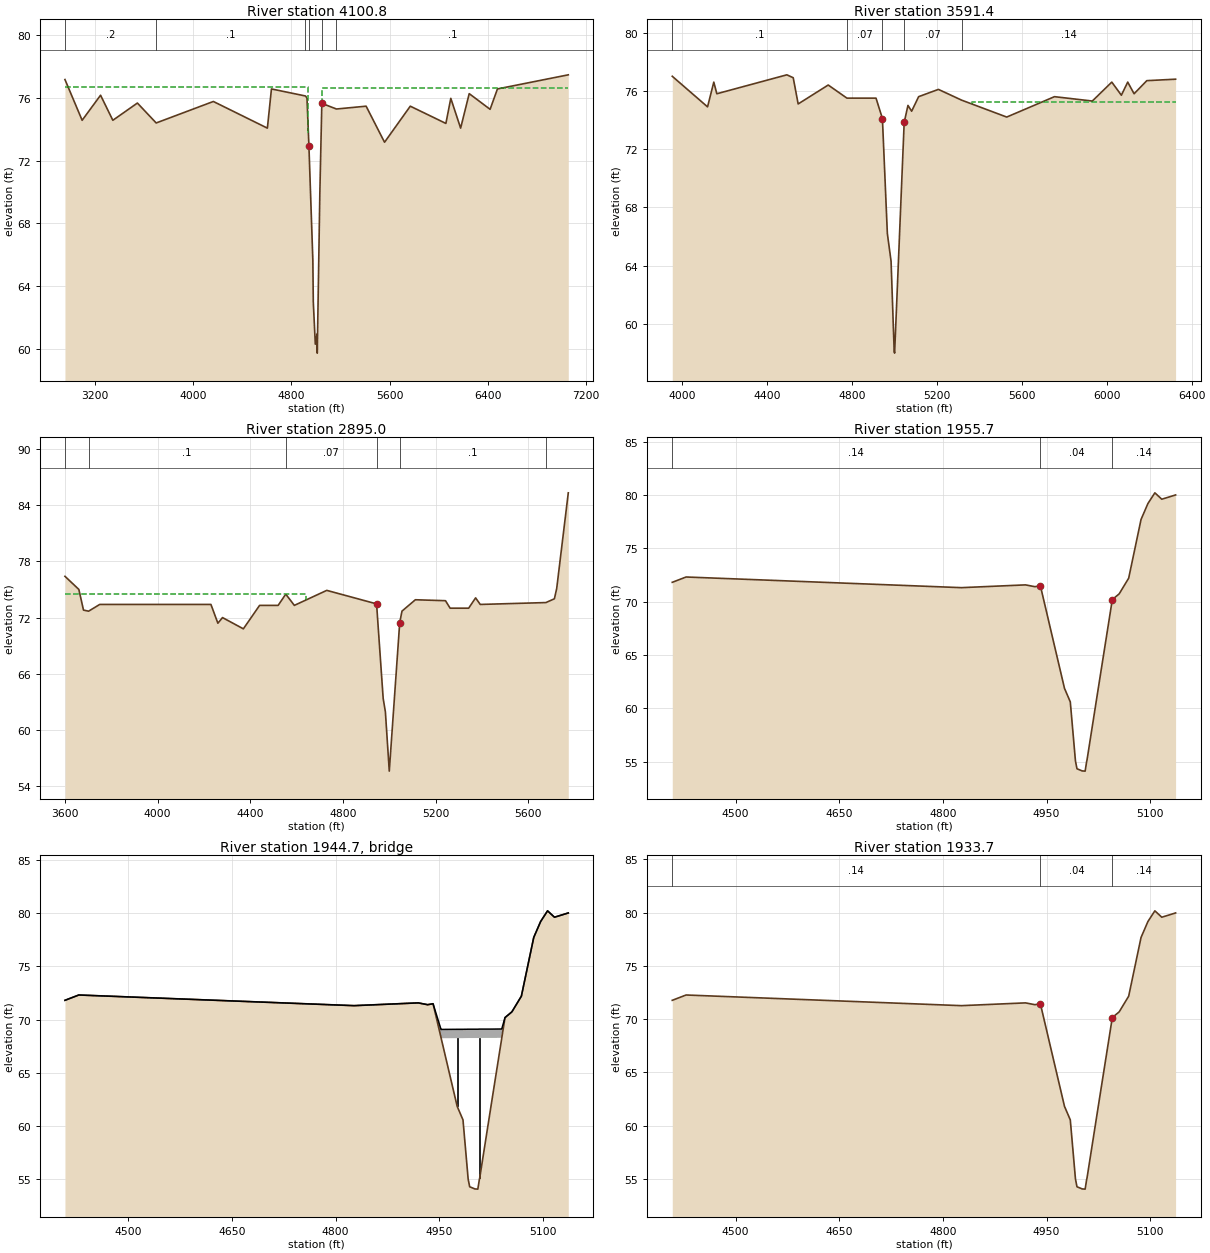
Type RM Length L Ch R = 1 ,4100.8  ,509.4,509.4,509.4
BEGIN DESCRIPTION:
Downstream Section of Bridge/Culvert/Weir
END DESCRIPTION:
XS GIS Cut Line= 6
      3126257.03     13911530.59      3125070.27     13911468.36
      3124266.88     13911421.72       3124180.9     13911421.72
      3123444.78     13911384.92      3122162.52     13911330.88
#Sta/Elev= 30
  2955.5   77.17  3095.5   74.57  3245.5   76.17  3345.5   74.57  3545.5   75.67
  3698.5    74.4  4164.2   75.77  4604.2   74.07  4637.4   76.57  4914.7   76.12
  4926.8   75.99  4942.5   72.94  4974.6   65.64  4978.2   62.99  4994.7   60.29
  5009.1   60.94  5010.4   59.72  5031.6   69.95  5047.7   75.65  5166.9   75.29
  5408.5   75.47  5558.5   73.17  5768.2   75.47  6058.2   74.37  6098.2   75.97
  6178.2   74.07  6248.2   76.27  6418.2   75.27  6478.2   76.57  7055.1   77.47
#Mann= 6 , 1 , 0
  2955.5      .2       0  3698.5      .1       0  4914.7     .07       0
  4942.5     .04       0  5047.7     .07       0  5166.9      .1       0
#XS Ineff= 2 , 0
       0    4939    76.7    5051       0    76.6
Permanent Ineff=
       F       F
Bank Sta=4942.5,5047.7
XS Rating Curve= 0 ,0
Exp/Cntr=0.5,0.3

Type RM Length L Ch R = 1 ,3591.4  ,699.8,696.4,693.4
BEGIN DESCRIPTION:
Cross Section 3591.4-Interpolated
END DESCRIPTION:
XS GIS Cut Line= 4
      3125287.46     13910951.91      3124375.27     13910934.89
      3124127.43     13910912.36      3122916.98     13910872.99
#Sta/Elev= 30
  3952.1      77  4118.4    74.9  4147.9    76.6  4162.1    75.8  4492.2    77.1
  4522.2    76.9  4545.5    75.1  4687.2    76.4  4775.2    75.5  4912.4    75.5
  4942.6    74.1  4965.9    66.2  4983.4    64.3  4998.1   58.11  5000.1   57.99
  5045.2   73.83    5063      75  5080.3    74.6  5113.3    75.6  5206.5    76.1
  5316.2   75.36  5528.5    74.2  5753.6    75.6  5931.9    75.3  6023.7    76.6
  6068.8    75.7  6098.8    76.6  6128.8    75.8  6188.8    76.7  6324.4    76.8
#Mann= 5 , 1 , 0
  3952.1      .1       0  4775.2     .07       0  4942.6     .04       0
  5045.2     .07       0  5316.2     .14       0
#XS Ineff= 2 , 0
       0                  5363.4       0    75.2
Permanent Ineff=
       F       F
Bank Sta=4942.6,5045.2
XS Rating Curve= 0 ,0
Exp/Cntr=0.3,0.1

Type RM Length L Ch R = 1 ,2895.0  ,936.5,939.3,942.1
BEGIN DESCRIPTION:
Cross Section 2895.0
END DESCRIPTION:
XS GIS Cut Line= 3
       3125678.6     13910272.23      3124506.91     13910235.18
      3123507.48     13910200.72
#Sta/Elev= 30
  3600.4    76.4  3660.4      75  3680.4    72.8  3702.3   72.68  3750.4    73.4
  4230.4    73.4  4260.4    71.4  4280.4      72  4370.4    70.8  4440.4    73.3
  4520.4    73.3  4553.4    74.5  4590.4    73.3  4730.4    74.9  4945.3   73.46
  4973.8   63.38  4983.4   61.94  5000.1   55.63  5045.2   71.47    5055   72.69
  5112.7    73.9  5242.7    73.8  5262.7      73  5342.7      73  5372.7    74.1
  5392.7    73.4    5676    73.6  5712.7      74  5722.7    75.1  5772.7    85.3
#Mann= 6 , 1 , 0
  3600.4      .2       0  3702.3      .1       0  4553.4     .07       0
  4945.3     .04       0  5045.2      .1       0    5676     .14       0
#XS Ineff= 2 , 0
       0  4640.4    74.5               0
Permanent Ineff=
       F       F
Bank Sta=4945.3,5045.2
XS Rating Curve= 0 ,0
Exp/Cntr=0.5,0.3

Type RM Length L Ch R = 1 ,1955.7  ,22,22,22
BEGIN DESCRIPTION:
Upstream Section of Bridge/Culvert/Weir
END DESCRIPTION:
XS GIS Cut Line= 2
      3124915.11     13909229.17      3124190.58     13909304.15
#Sta/Elev= 29
  4408.4   71.82  4428.4   72.32  4826.8   71.32 4919.61   71.58 4933.21   71.41
 4941.11    71.5 4952.61   68.33 4952.82   68.27 4952.91   68.24 4976.01   61.87
 4984.41    60.6 4991.91   55.04 4994.11   54.32 5001.61   54.12 5005.91    54.1
 5008.11   55.01 5008.51    55.1 5025.81   62.24  5040.2   68.14 5040.31   68.19
 5040.51   68.27 5045.21    70.2 5055.21   70.74 5068.91   72.21  5086.8   77.72
  5096.8   79.22  5106.8   80.22  5116.8   79.62  5136.8   80.02
#Mann= 3 , 1 , 0
  4408.4     .14       0 4941.11     .04       0 5045.21     .14       0
#XS Ineff= 2 , 0
       0    4951    68.7  5041.7       0    68.7
Permanent Ineff=
       F       F
Bank Sta=4941.11,5045.21
XS Rating Curve= 0 ,0
Exp/Cntr=0.5,0.3

Type RM Length L Ch R = 3 ,1944.7  ,,,
BEGIN DESCRIPTION:
2 10" PIPELINES
END DESCRIPTION:
Bridge Culvert--1,0,-1,-1, 0
Deck Dist Width WeirC Skew NumUp NumDn MinLoCord MaxHiCord MaxSubmerge Is_Ogee
10,2,2.6,0, 29, 29, , , 0.95, 0, 1,1,,
  4408.4  4428.4  4826.8 4919.61 4933.21 4941.11 4952.61 4952.82 4952.91 4976.01
 4984.41 4991.91 4994.11 5001.61 5005.91 5008.11 5008.51 5025.81  5040.2 5040.31
 5040.51 5045.21 5055.21 5068.91  5086.8  5096.8  5106.8  5116.8  5136.8
    71.8    72.3    71.3   71.56   71.39   71.48   69.07   69.07   69.07   69.08
   69.08   69.09   69.09   69.09   69.09    69.1    69.1    69.1   69.11   69.11
   69.11   70.18   70.72   72.19    77.7    79.2    80.2    79.6      80
    71.8    72.3    71.3   71.56   71.39   71.48   68.31   68.25   68.24   68.25
   68.25   68.26   68.26   68.26   68.26   68.27   68.27   68.27   68.28   68.17
   68.25   70.18   70.72   72.19    77.7    79.2    80.2    79.6      80
  4408.4  4428.4  4826.8 4919.61 4933.21 4941.11 4952.61 4952.82 4952.91 4976.01
 4984.41 4991.91 4994.11 5001.61 5005.91 5008.11 5008.51 5025.81  5040.2 5040.31
 5040.51 5045.21 5055.21 5068.91  5086.8  5096.8  5106.8  5116.8  5136.8
    71.8    72.3    71.3   71.56   71.39   71.48   69.07   69.07   69.07   69.08
   69.08   69.09   69.09   69.09   69.09    69.1    69.1    69.1   69.11   69.11
   69.11   70.18   70.72   72.19    77.7    79.2    80.2    79.6      80
    71.8    72.3    71.3   71.56   71.39   71.48   68.31   68.25   68.24   68.25
   68.25   68.26   68.26   68.26   68.26   68.27   68.27   68.27   68.28   68.17
   68.25   70.18   70.72   72.19    77.7    79.2    80.2    79.6      80
Pier Skew, UpSta & Num, DnSta & Num=  ,4976, 2 ,4976, 2 , 0 , 0 , 0 ,,
       1       1
   60.77   69.25
       1       1
   60.77   69.25
Pier Skew, UpSta & Num, DnSta & Num=  ,5008.5, 2 ,5008.5, 2 , 0 , 0 , 0 ,,
       1       1
   53.95   69.27
       1       1
   53.95   69.27
BR Coef= 1 , 1 , 0 ,1.25, 0 ,,,0.8,0,2,0,
WSPro=,,,, 1 ,,,, 0 ,,,, 0 ,,,,-1 ,-1 ,-1 , 0 , 0 , 0 , 0 , 0
BR U #Sta/Elev= 29
  4408.4    71.8  4428.4    72.3  4826.8    71.3 4919.61   71.56 4933.21   71.39
 4941.11   71.48 4952.61   68.31 4952.82   68.25 4952.91   68.22 4976.01   61.85
 4984.41   60.58 4991.91   55.02 4994.11    54.3 5001.61    54.1 5005.91   54.08
 5008.11   54.99 5008.51   55.08 5025.81   62.22  5040.2   68.12 5040.31   68.17
 5040.51   68.25 5045.21   70.18 5055.21   70.72 5068.91   72.19  5086.8    77.7
  5096.8    79.2  5106.8    80.2  5116.8    79.6  5136.8      80
BR U #Mann= 3
  4408.4     .14 4941.11     .04 5045.21     .14
BR U Banks=4941.11,5045.21
BR D #Sta/Elev= 29
  4408.4    71.8  4428.4    72.3  4826.8    71.3 4919.61   71.56 4933.21   71.39
 4941.11   71.48 4952.61   68.31 4952.82   68.25 4952.91   68.22 4976.01   61.85
 4984.41   60.58 4991.91   55.02 4994.11    54.3 5001.61    54.1 5005.91   54.08
 5008.11   54.99 5008.51   55.08 5025.81   62.22  5040.2   68.12 5040.31   68.17
 5040.51   68.25 5045.21   70.18 5055.21   70.72 5068.91   72.19  5086.8    77.7
  5096.8    79.2  5106.8    80.2  5116.8    79.6  5136.8      80
BR D #Mann= 3
  4408.4     .14 4941.11     .04 5045.21     .14
BR D Banks=4941.11,5045.21
BC Design=,, 0 ,, 0 ,,,,,,
BC HTab HWMax=80.22
BC Use User HTab Curves=0
BC User HTab FreeFlow(D)= 0

Type RM Length L Ch R = 1 ,1933.7  ,701.7,701.7,701.7
BEGIN DESCRIPTION:
Downstream Section of Bridge/Culvert/Weir
END DESCRIPTION:
XS GIS Cut Line= 2
      3124916.21      13909207.2      3124191.68     13909282.18
#Sta/Elev= 29
  4408.4   71.77  4428.4   72.27  4826.8   71.27 4919.61   71.53 4933.21   71.36
 4941.11   71.45 4952.61   68.28 4952.82   68.22 4952.91   68.19 4976.01   61.82
 4984.41   60.55 4991.91   54.99 4994.11   54.27 5001.61   54.07 5005.91   54.05
 5008.11   54.96 5008.51   55.05 5025.81   62.19  5040.2   68.09 5040.31   68.14
 5040.51   68.22 5045.21   70.15 5055.21   70.69 5068.91   72.16  5086.8   77.67
  5096.8   79.17  5106.8   80.17  5116.8   79.57  5136.8   79.97
#Mann= 3 , 1 , 0
  4408.4     .14       0 4941.11     .04       0 5045.21     .14       0
#XS Ineff= 2 , 0
       0    4951    68.7  5041.7       0    68.7
Permanent Ineff=
       F       F
Bank Sta=4941.11,5045.21
XS Rating Curve= 0 ,0
Exp/Cntr=0.5,0.3

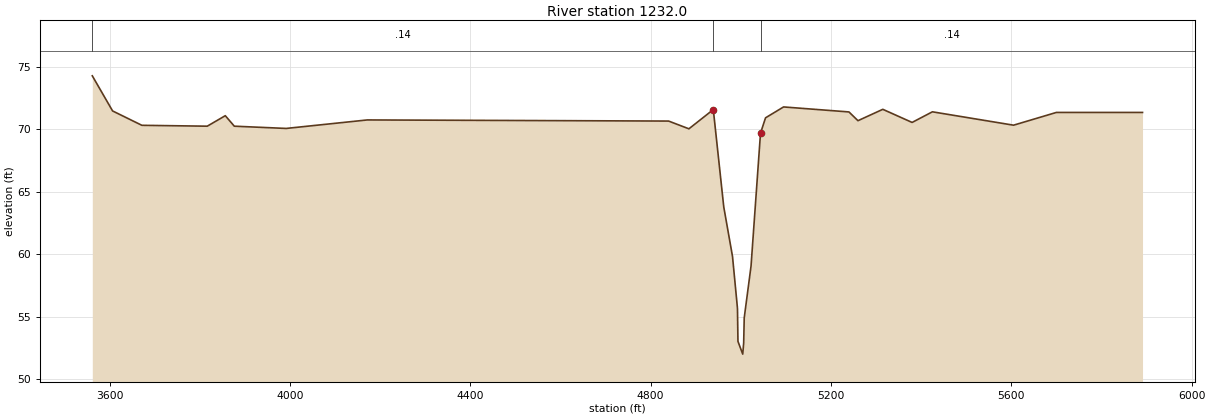
Type RM Length L Ch R = 1 ,1232.0  ,0,0,0
BEGIN DESCRIPTION:
Cross Section 1232.0 - Interpolated
END DESCRIPTION:
XS GIS Cut Line= 5
      3125706.25     13908993.28      3125468.68     13908810.15
      3124553.04     13908562.68      3124063.06     13908572.58
      3123474.08     13908622.07
#Sta/Elev= 30
  3561.4   74.26  3606.4   71.45  3671.4    70.3  3816.4   70.23  3856.4   71.07
  3876.4   70.23  3991.4   70.05  4171.4   70.73  4839.8   70.64  4884.8   70.02
  4938.9   71.56  4962.1   63.77  4981.5   59.81  4992.5   55.66  4993.6   53.01
  5004.2   51.99  5006.3    52.9  5007.5   54.89  5022.6   59.03  5043.6   69.67
  5054.8    70.9  5094.8   71.77  5239.8   71.37  5259.8   70.67  5314.9   71.58
  5379.9   70.53  5424.9   71.38  5604.9   70.31  5699.9   71.33    5891   71.33
#Mann= 3 , 1 , 0
  3561.4     .14       0  4938.9     .04       0  5043.6     .14       0
Bank Sta=4938.9,5043.6
XS Rating Curve= 0 ,0
Exp/Cntr=0.3,0.1

Chan Stop Cuts=-1
Use User Specified Reach Order=0
Composite Channel Slope=5